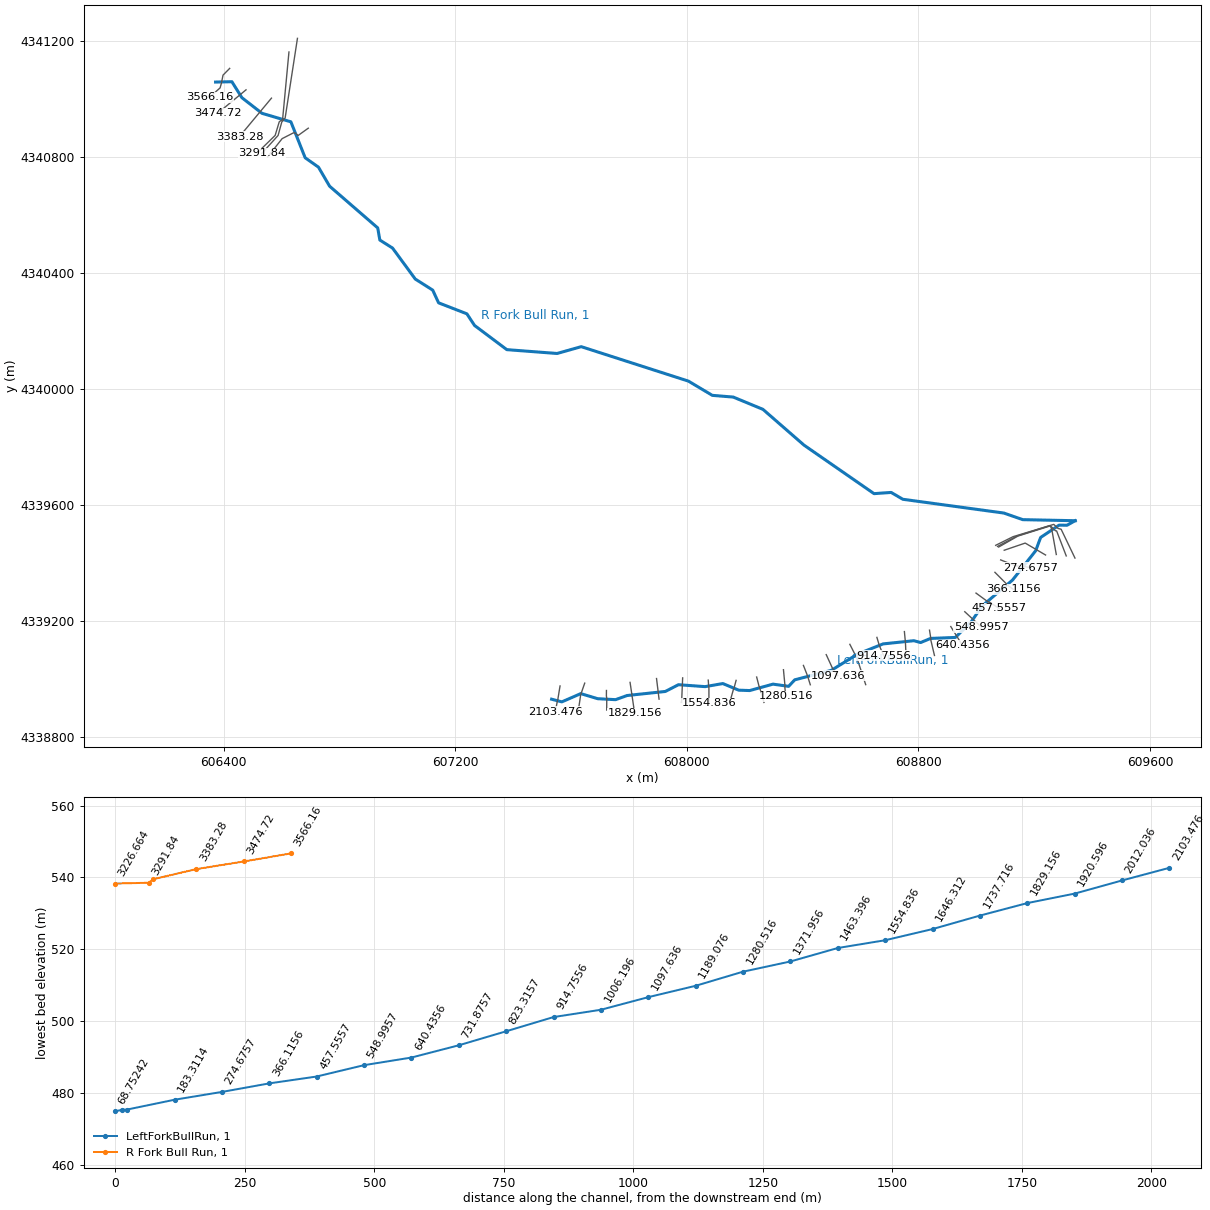
--- CheatRiver.prj (project) ---

Proj Title=CheatRiver
Current Plan=p01
Default Exp/Contr=0.3,0.1
SI Units
Geom File=g01
Flow File=f01
Plan File=p01
Y Axis Title=Elevation
X Axis Title(PF)=Main Channel Distance
X Axis Title(XS)=Station
BEGIN DESCRIPTION:
September 2018
Tucker County ABFE Study
US Army Corps of Engineers, Pittsburgh District
NAD 1983 UTM 17N (meters)
END DESCRIPTION:
DSS Export Rating Curves= 0
DSS Export Rating Curve Sorted= 0
DSS Export Volume Flow Curves= 0
DXF OffsetX= 0
DXF OffsetY= 0
DXF ScaleX= 1
DXF ScaleY= 10

--- CheatRiver.p01 (plan) ---

Plan Title=CheatRiver_plan
Program Version=5.05
Short Identifier=Plan1_subcritical
Geom File=g01
Flow File=f01
Subcritical Flow
K Sum by GR= 0
Std Step Tol= 0.003
Critical Tol= 0.003
Num of Std Step Trials= 20
Max Error Tol= 0.1
Flow Tol Ratio= 0.001
Split Flow NTrial= 30
Split Flow Tol= 0.006
Split Flow Ratio= 0.02
Log Output Level= 0
Friction Slope Method= 1
Unsteady Friction Slope Method= 2
Unsteady Bridges Friction Slope Method= 1
Parabolic Critical Depth
Global Vel Dist= 0 , 0 , 0
Global Log Level= 0
CheckData=True
Encroach Param=-1 ,0,0, 0
Computation Interval=1MIN
Output Interval=1HOUR
Instantaneous Interval=1HOUR
Mapping Interval=1HOUR
Computation Time Step Use Courant=        0
Computation Time Step Use Time Series=    0
Computation Time Step Count To Double=0
Computation Time Step Max Doubling=0
Computation Time Step Max Halving=0
Computation Time Step Residence Courant=0
Run HTab= 0
Run UNet= 0
Run Sediment= 0
Run PostProcess= 0
Run WQNet= 0
Run RASMapper=-1
UNET Theta= 1
UNET Theta Warmup= 1
UNET ZTol= 0.006
UNET ZSATol= 0.006
UNET MxIter= 20
UNET Max Iter WO Improvement= 0
UNET MaxInSteps= 0
UNET DtIC= 0
UNET DtMin= 0
UNET MaxCRTS= 20
UNET WFStab= 2
UNET SFStab= 1
UNET WFX= 1
UNET SFX= 1
UNET 1D Methodology=Finite Difference
UNET DSS MLevel= 4
UNET Pardiso=0
UNET DZMax Abort= 30
UNET Use Existing IB Tables=-1
UNET Froude Reduction=False
UNET Froude Limit= 0.8
UNET Froude Power= 4
UNET D1 Cores= 0
UNET D2 Coriolis=0
UNET D2 Cores= 0
UNET D2 Theta= 1
UNET D2 Theta Warmup= 1
UNET D2 Z Tol= 0.003
UNET D2 Volume Tol= 0.003
UNET D2 Max Iterations= 20
UNET D2 Equation= 0
UNET D2 RampUpFraction=0.1
UNET D2 TimeSlices= 1
UNET D2 BCVolumeCheck=0
UNET D1D2 MaxIter= 0
UNET D1D2 ZTol=0.003
UNET D1D2 QTol=0.1
UNET D1D2 MinQTol=0.03
Write IC File= 0
Write IC File at Fixed DateTime=0
Write IC File at Sim End=0
Echo Input=False
Echo Parameters=False
Echo Output=False
Write Detailed= 0
HDF Write Warmup=0
HDF Write Time Slices=0
HDF Flush=0
HDF Face Node Velocities=0
HDF Compression= 1
HDF Chunk Size= 1
HDF Spatial Parts= 1
HDF Use Max Rows=0
HDF Fixed Rows= 1
Calibration Method= 0
Calibration Iterations= 20
Calibration Max Change=0.05
Calibration Tolerance=0.2
Calibration Maximum=1.5
Calibration Minimum=0.5
Calibration Optimization Method= 1
WQ AD Non Conservative
WQ ULTIMATE=-1
WQ Max Comp Step=1HOUR
WQ Output Interval=15MIN
WQ Output Selected Increments= 0
WQ Output face flow=0
WQ Output face velocity=0
WQ Output face area=0
WQ Output face dispersion=0
WQ Output cell volume=0
WQ Output cell surface area=0
WQ Output cell continuity=0
WQ Output cumulative cell continuity=0
WQ Output face conc=0
WQ Output face dconc_dx=0
WQ Output face courant=0
WQ Output face peclet=0
WQ Output face adv mass=0
WQ Output face disp mass=0
WQ Output cell mass=0
WQ Output cell source sink temp=0
WQ Output nsm pathways=0
WQ Output nsm derived pathways=0
WQ Output MaxMinRange=-1
WQ Daily Max Min Mean=-1
WQ Daily Range=0
WQ Daily Time=0
WQ Create Restart=0
WQ Fixed Restart=0
WQ System Summary=0
WQ Write To DSS=0
WQ Use Fixed Temperature=0
Sorting and Armoring Iterations= 10
XS Update Threshold= 0.02
Bed Roughness Predictor= 0
Hydraulics Update Threshold= 0.02
Energy Slope Method= 1
Volume Change Method= 1
Sediment Retention Method= 0
XS Weighting Method= 0
Number of US Weighted Cross Sections= 1
Number of DS Weighted Cross Sections= 1
Upstream XS Weight=0
Main XS Weight=1
Downstream XS Weight=0
Number of DS XS's Weighted with US Boundary= 1
Upstream Boundary Weight= 1
Weight of XSs Associated with US Boundary= 0
Number of US XS's Weighted with DS Boundary= 1
Downstream Boundary Weight= 0.5
Weight of XSs Associated with DS Boundary= 0.5
Percentile Method= 0
Sediment Output Level= 4
Mass or Volume Output= 0
Output Increment Type= 1
Profile and TS Output Increment= 1
XS Output Flag= 0
XS Output Increment= 10
Write Gradation File= 0
Read Gradation Hotstart= 0
Write HDF5 File= 1
Write Binary Output= 1
Write DSS Sediment File= 0
SV Curve= 0
Specific Gage Flag= 0

--- CheatRiver.f01 (steady flow) ---

Flow Title=CheatRiver_flow
Program Version=5.05
Number of Profiles= 1
Profile Names=100yr
River Rch & RM=Bull Run,1               ,640.08
 49.6956
River Rch & RM=Bull Run,1               ,91.39324
 49.6956
River Rch & RM=Cheat River,3               ,16642.08
 2959.39
River Rch & RM=Cheat River,3               ,13533.12
  2978.2
River Rch & RM=Cheat River,2               ,13441.68
 3022.77
River Rch & RM=Cheat River,2               ,6766.56
 3015.57
River Rch & RM=Cheat River,1               ,6675.12
 3053.26
River Rch & RM=Cheat River,1               ,91.44003
 3058.59
River Rch & RM=LeftForkBullRun,1               ,2103.476
   14.64
River Rch & RM=LeftForkBullRun,1               ,1097.636
 16.1404
River Rch & RM=LeftForkBullRun,1               ,68.75242
 17.6412
River Rch & RM=Licking Creek,1               ,7406.623
   14.64
River Rch & RM=Licking Creek,1               ,6400.8
 16.0272
River Rch & RM=Licking Creek,1               ,5760.72
 17.7262
River Rch & RM=Licking Creek,1               ,4845.997
   19.68
River Rch & RM=Licking Creek,1               ,4206.232
 22.5966
River Rch & RM=Licking Creek,1               ,3566.16
 26.0513
River Rch & RM=Licking Creek,1               ,3200.4
 29.6758
River Rch & RM=Licking Creek,1               ,2834.627
 30.1288
River Rch & RM=Licking Creek,1               ,1463.014
 34.1781
River Rch & RM=Licking Creek,1               ,914.405
 36.5001
River Rch & RM=Licking Creek,1               ,91.43999
 37.6894
River Rch & RM=R Fork Bull Run,1               ,3566.16
   14.64
River Rch & RM=R Fork Bull Run,1               ,2911.74
 15.3759
River Rch & RM=R Fork Bull Run,1               ,2194.56
 24.3806
River Rch & RM=R Fork Bull Run,1               ,1188.7
 25.5982
River Rch & RM=R Fork Bull Run,1               ,640.08
  30.497
River Rch & RM=R Fork Bull Run,1               ,365.7601
 31.9411
River Rch & RM=R Fork Bull Run,1               ,91.44
 32.0544
Boundary for River Rch & Prof#=Bull Run,1               , 1
Up Type= 0
Dn Type= 0
Boundary for River Rch & Prof#=Cheat River,3               , 1
Up Type= 1
Up Known WS=1543
Dn Type= 0
Boundary for River Rch & Prof#=Cheat River,2               , 1
Up Type= 0
Dn Type= 0
Boundary for River Rch & Prof#=Cheat River,1               , 1
Up Type= 0
Dn Type= 3
Dn Slope=0.0123
Boundary for River Rch & Prof#=LeftForkBullRun,1               , 1
Up Type= 2
Dn Type= 0
Boundary for River Rch & Prof#=Licking Creek,1               , 1
Up Type= 2
Dn Type= 0
Boundary for River Rch & Prof#=R Fork Bull Run,1               , 1
Up Type= 2
Dn Type= 0
DSS Import GetInterval= 0
DSS Import GetPeak= 0
DSS Import FillOption= 0

--- CheatRiver.g01 (geometry) ---

Geom Title=CheatRiver_geometry
Program Version=5.05

Junct Name=1
Junct Desc=, 0 , 0 , 0 ,0
Up River,Reach=LeftForkBullRun ,1
Up River,Reach=R Fork Bull Run ,1
Dn River,Reach=Bull Run        ,1
Junc L&A=133,
Junc L&A=157,

Junct Name=2
Junct Desc=, 0 , 0 , 0 ,0
Up River,Reach=Bull Run        ,1
Up River,Reach=Cheat River     ,3
Dn River,Reach=Cheat River     ,2
Junc L&A=125,
Junc L&A=92,

Junct Name=5
Junct Desc=, 0 , 0 , 0 ,0
Up River,Reach=Cheat River     ,2
Up River,Reach=Licking Creek   ,1
Dn River,Reach=Cheat River     ,1
Junc L&A=92,
Junc L&A=153,

River Reach=LeftForkBullRun ,1
Reach XY= 30
     607532.5841    4338929.3389      607567.958    4338920.1127
     607633.4425    4338948.5554     607691.9817    4338931.0268
     607753.4974    4338927.7195     607793.4496    4338942.0069
     607925.5406    4338956.0377     607970.7869    4338979.3133
     608063.0605    4338972.6987     608124.2456    4338983.2821
     608179.1467    4338960.4617     608216.8499    4338959.1388
      608297.548    4338981.2977     608351.4569    4338973.6909
     608372.6237    4338996.1805     608498.9625    4339028.9228
     608589.9132    4339085.1469     608677.9014    4339120.1402
     608784.1805    4339131.1711     608807.5334    4339124.8344
     608841.9293    4339139.0558608927.5405247374339142.44529134
608982.4271532344339196.48037081     609019.5312    4339250.5118
609125.1497979154339340.66305427609205.0149785034339441.67349123
     609222.1584      4339487.59     609285.7687    4339529.9785
     609313.2193    4339529.6477     609341.4219    4339545.2405

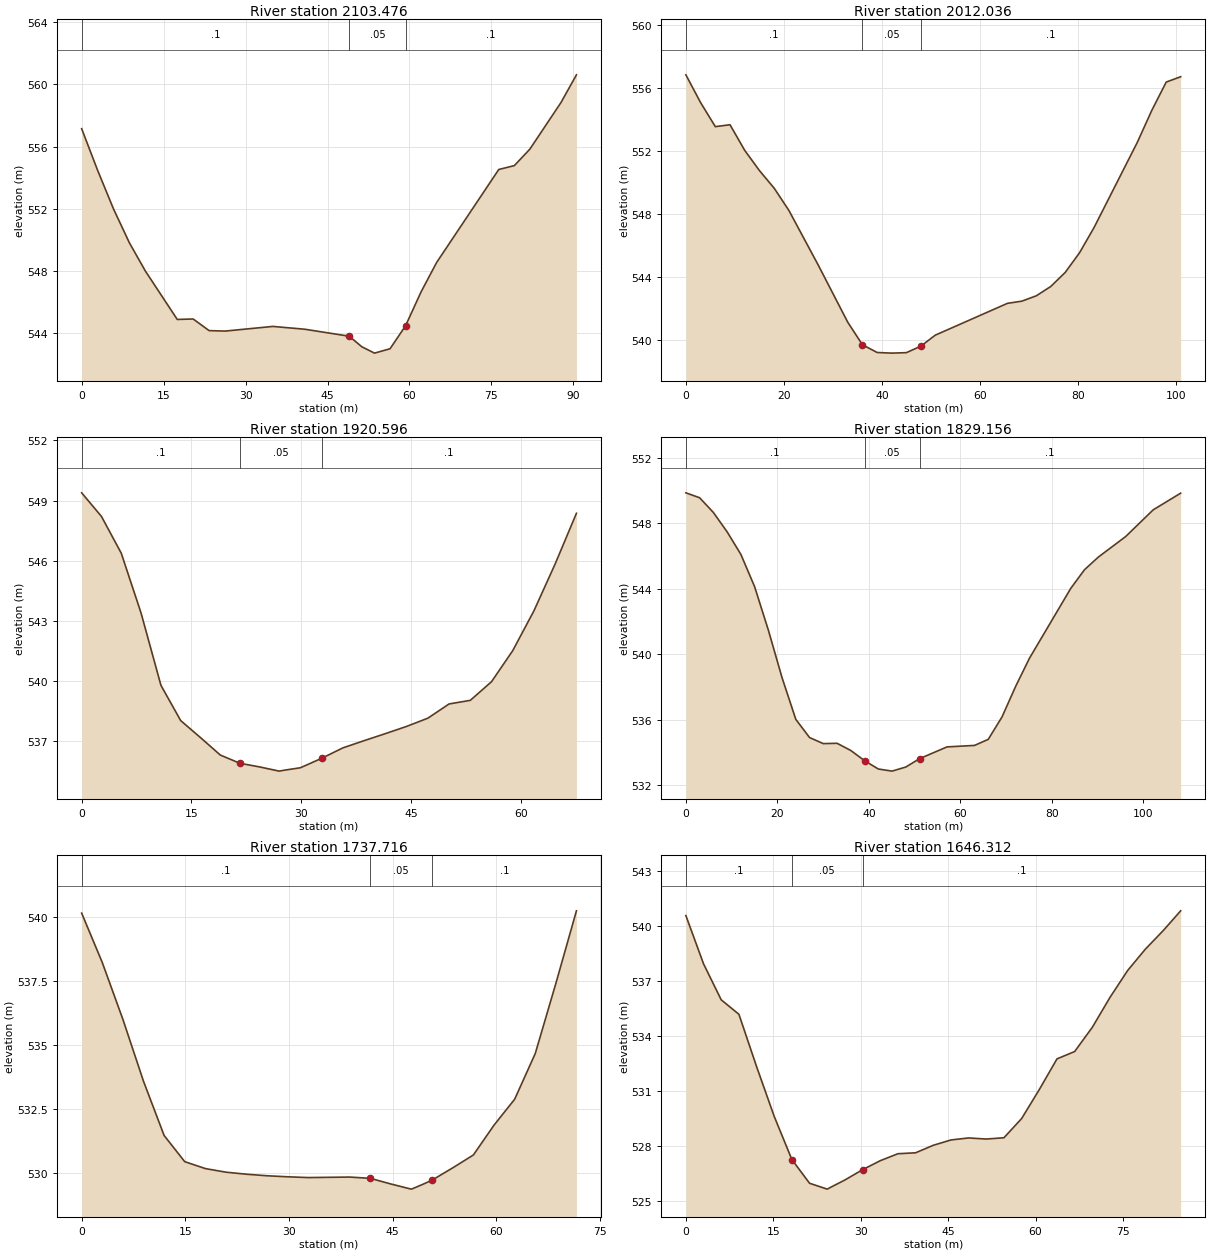
Type RM Length L Ch R = 1 ,2103.476,85.27,91.44,88.18
XS GIS Cut Line= 4
     607561.7846    4338975.0234     607554.2118    4338928.9835
     607552.3619    4338922.2951     607545.4048    4338885.9955
#Sta/Elev= 23
       0  557.15    2.92  554.47    5.83  551.98    8.75  549.79   11.66  547.98
    17.5  544.86   20.41  544.89   23.33  544.14   26.25  544.11   34.99  544.41
   40.83  544.23   48.97  543.78   51.28   543.1    53.6  542.69   56.44  542.97
   59.28  544.45   62.13  546.64   64.97  548.53   76.34  554.52   79.19  554.77
   82.03  555.83   87.72  558.83   90.56  560.62
#Mann= 3 , 0 , 0
       0      .1       0   48.97     .05       0   59.28      .1       0
Bank Sta=48.97,59.28
XS Rating Curve= 0 ,0
Exp/Cntr=0.3,0.1

Type RM Length L Ch R = 1 ,2012.036,90.32,91.44,93.41
XS GIS Cut Line= 3
     607646.9736    4338984.7311     607633.1865    4338944.9915
     607624.4272     4338886.701
#Sta/Elev= 27
       0  556.84       3  555.08    6.01  553.55    9.01  553.67   12.02  552.04
   15.02  550.76   18.03  549.64   21.03  548.23   27.04  544.75   33.05  541.13
   36.05   539.7   39.06  539.21   42.06  539.17   45.01   539.2   47.96  539.61
   50.91  540.31   65.64  542.33   68.59  542.47   71.54  542.81   74.48   543.4
   77.43  544.29   80.38  545.55   83.32  547.14   92.17  552.56   95.11  554.58
   98.06  556.38  101.01  556.72
#Mann= 3 , 0 , 0
       0      .1       0   36.05     .05       0   47.96      .1       0
Bank Sta=36.05,47.96
XS Rating Curve= 0 ,0
Exp/Cntr=0.3,0.1

Type RM Length L Ch R = 1 ,1920.596,89.5,91.44,90.78
XS GIS Cut Line= 4
     607722.0913    4338959.4005     607721.8998    4338940.4556
     607723.1948    4338932.5179     607722.8592    4338891.9185
#Sta/Elev= 27
       0  549.39    2.71  548.21    5.41  546.38    8.12  543.39   10.83  539.79
   13.53  538.03   16.24  537.18   18.95  536.31   21.63   535.9   24.31  535.72
   26.99  535.51   27.74  535.56   29.74  535.67   29.89  535.68   32.79  536.15
   35.69  536.67   38.59  537.03   41.49  537.38   44.39  537.74   47.29  538.15
   50.19  538.86   53.09  539.04   55.99  539.97   58.89  541.52   61.79  543.51
   64.69  545.85   67.59  548.37
#Mann= 3 , 0 , 0
       0      .1       0   21.63     .05       0   32.79      .1       0
Bank Sta=21.63,32.79
XS Rating Curve= 0 ,0
Exp/Cntr=0.3,0.1

Type RM Length L Ch R = 1 ,1829.156,91.87,91.44,92.45
XS GIS Cut Line= 2
      607803.695    4338987.3805     607819.5929    4338880.4041
#Sta/Elev= 30
       0  549.87       3  549.57    6.01  548.67    9.01  547.49   12.02  546.11
   15.02  544.14   18.03  541.48   21.03  538.57   24.03  536.03   27.04  534.92
   30.04  534.55   33.05  534.57   36.05  534.13   39.05  533.51   42.06     533
   45.06  532.87   48.07  533.12   51.07  533.63   57.08  534.35   63.09  534.44
   66.09  534.81    69.1  536.18    72.1  538.06   75.11  539.77   84.12  544.03
   87.12  545.17   90.13  545.94   96.13   547.2  102.14  548.83  108.15  549.85
#Mann= 3 , 0 , 0
       0      .1       0   39.05     .05       0   51.07      .1       0
Bank Sta=39.05,51.07
XS Rating Curve= 0 ,0
Exp/Cntr=0.3,0.1

Type RM Length L Ch R = 1 ,1737.716,88.11,91.4,88.58
XS GIS Cut Line= 2
     607895.1211    4339000.6625     607903.8215    4338929.6098
#Sta/Elev= 26
       0  540.14    2.98  538.22    5.97     536    8.95  533.59   11.93  531.48
   14.91  530.46    17.9  530.19   20.88  530.05   23.86  529.97   26.84  529.91
   29.83  529.87   32.81  529.84   38.77  529.86   41.76  529.81   44.74  529.59
   47.38  529.41   47.72  529.39   49.38  529.58    50.7  529.74   53.69  530.22
   56.67  530.72   59.65  531.88   62.64  532.89   65.62  534.67    68.6   537.4
   71.58  540.23
#Mann= 3 , 0 , 0
       0      .1       0   41.76     .05       0    50.7      .1       0
Bank Sta=41.76,50.7
XS Rating Curve= 0 ,0
Exp/Cntr=0.3,0.1

Type RM Length L Ch R = 1 ,1646.312,90.8,91.48,92.66
XS GIS Cut Line= 2
     607985.3654    4339002.9391     607981.7394    4338918.1245
#Sta/Elev= 30
       0  540.55    3.03  537.92    6.06  535.96     9.1  535.17   12.13  532.32
   15.16   529.6   18.19  527.25   21.22  525.96   24.25  525.64   25.21   525.8
   27.29  526.14   30.32   526.7   33.35  527.19   36.38  527.57   39.41  527.62
   42.45  528.03   45.48  528.32   48.51  528.43   51.54  528.37   54.57  528.44
   57.61  529.49   60.64  531.07   63.67  532.74    66.7  533.14   69.73  534.46
   72.76  536.09    75.8  537.56   78.83  538.72   81.86  539.72   84.89  540.81
#Mann= 3 , 0 , 0
       0      .1       0   18.19     .05       0   30.32      .1       0
Bank Sta=18.19,30.32
XS Rating Curve= 0 ,0
Exp/Cntr=0.3,0.1

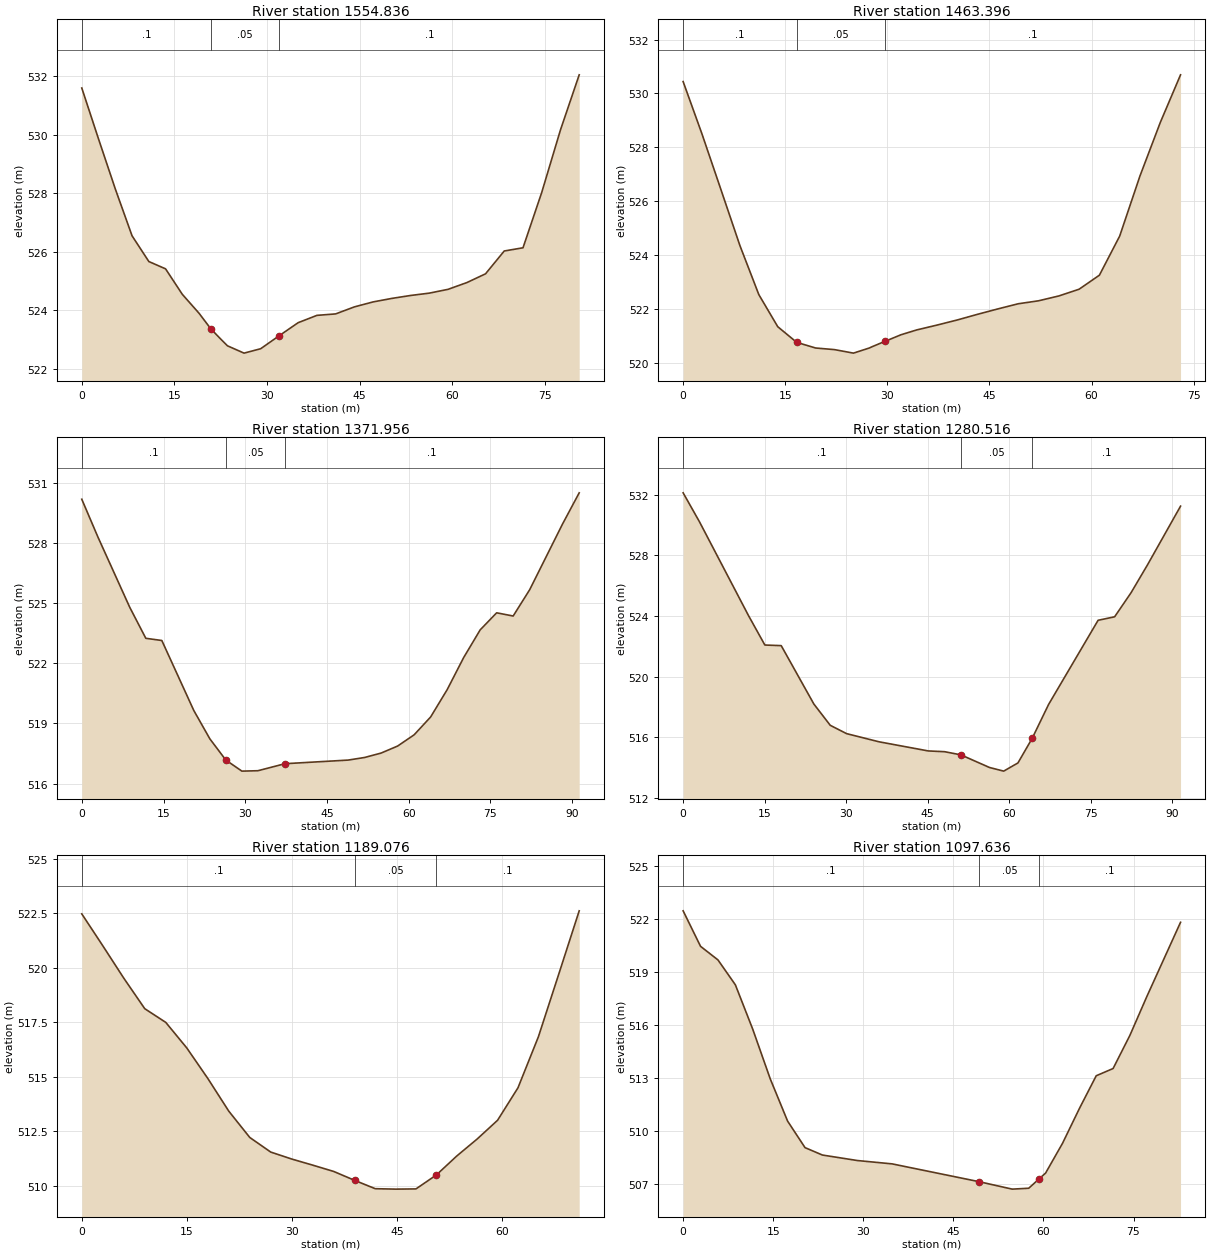
Type RM Length L Ch R = 1 ,1554.836,91.93,91.44,85.09
XS GIS Cut Line= 5
     608073.7523    4338995.1724     608075.1513    4338976.2256
     608075.4675    4338974.3536     608076.1143    4338966.3039
     608076.1115    4338914.7127
#Sta/Elev= 30
       0  531.59    2.71  529.85    5.43  528.14    8.14  526.54   10.86  525.66
   13.57  525.41   16.28  524.54      19  523.89    20.9  523.36   22.55     523
   23.59  522.78   26.28  522.53   28.97  522.68   32.01  523.13   35.04  523.57
   38.08  523.82   41.11  523.87   44.15  524.11   47.18  524.28   50.22   524.4
   53.25   524.5   56.29  524.58   59.32  524.71   62.36  524.94   65.39  525.24
   68.42  526.02   71.46  526.13   74.49  528.02   77.53  530.16   80.56  532.04
#Mann= 3 , 0 , 0
       0      .1       0    20.9     .05       0   32.01      .1       0
Bank Sta=20.9,32.01
XS Rating Curve= 0 ,0
Exp/Cntr=0.3,0.1

Type RM Length L Ch R = 1 ,1463.396,86.44,91.44,96.31
XS GIS Cut Line= 4
     608170.0657    4338994.3262     608163.5225    4338970.1748
     608160.2875    4338961.4639     608149.7099    4338924.1744
#Sta/Elev= 29
       0  530.44    2.78  528.49    5.56  526.43    8.34  524.36   11.12  522.54
    13.9  521.35   16.68  520.77   19.46  520.56   22.24   520.5   25.02  520.37
   27.35  520.56   27.69   520.6   29.67  520.81   29.69  520.81   31.99  521.05
   34.31  521.23    37.3  521.41   40.28   521.6   43.26  521.81   46.24  522.01
   49.22   522.2    52.2  522.31   55.19  522.49   58.17  522.74   61.15  523.26
   64.13  524.71   67.11  526.94   70.09  528.92   73.07  530.69
#Mann= 3 , 0 , 0
       0      .1       0   16.68     .05       0   29.69      .1       0
Bank Sta=16.68,29.69
XS Rating Curve= 0 ,0
Exp/Cntr=0.3,0.1

Type RM Length L Ch R = 1 ,1371.956,90.81,91.44,92.11
XS GIS Cut Line= 4
     608241.0464     4339005.854     608249.0981    4338974.5576
     608251.9261    4338967.6447      608266.237    4338918.1771
#Sta/Elev= 25
       0  530.17    2.94   528.3    8.81  524.78   11.75  523.24   14.69  523.13
   20.56  519.64    23.5  518.23   26.44  517.17   29.38  516.62   32.32  516.64
   37.29  516.99   48.87  517.17    51.9   517.3   54.93  517.52   57.96  517.87
   60.99  518.43   64.02  519.32   67.05  520.68   70.08  522.28   73.11  523.66
   76.13  524.51   79.16  524.35   82.19  525.66   88.25  528.95   91.28  530.49
#Mann= 3 , 0 , 0
       0      .1       0   26.44     .05       0   37.29      .1       0
Bank Sta=26.44,37.29
XS Rating Curve= 0 ,0
Exp/Cntr=0.3,0.1

Type RM Length L Ch R = 1 ,1280.516,84.01,91.44,103.84
XS GIS Cut Line= 4
     608333.6142    4339031.1399     608338.4717    4338980.2379
      608338.731    4338967.1462     608341.6976    4338940.0053
#Sta/Elev= 22
       0  532.12    3.01  530.21   12.03  524.03   15.04  522.09   18.05  522.05
   24.06   518.2   27.07   516.8   30.08  516.25   36.09  515.71   45.12  515.11
   48.13  515.06   51.13  514.85   56.37  514.02   58.99  513.78   61.61  514.32
   64.23  515.94   67.26  518.18   76.36  523.72    79.4  523.95   82.43  525.54
   85.46  527.38   91.53  531.24
#Mann= 3 , 0 , 0
       0      .1       0   51.13     .05       0   64.23      .1       0
Bank Sta=51.13,64.23
XS Rating Curve= 0 ,0
Exp/Cntr=0.3,0.1

Type RM Length L Ch R = 1 ,1189.076,89.34,91.44,92.78
XS GIS Cut Line= 3
     608402.6327    4339045.8894     608416.8588    4339009.6494
     608426.3538    4338979.0799
#Sta/Elev= 26
       0  522.48    2.99  521.02    5.99  519.53    8.98  518.13   11.98   517.5
   14.97  516.33   17.97  514.93   20.96  513.43   23.96  512.22   26.95  511.55
   29.95  511.23   32.94  510.95   35.94  510.66   38.93  510.25   41.62   509.9
   41.84  509.87   44.75  509.85   47.66  509.86   50.57   510.5   53.48  511.37
   56.39  512.15    59.3  513.01   62.21   514.5   65.12  516.84   68.03  519.72
   70.94  522.62
#Mann= 3 , 0 , 0
       0      .1       0   38.93     .05       0   50.57      .1       0
Bank Sta=38.93,50.57
XS Rating Curve= 0 ,0
Exp/Cntr=0.3,0.1

Type RM Length L Ch R = 1 ,1097.636,90.69,91.44,91.27
XS GIS Cut Line= 4
     608481.3781     4339083.101     608501.9678     4339038.311
     608506.1076    4339031.1665      608520.907    4339010.6757
#Sta/Elev= 23
       0  522.45     2.9  520.44     5.8  519.67     8.7  518.26    11.6  515.74
    14.5  512.94    17.4  510.54    20.3  509.04    23.2  508.62      29  508.31
    34.8  508.12    49.3  507.11    54.8  506.69   57.55  506.74   59.34  507.29
   60.36   507.6   63.17  509.28   65.98  511.25   68.79  513.11    71.6  513.52
    74.4   515.4   77.21  517.59   82.83   521.8
#Mann= 3 , 0 , 0
       0      .1       0    49.3     .05       0   59.34      .1       0
Bank Sta=49.3,59.34
XS Rating Curve= 0 ,0
Exp/Cntr=0.3,0.1

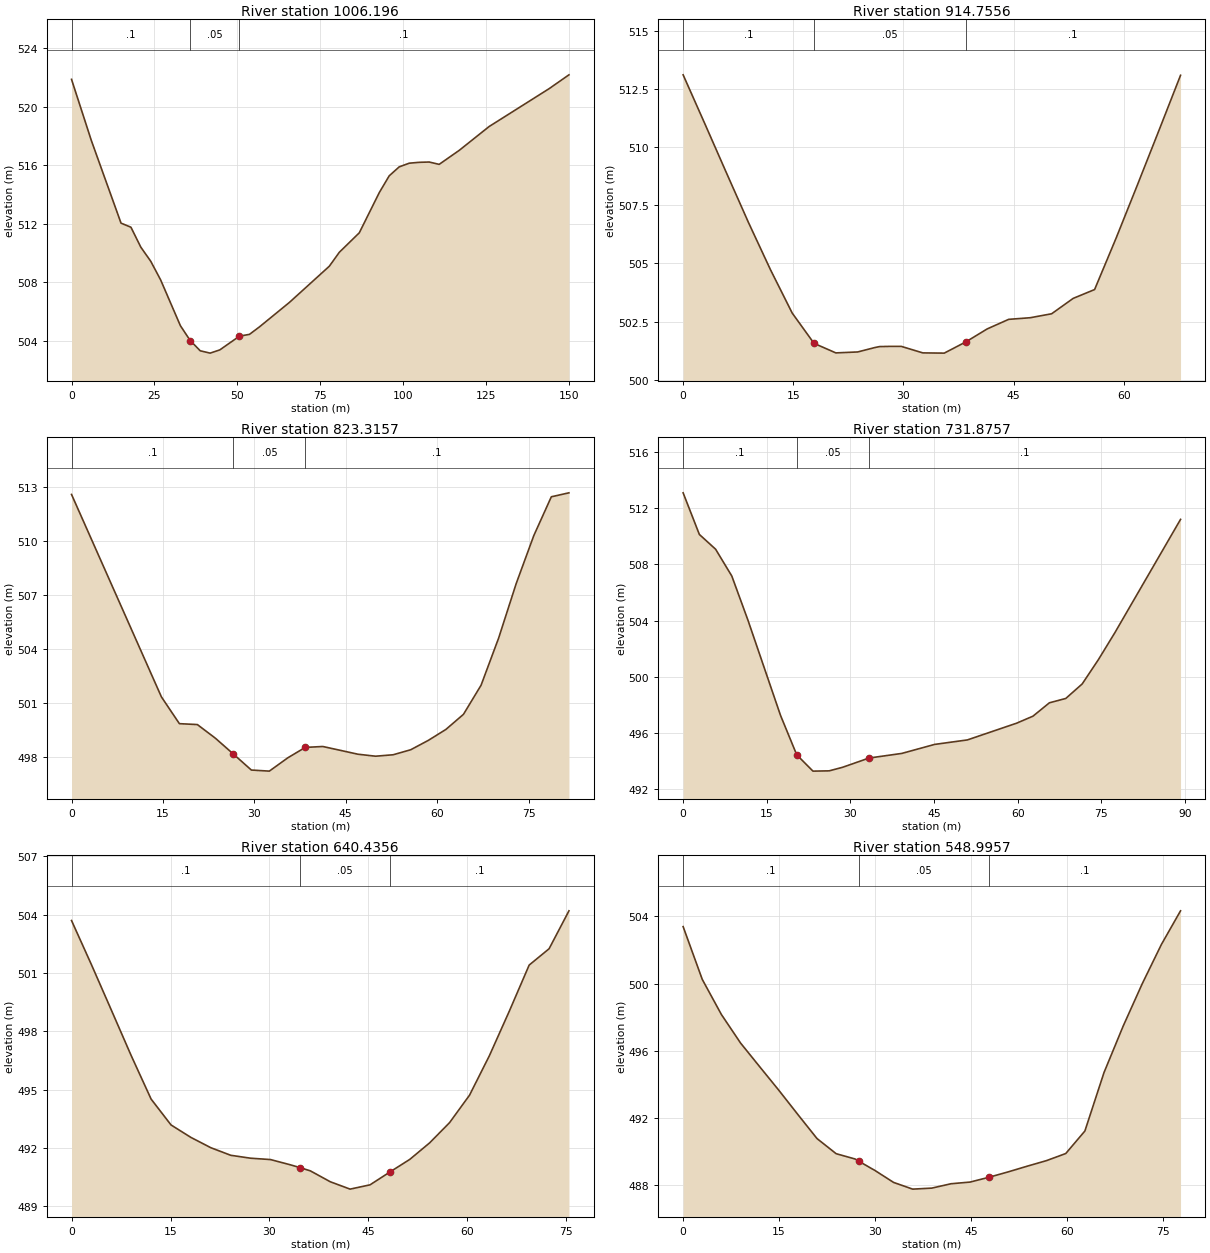
Type RM Length L Ch R = 1 ,1006.196,93.88,91.44,88.3
XS GIS Cut Line= 4
     608563.0457    4339118.6692     608582.0118    4339081.4173
     608585.7441    4339076.9216     608617.7064    4338979.6402
#Sta/Elev= 30
       0  521.86    5.97  517.69   14.93  512.05   17.92  511.77    20.9  510.41
   23.89  509.45   26.87  508.18   32.84  505.05   35.83  504.03   38.82  503.34
    41.8  503.18   44.72   503.4   50.66  504.34   53.67  504.46   56.68  504.97
   65.72  506.64   77.76  509.11   80.77  510.06    86.8  511.39   92.82  514.13
   95.83  515.28   98.84  515.89  101.86  516.14  104.87   516.2  107.88  516.22
  110.89  516.06  116.91  517.01  125.95  518.64  144.02  521.22  150.04  522.17
#Mann= 3 , 0 , 0
       0      .1       0   35.83     .05       0   50.66      .1       0
Bank Sta=35.83,50.66
XS Rating Curve= 0 ,0
Exp/Cntr=0.3,0.1

Type RM Length L Ch R = 1 ,914.7556,92.15,91.44,89.45
XS GIS Cut Line= 3
     608656.4499    4339142.6452     608664.9783    4339114.1926
     608679.7754     4339079.175
#Sta/Elev= 26
       0   513.1    2.97  510.99    5.94  508.86    8.91  506.75   11.88  504.74
   14.85  502.87   17.82  501.57   20.79  501.16   23.76   501.2   26.11  501.39
   26.73  501.43   28.11  501.44    29.7  501.44   32.63  501.16   35.55  501.15
   38.48  501.63    41.4  502.19   44.32   502.6   47.25  502.67   50.17  502.84
    53.1   503.5   56.02  503.88   58.95  506.09   61.87  508.39   64.79  510.72
   67.72  513.08
#Mann= 3 , 0 , 0
       0      .1       0   17.82     .05       0   38.48      .1       0
Bank Sta=17.82,38.48
XS Rating Curve= 0 ,0
Exp/Cntr=0.3,0.1

Type RM Length L Ch R = 1 ,823.3157,89.82,91.44,90.47
XS GIS Cut Line= 3
      608751.436    4339162.7054     608755.0704    4339124.5188
     608757.0218     4339081.294
#Sta/Elev= 24
       0  512.58   14.75  501.32    17.7  499.83   20.65  499.78   23.61  499.02
   26.56  498.14   29.51  497.25   32.46  497.19   35.49  497.93   38.36  498.51
   41.24  498.56   47.01  498.13    49.9  498.02   52.78   498.1   55.67  498.38
   58.55   498.9   61.44  499.51   64.32  500.35   67.21  501.97   70.09  504.59
   72.97  507.62   75.86  510.29   78.74  512.45   81.63  512.67
#Mann= 3 , 0 , 0
       0      .1       0   26.56     .05       0   38.36      .1       0
Bank Sta=26.56,38.36
XS Rating Curve= 0 ,0
Exp/Cntr=0.3,0.1

Type RM Length L Ch R = 1 ,731.8757,87.54,91.44,92.44
XS GIS Cut Line= 4
     608838.2251    4339167.6165     608842.2548    4339141.7396
     608842.4888    4339134.6035     608855.3147    4339080.2356
#Sta/Elev= 22
       0  513.09    2.91  510.13    5.82  509.08    8.73  507.17   11.64  504.01
   17.46  497.26   20.37  494.45   23.28  493.29   26.19  493.31   28.57  493.56
   33.33  494.22   39.21  494.55   45.09  495.19   50.97  495.51   59.79   496.7
   62.73   497.2   65.67  498.15   68.61  498.46   71.55  499.49   74.49  501.24
   77.43  503.15   89.19   511.2
#Mann= 3 , 0 , 0
       0      .1       0   20.37     .05       0   33.33      .1       0
Bank Sta=20.37,33.33
XS Rating Curve= 0 ,0
Exp/Cntr=0.3,0.1

Type RM Length L Ch R = 1 ,640.4356,82.09,91.44,83.37
XS GIS Cut Line= 2
     608911.7415    4339179.9998     608951.4816    4339115.9294
#Sta/Elev= 28
       0  503.69    3.02  501.42    6.03  499.09    9.05  496.74   12.06  494.51
   15.08  493.18   18.09  492.54   21.11  492.01   24.13  491.62   27.14  491.47
   30.16   491.4   33.17  491.13   34.68  490.98   36.19  490.82   36.68  490.73
   39.21  490.26   42.22  489.88   45.24   490.1   48.25  490.76   51.27  491.41
   54.28  492.26    57.3   493.3   60.32  494.71   63.33  496.74   66.35  499.03
   69.36   501.4   72.38  502.24   75.39  504.19
#Mann= 3 , 0 , 0
       0      .1       0   34.68     .05       0   48.25      .1       0
Bank Sta=34.68,48.25
XS Rating Curve= 0 ,0
Exp/Cntr=0.3,0.1

Type RM Length L Ch R = 1 ,548.9957,85.49,91.44,88.05
XS GIS Cut Line= 2
     608960.0061    4339231.2133     609017.1935    4339178.4822
#Sta/Elev= 29
       0  503.39    2.99  500.25    5.98  498.16    8.98  496.46   11.97  495.05
   14.96  493.65   17.95   492.2   20.94  490.77   23.93  489.87   26.93  489.55
   27.49  489.42   29.49  488.98   29.92  488.89   32.91  488.16    35.9  487.76
   38.89  487.82   41.89  488.08   44.88  488.18   47.87  488.47   50.86  488.79
   53.85  489.13   56.85  489.46   59.84  489.88   62.83  491.22   65.82   494.7
   68.81  497.46    71.8  499.99    74.8  502.33   77.79  504.33
#Mann= 3 , 0 , 0
       0      .1       0   27.49     .05       0   47.87      .1       0
Bank Sta=27.49,47.87
XS Rating Curve= 0 ,0
Exp/Cntr=0.3,0.1

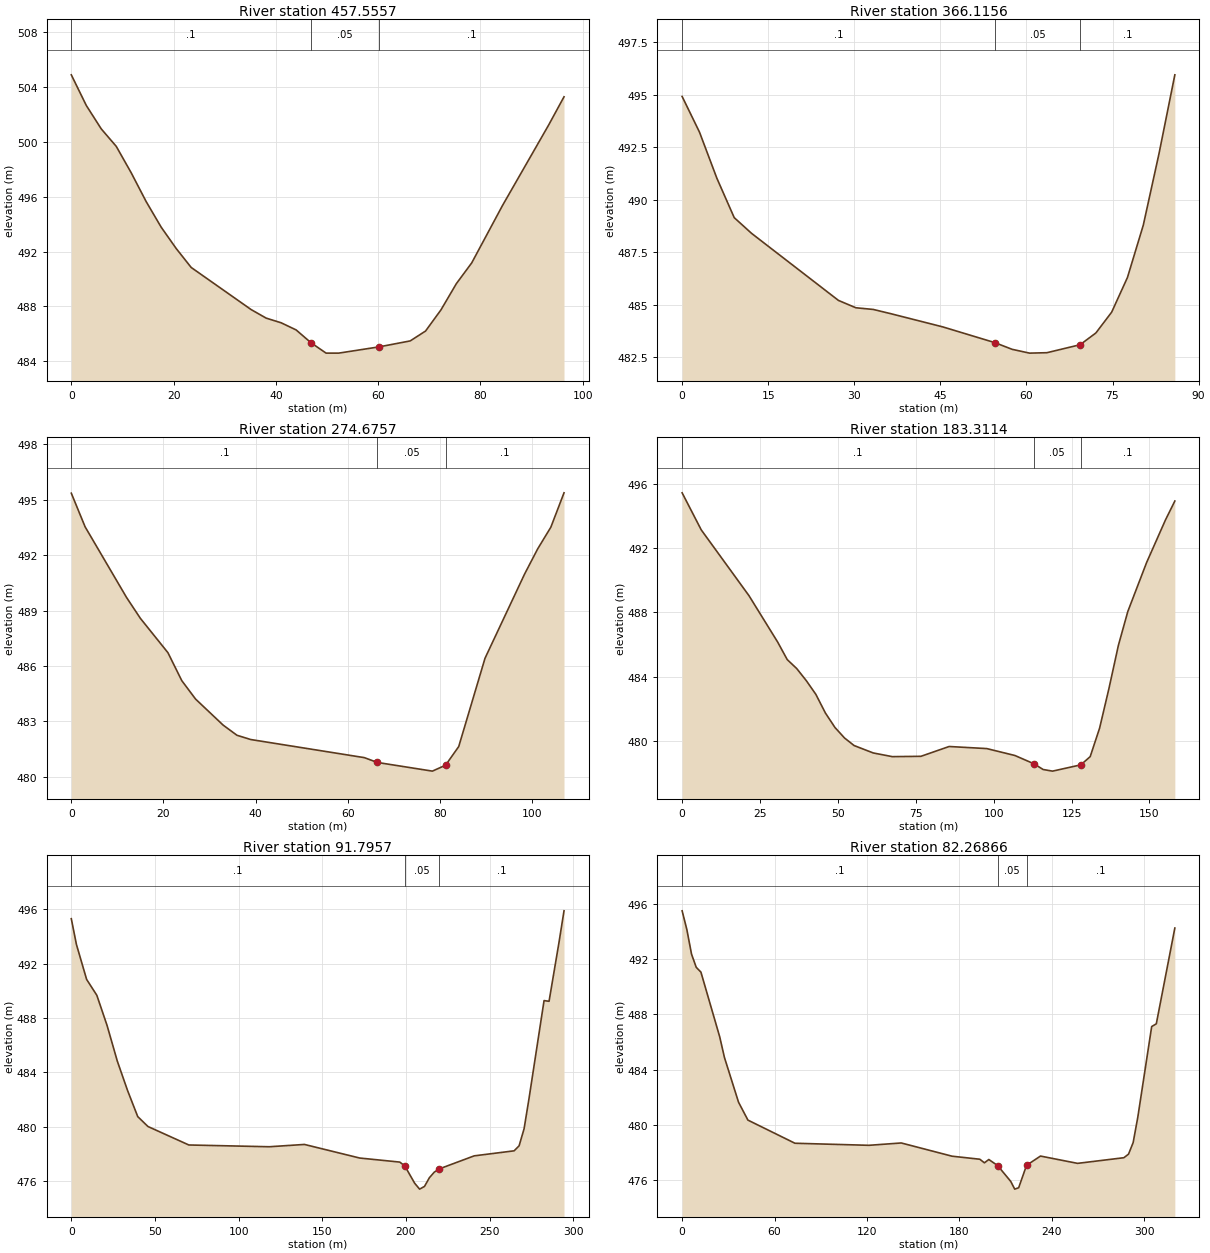
Type RM Length L Ch R = 1 ,457.5557,90.92,91.44,87.78
XS GIS Cut Line= 4
     608998.9067    4339295.4487      609039.169    4339266.1064
     609046.1536    4339263.5919     609079.0766    4339242.5082
#Sta/Elev= 25
       0  504.87    2.93  502.64    5.86  500.93    8.79  499.66   11.72  497.73
   14.65  495.63   17.58  493.77   20.51  492.22   23.44  490.84   35.17  487.77
    38.1  487.15   41.03  486.81   43.96  486.29   46.89  485.35   49.82   484.6
   52.29   484.6   60.25  485.06   66.27  485.49   69.27  486.21   72.28  487.75
   75.29  489.66   78.29  491.17   84.31  495.35   93.33  501.21   96.34  503.27
#Mann= 3 , 0 , 0
       0      .1       0   46.89     .05       0   60.25      .1       0
Bank Sta=46.89,60.25
XS Rating Curve= 0 ,0
Exp/Cntr=0.3,0.1

Type RM Length L Ch R = 1 ,366.1156,73.53,91.44,90.43
XS GIS Cut Line= 3
      609064.225    4339367.1699     609111.3167    4339320.0782
     609127.0501    4339308.9671
#Sta/Elev= 21
       0  494.91    3.03  493.21    6.05  491.02    9.08  489.14   12.11  488.39
   27.24   485.2   30.27  484.85    33.3  484.77   36.33  484.57   45.41  483.94
   54.49  483.19   57.52  482.87   60.54  482.69   63.57  482.71   69.35  483.09
    72.1  483.65   74.85  484.64    77.6  486.29   80.36  488.78   83.11   492.2
   85.86  495.94
#Mann= 3 , 0 , 0
       0      .1       0   54.49     .05       0   69.35      .1       0
Bank Sta=54.49,69.35
XS Rating Curve= 0 ,0
Exp/Cntr=0.3,0.1

Type RM Length L Ch R = 1 ,274.6757,85.59,91.36,81.71
XS GIS Cut Line= 6
     609084.0884    4339409.9991     609131.4774    4339391.2771
       609143.86    4339388.5784     609152.2813    4339389.0388
     609155.7555    4339388.8537     609186.7469    4339383.5407
#Sta/Elev= 20
       0  495.35       3  493.53   11.99  489.71   14.99  488.58   20.98  486.72
   23.98  485.21   26.98  484.21   32.97   482.8   35.97  482.25   38.96  482.02
   63.63  481.04   66.44  480.78    78.4  480.31   81.26  480.63   84.12  481.64
   89.83  486.42   98.41  490.97  101.27  492.34  104.12  493.51  106.98  495.37
#Mann= 3 , 0 , 0
       0      .1       0   66.44     .05       0   81.26      .1       0
Bank Sta=66.44,81.26
XS Rating Curve= 0 ,0
Exp/Cntr=0.3,0.1

Type RM Length L Ch R = 1 ,183.3114,104.19,91.52,83.08
XS GIS Cut Line= 3
     609096.2592    4339443.3367     609168.8035    4339468.0859
     609239.1345    4339426.9325
#Sta/Elev= 30
       0  495.43    6.13  493.13   21.46  489.04   30.66  486.16   33.73  485.07
   36.79  484.51   39.86  483.76   42.92  482.91   45.99  481.75   49.06  480.85
   52.12   480.2   55.19  479.73   61.32  479.27   67.45  479.04   76.65  479.06
    85.7  479.67   97.78  479.54  106.83  479.11  112.87   478.6  115.88  478.24
   118.9  478.14  127.96  478.53  130.97  479.04  133.99  480.81  137.01  483.29
  140.03  485.96  143.05  488.06  149.08   491.1  155.12  493.74  158.14  494.92
#Mann= 3 , 0 , 0
       0      .1       0  112.87     .05       0  127.96      .1       0
Bank Sta=112.87,127.96
XS Rating Curve= 0 ,0
Exp/Cntr=0.3,0.1

Type RM Length L Ch R = 1 ,91.7957 ,2.13,9.53,16.8
XS GIS Cut Line= 6
     609077.2162    4339454.4369     609143.5489    4339492.2827
      609255.166    4339527.2644     609259.2674    4339519.2671
     609262.4965    4339504.9918     609276.2084    4339428.6746
#Sta/Elev= 30
       0  495.32    3.05  493.43    9.16  490.85   15.27  489.68   21.38  487.46
   27.49  484.84    33.6  482.68   39.71  480.75   45.82  480.02   70.26  478.66
  118.36  478.53  139.35   478.7  172.35   477.7  196.34   477.4  199.33  477.12
  205.26  475.84  208.18  475.41  211.11  475.61  214.04  476.25  216.96  476.66
  219.95   476.9  240.82  477.86  264.68  478.23  267.66   478.6  270.64  479.86
  273.63  482.12  282.57  489.29  285.56  489.24  291.52  493.59   294.5   495.9
#Mann= 3 , 0 , 0
       0      .1       0  199.33     .05       0  219.95      .1       0
Bank Sta=199.33,219.95
XS Rating Curve= 0 ,0
Exp/Cntr=0.3,0.1

Type RM Length L Ch R = 1 ,82.26866,11.85,13.52,16.43
XS GIS Cut Line= 6
     609073.1132    4339456.4448      609140.419    4339492.4075
     609254.8095    4339528.6398     609273.5949    4339510.3835
     609277.2991    4339510.1189     609310.5721    4339423.7575
#Sta/Elev= 30
       0  495.52    3.05  494.17     6.1  492.38    9.16  491.42   12.21  491.07
   24.42  486.37   27.47  484.88   36.63  481.63   42.73  480.33   73.26  478.65
  121.31   478.5  142.31  478.67   175.3  477.71   193.3  477.49   196.3  477.23
  199.17  477.47  204.89  477.03  213.41  475.88  215.98  475.32  218.55  475.42
  223.68  477.05  232.72  477.72  256.79  477.19  286.88   477.6  289.89  477.86
   292.9   478.7   295.9  480.53  304.93  487.12  307.94  487.32  319.97  494.27
#Mann= 3 , 0 , 0
       0      .1       0  204.89     .05       0  223.68      .1       0
Bank Sta=204.89,223.68
XS Rating Curve= 0 ,0
Exp/Cntr=0.3,0.1

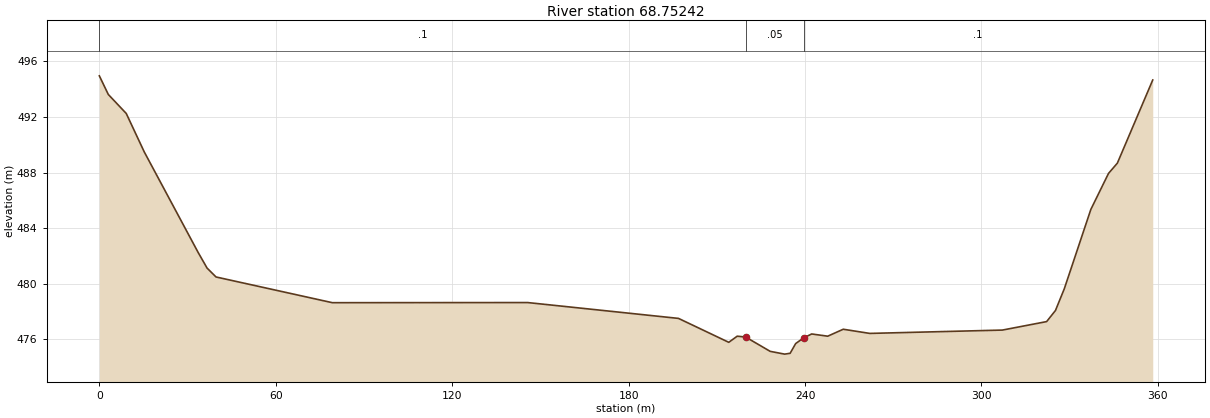
Type RM Length L Ch R = 1 ,68.75242,38.75,68.75,51.51
XS GIS Cut Line= 6
     609066.8601     4339460.328      609127.014    4339490.2298
     609267.5095    4339532.6085     609282.3262    4339518.5856
     609292.9095    4339515.9397     609340.7347    4339416.3491
#Sta/Elev= 30
       0  494.96    3.05  493.62    9.16  492.25   15.27  489.49   33.59  482.26
   36.64  481.13   39.69  480.49   79.25  478.64  145.65  478.65  196.97  477.51
  214.07  475.79  216.94  476.23   219.8  476.17  228.15  475.14  233.07  474.94
  234.94     475  236.82   475.7  239.54  476.11  242.27  476.39  247.72  476.23
     253  476.73  262.02  476.43  307.13  476.67  322.17  477.28  325.18  478.08
  328.18  479.64  337.21  485.35  343.22  487.94  346.23  488.68  358.26  494.66
#Mann= 3 , 0 , 0
       0      .1       0   219.8     .05       0  239.54      .1       0
Bank Sta=219.8,239.54
XS Rating Curve= 0 ,0
Exp/Cntr=0.3,0.1

River Reach=R Fork Bull Run ,1
Reach XY= 30
     606371.6494    4341059.0505606428.1118858984341060.25366482
     606462.6001    4341005.1415     606532.0533    4340951.2326
     606631.9337    4340921.7976     606681.2125    4340797.7739
     606727.1839    4340765.3624     606765.6836    4340699.6174
     606931.9057    4340555.6797     606939.2086    4340513.9211
     606983.0129    4340486.2025 607061.578067294340379.30419743
     607121.9195    4340341.0121     607142.1945    4340297.1311
607239.9567765994340259.23262194     607266.3861    4340219.1338
     607377.9044    4340135.6288     607551.5375    4340122.3996
     607635.0373    4340145.9054608005.3016082884340027.01110364
     608087.8064    4339977.8947     608160.2363    4339971.9415
608262.7646023434339929.56729426     608404.4897    4339806.2219
608646.5672183074339638.67426729     608705.6915    4339642.8704
608746.1864497634339619.22654809     609094.8788    4339571.7584
     609160.5381    4339548.9141     609341.4219    4339545.2405

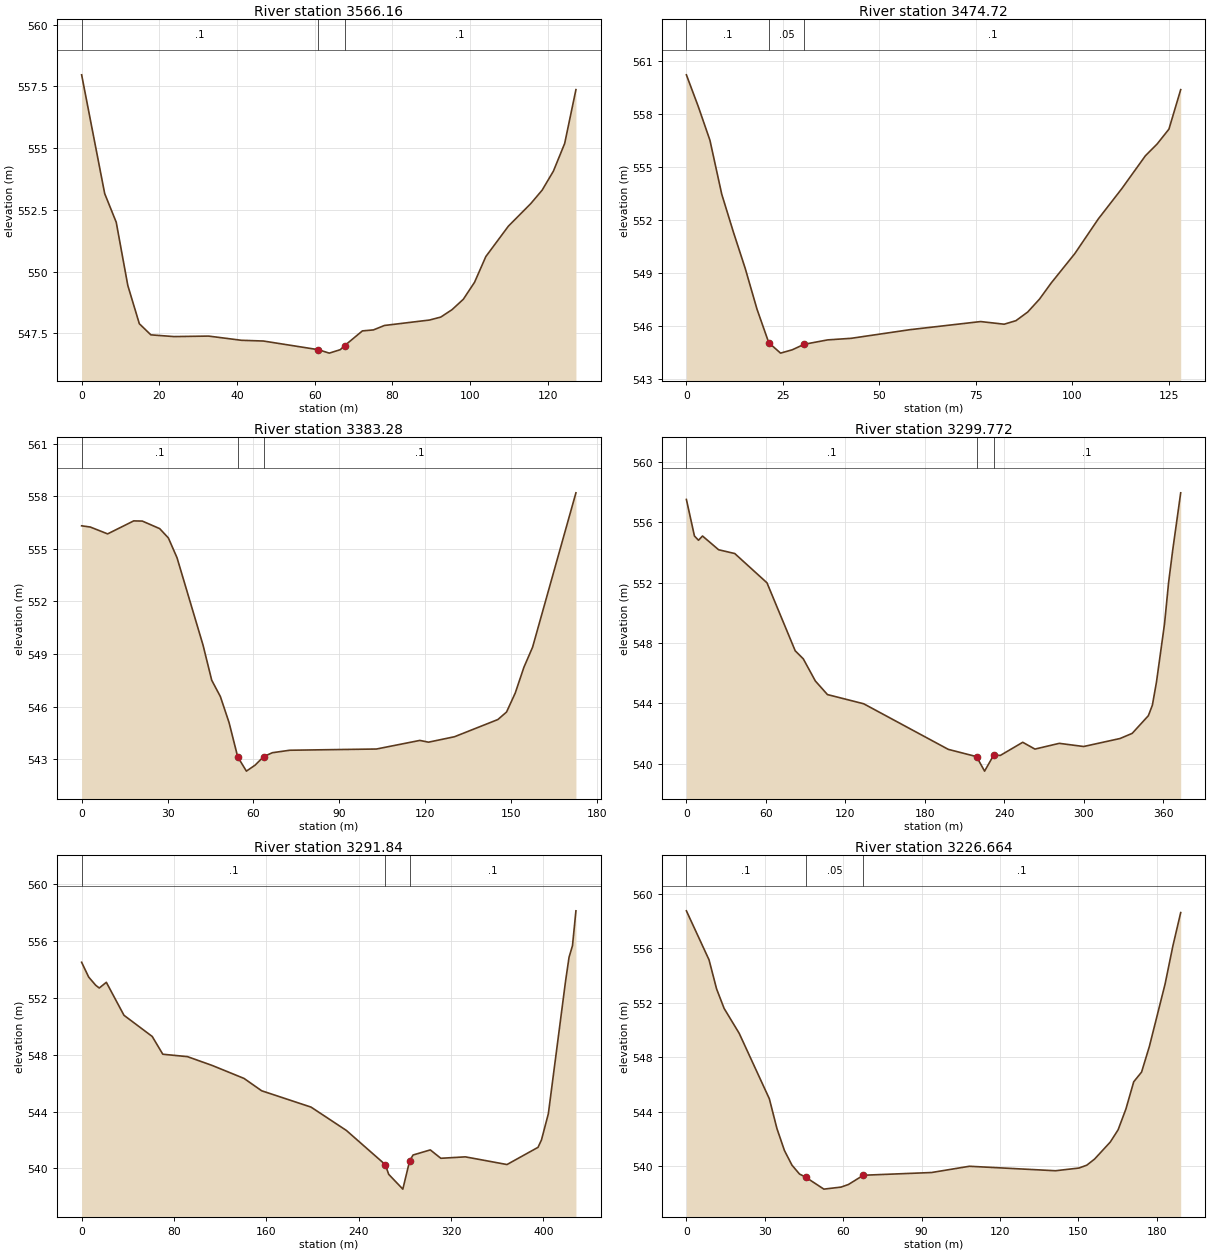
Type RM Length L Ch R = 1 ,3566.16 ,89.71,91.44,71.39
XS GIS Cut Line= 5
     606420.4458    4341106.2352     606397.4358    4341083.0216
     606391.9324    4341055.3371     606387.3131    4341038.9132
      606350.387    4341006.2476
#Sta/Elev= 29
       0  557.97    5.94  553.16    8.91     552   11.89  549.44   14.86  547.89
   17.83  547.44   23.77  547.37   32.69  547.39   41.15  547.22    46.8  547.19
   60.91  546.84   63.76   546.7    66.6  546.84   67.69     547   72.29   547.6
   75.13  547.64   77.97  547.82   89.57  548.04   92.47  548.16   95.37  548.46
   98.27  548.88  101.17  549.57  104.07  550.61  109.87  551.84  115.67  552.76
  118.57   553.3  121.47  554.07  124.37  555.19  127.27  557.37
#Mann= 3 , 0 , 0
       0      .1       0   60.91     .05       0   67.69      .1       0
Bank Sta=60.91,67.69
XS Rating Curve= 0 ,0
Exp/Cntr=0.3,0.1

Type RM Length L Ch R = 1 ,3474.72 ,91.37,91.44,95.7
XS GIS Cut Line= 2
     606476.9092    4341032.2338     606378.0952    4340950.7122
#Sta/Elev= 27
       0  560.23    3.05  558.45     6.1  556.52    9.15  553.47    12.2   551.3
   15.25  549.25    18.3  546.94   21.35  545.04    24.4  544.45   27.45  544.64
    30.5  544.95    36.6   545.2    42.7  545.29   57.95  545.78   76.25  546.24
   82.35  546.09    85.4  546.29   88.45  546.78    91.5  547.51   94.55  548.43
  100.65  550.09  106.75  552.06  112.85  553.78  118.95  555.64     122  556.31
  125.05  557.15   128.1  559.39
#Mann= 3 , 0 , 0
       0      .1       0   21.35     .05       0    30.5      .1       0
Bank Sta=21.35,30.5
XS Rating Curve= 0 ,0
Exp/Cntr=0.3,0.1

Type RM Length L Ch R = 1 ,3383.28 ,82.05,83.51,87.93
XS GIS Cut Line= 2
     606564.7961    4341003.5843     606454.3113    4340871.0018
#Sta/Elev= 28
       0  556.31    3.03  556.24    9.08  555.85   18.17  556.59   21.19  556.58
   27.25  556.15   30.28  555.62   33.31  554.49   42.39  549.51   45.42  547.51
   48.44  546.58   51.47   545.1    54.5  543.14   57.53  542.33   60.56  542.67
   63.58  543.16   66.61  543.38   72.67  543.52  102.94  543.59  118.08  544.08
  121.11  543.98  130.19  544.29  145.33  545.27  148.36   545.7  151.39  546.78
  154.42  548.25  157.44  549.39  172.58  558.19
#Mann= 3 , 0 , 0
       0      .1       0    54.5     .05       0   63.58      .1       0
Bank Sta=54.5,63.58
XS Rating Curve= 0 ,0
Exp/Cntr=0.3,0.1

Type RM Length L Ch R = 1 ,3299.772,8.58,7.93,9.33
XS GIS Cut Line= 6
     606625.2091    4341162.8573     606603.7713      4340935.68
     606602.5013     4340929.965     606591.7063    4340921.9216
     606577.5246    4340874.9315     606522.8181    4340821.7097
#Sta/Elev= 30
       0   557.5    6.09  555.08    9.13   554.8   12.17  555.08   24.34  554.17
   36.51  553.92   60.85  551.98   82.15  547.48   88.23  546.95   97.36  545.48
  106.49  544.58  133.87  543.97  197.76  540.95  219.06  540.47  225.14  539.51
  232.01  540.57  237.04  540.55  253.94  541.42  263.15  540.97  281.55  541.35
  299.94  541.14  327.42  541.67  336.58  542.01  348.79  543.18  351.84  543.88
   354.9   545.4     361  549.26  364.06  551.99  367.11   554.1  373.21  557.94
#Mann= 3 , 0 , 0
       0      .1       0  219.06     .05       0  232.01      .1       0
Bank Sta=219.06,232.01
XS Rating Curve= 0 ,0
Exp/Cntr=0.3,0.1

Type RM Length L Ch R = 1 ,3291.84 ,84.47,65.18,32.2
XS GIS Cut Line= 5
     606654.5779    4341209.9532     606612.0493    4340935.0383
     606600.5337     4340921.587     606587.6716    4340874.7059
     606531.4277    4340812.8604
#Sta/Elev= 30
       0   554.5    6.11  553.46   12.23  552.88   15.28  552.69    21.4  553.09
   36.68  550.77   61.14  549.28   70.31  548.03   91.71  547.86  113.11  547.24
  140.62  546.33  155.91  545.46   198.7  544.31  229.27  542.67   262.9  540.27
  265.96  539.58  278.18  538.54  284.09  540.53  287.04  540.94  301.97   541.3
  311.08  540.71  332.35  540.81  368.39  540.27  395.26  541.48  398.25     542
  404.22  543.85  419.14  553.19  422.13  554.85  425.12  555.67   428.1  558.12
#Mann= 3 , 0 , 0
       0      .1       0   262.9     .05       0  284.09      .1       0
Bank Sta=262.9,284.09
XS Rating Curve= 0 ,0
Exp/Cntr=0.3,0.1

Type RM Length L Ch R = 1 ,3226.664,14.16,13.24,7.5
XS GIS Cut Line= 6
     606692.0131    4340899.9133     606656.8495    4340874.6749
     606645.9354    4340883.6046      606640.313    4340883.6046
     606601.6176    4340863.7608     606551.3763    4340800.4247
#Sta/Elev= 30
       0  558.75    8.66  555.15   11.54  553.02   14.43  551.58    20.2  549.75
   31.74  544.94   34.63  542.76   37.51  541.14    40.4  540.06   43.28  539.41
   45.61  539.18    52.6   538.3   59.19  538.45      62  538.64   67.71  539.32
    93.8  539.52   108.3  539.98  141.23  539.65  150.21  539.85  153.21  540.06
   156.2  540.51  162.19  541.76  165.19  542.66  168.18  544.19  171.17  546.19
  174.17   546.9  177.16  548.79  183.15  553.36  186.15  556.17  189.14  558.62
#Mann= 3 , 0 , 0
       0      .1       0   45.61     .05       0   67.71      .1       0
Bank Sta=45.61,67.71
XS Rating Curve= 0 ,0
Exp/Cntr=0.3,0.1