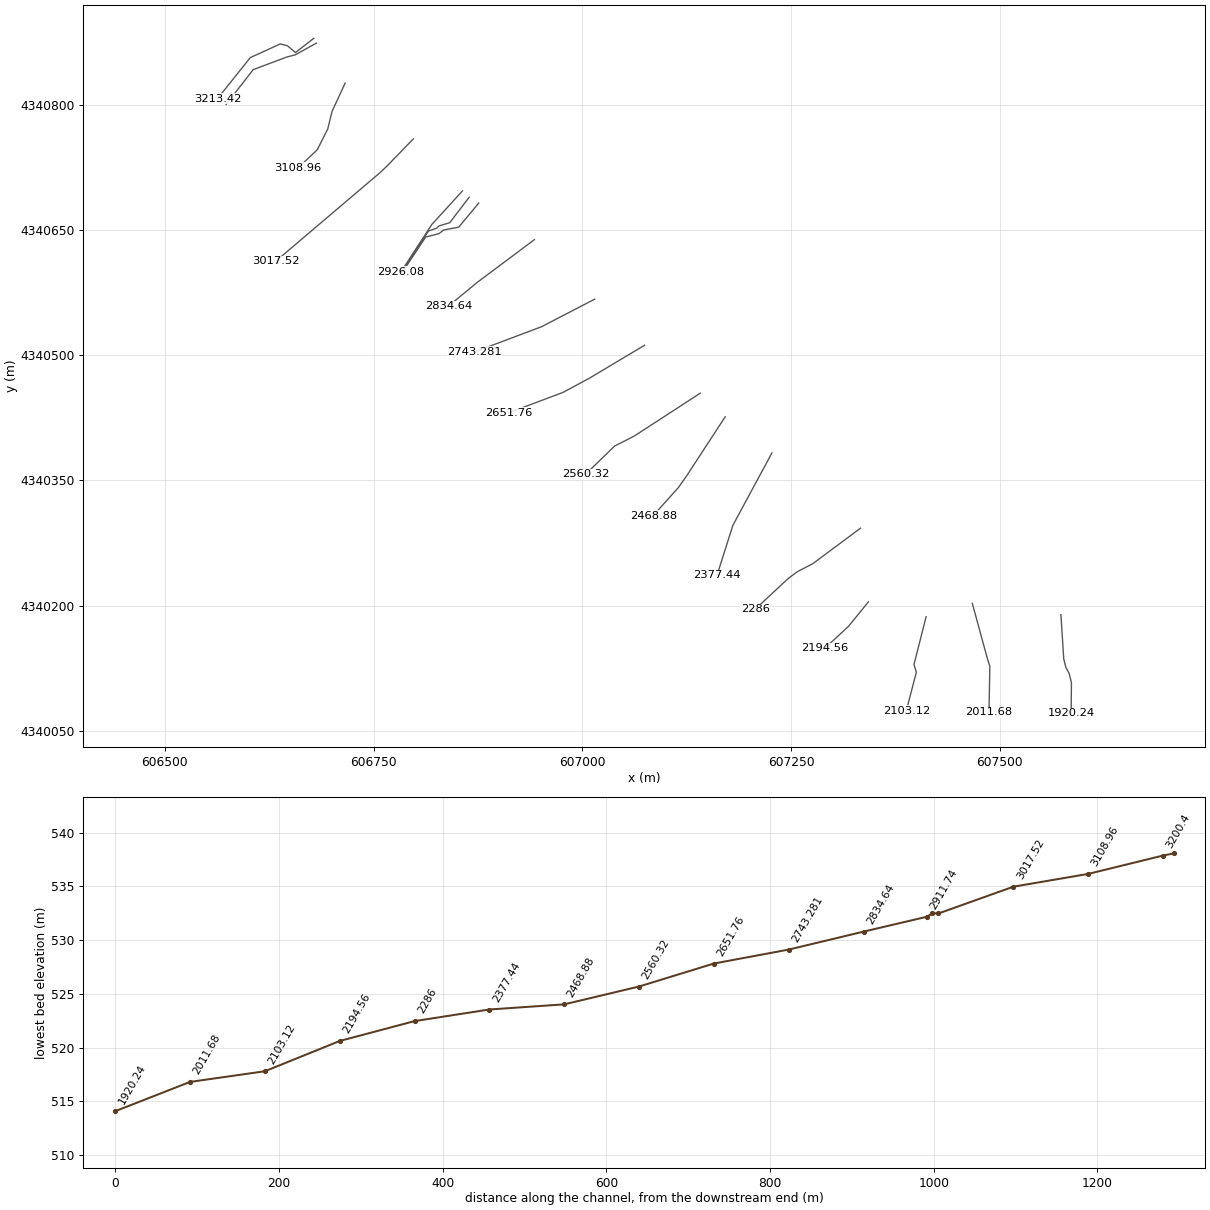
HEC-RAS study CheatRiver.prj: CheatRiver

--- CheatRiver.g01 (geometry) --- (continued)

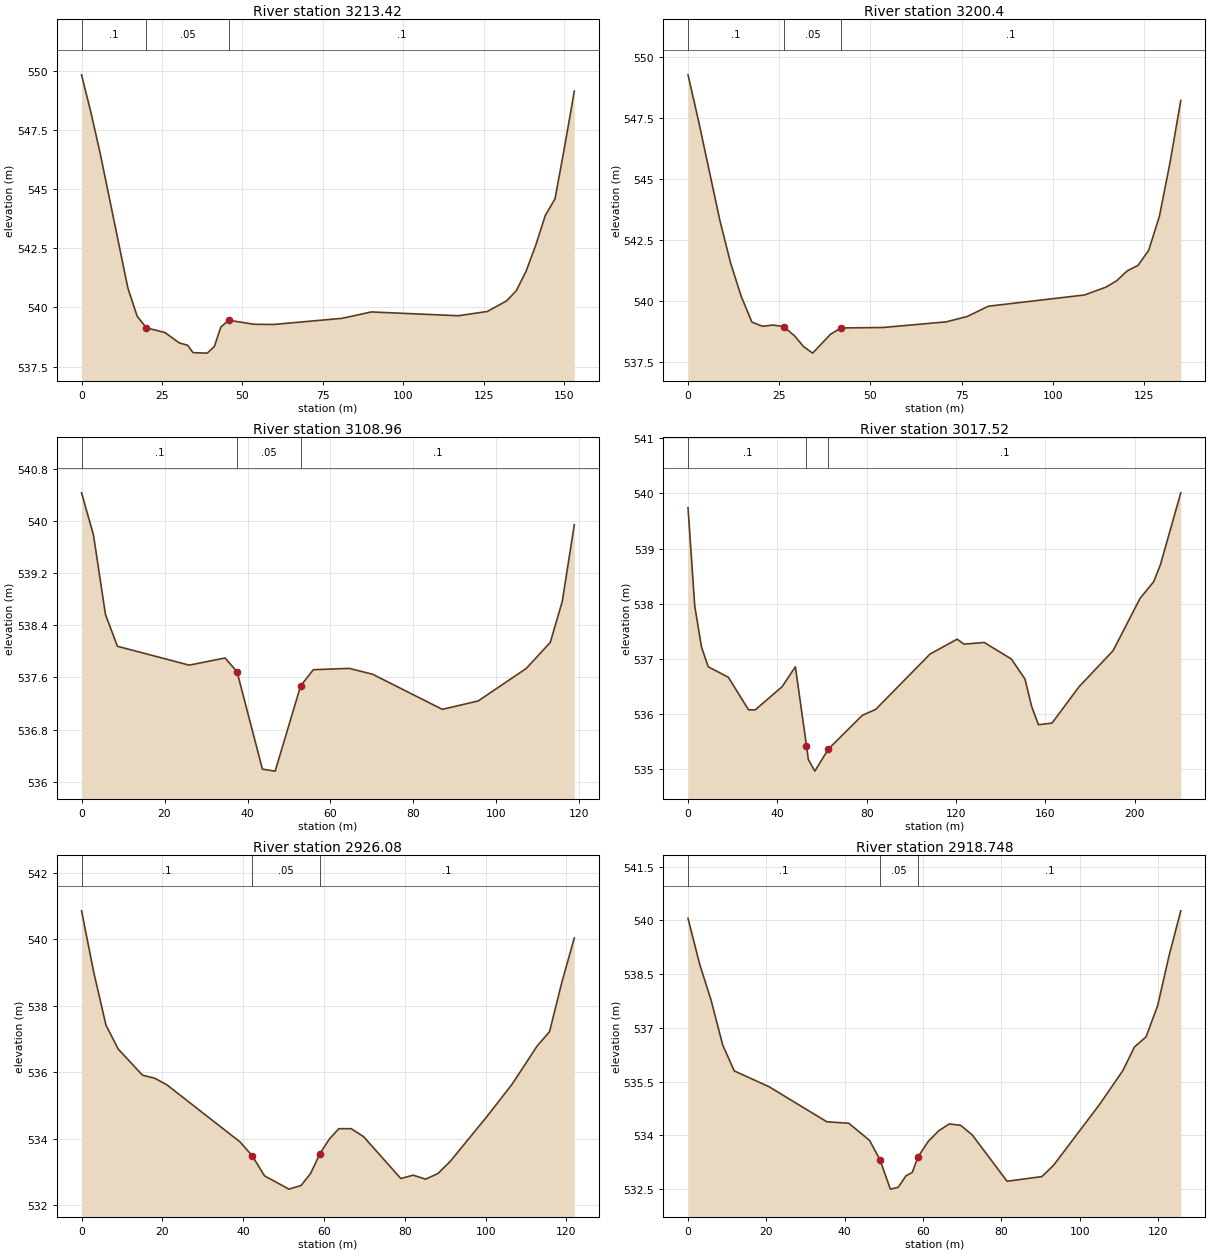
Type RM Length L Ch R = 1 ,3213.42 ,2.19,13.02,15.71
XS GIS Cut Line= 6
     606678.3741    4340879.4775     606656.4592     4340862.504
     606646.8284    4340870.5474     606638.2559    4340872.7699
     606602.2725    4340856.3657     606562.9252    4340807.0504
#Sta/Elev= 28
       0  549.83    2.88  548.26    5.76  546.53    14.4  540.82   17.28  539.63
   20.16  539.14   25.92  538.94   30.41   538.5   32.99   538.4   34.66  538.09
   39.07  538.07   41.28  538.35   43.29  539.17   45.73  539.46   53.56  539.29
   59.65  539.28   80.94  539.54   90.07  539.81   117.1  539.65  126.12  539.83
  132.12  540.28  135.13  540.71  138.13  541.52  141.14  542.62  144.14  543.89
  147.15  544.59  150.15   546.8  153.15  549.14
#Mann= 3 , 0 , 0
       0      .1       0   20.16     .05       0   45.73      .1       0
Bank Sta=20.16,45.73
XS Rating Curve= 0 ,0
Exp/Cntr=0.3,0.1

Type RM Length L Ch R = 1 ,3200.4  ,78.78,91.44,113.72
XS GIS Cut Line= 5
     606681.4332    4340873.7002     606655.9001    4340859.5824
     606646.2506      4340857.17     606605.8154    4340841.9703
     606573.3996    4340800.3415
#Sta/Elev= 27
       0  549.26    2.92  547.35    8.75  543.29   11.67  541.56   14.59  540.19
   17.51  539.14   20.42  538.97   23.34  539.02   26.26  538.95   29.18  538.58
   31.66  538.14   34.15  537.87   39.12  538.65      42   538.9   53.52  538.92
    70.8  539.15   76.56  539.37   82.32  539.79   108.7  540.25  114.56  540.57
  117.49  540.83  120.43  541.24  123.36  541.46  126.29  542.08  129.22  543.47
  132.15  545.68  135.08  548.21
#Mann= 3 , 0 , 0
       0      .1       0   26.26     .05       0      42      .1       0
Bank Sta=26.26,42
XS Rating Curve= 0 ,0
Exp/Cntr=0.3,0.1

Type RM Length L Ch R = 1 ,3108.96 ,98.16,91.44,78.75
XS GIS Cut Line= 5
     606715.9682    4340825.8783     606700.2181    4340791.8822
     606695.1436    4340771.0203     606682.5448    4340745.9925
     606659.3857    4340724.1877
#Sta/Elev= 19
       0  540.44    2.88  539.79    5.76  538.57    8.65  538.08   25.94  537.79
   34.59   537.9   37.47  537.69    43.6  536.19   46.67  536.16    52.8  537.47
   55.87  537.72   64.54  537.74   70.15  537.65   86.96  537.11   95.63  537.24
   107.2  537.74  112.98  538.14  115.87  538.77  118.77  539.95
#Mann= 3 , 0 , 0
       0      .1       0   37.47     .05       0    52.8      .1       0
Bank Sta=37.47,52.8
XS Rating Curve= 0 ,0
Exp/Cntr=0.3,0.1

Type RM Length L Ch R = 1 ,3017.52 ,89.45,91.44,97.38
XS GIS Cut Line= 4
     606797.5871    4340758.9895     606766.1527    4340726.5777
      606757.732    4340718.5779      606632.882    4340612.5559
#Sta/Elev= 30
       0  539.74    3.01  537.96    6.02  537.22    9.03  536.86   18.06  536.67
   27.09  536.08    30.1  536.08   42.14   536.5   48.06  536.86   53.03  535.43
   53.86  535.18   56.77  534.97   62.83  535.37      78  535.98   84.07  536.09
  108.33  537.09  120.46  537.36   123.5  537.27   132.6   537.3  144.73     537
   150.8  536.64  153.83  536.14  156.86  535.81  162.93  535.84  175.06   536.5
  190.23  537.15  202.36   538.1  208.43   538.4  211.46  538.71  220.56  540.01
#Mann= 3 , 0 , 0
       0      .1       0   53.03     .05       0   62.83      .1       0
Bank Sta=53.03,62.83
XS Rating Curve= 0 ,0
Exp/Cntr=0.3,0.1

Type RM Length L Ch R = 1 ,2926.08 ,14.32,7.33,0.95
XS GIS Cut Line= 4
     606856.4892    4340696.7572     606819.8699    4340656.6167
     606814.7397    4340648.8196     606782.9549    4340599.9756
#Sta/Elev= 29
       0  540.86    3.02  539.01    6.04  537.42    9.06   536.7   15.09  535.91
   18.11  535.82   21.13  535.62   39.24   533.9   42.26  533.48   45.28  532.88
   51.32  532.48   54.33  532.59   56.67  532.95      59  533.55   61.33  533.99
   63.67   534.3   66.74   534.3    69.8  534.06      79   532.8   82.07   532.9
   85.14  532.78    88.2  532.95   91.27  533.32  100.47  534.69  106.61  535.65
  112.74  536.79  115.81  537.22  118.88  538.72  121.94  540.04
#Mann= 3 , 0 , 0
       0      .1       0   42.26     .05       0      59      .1       0
Bank Sta=42.26,59
XS Rating Curve= 0 ,0
Exp/Cntr=0.3,0.1

Type RM Length L Ch R = 1 ,2918.748,11.67,7.01,1.09
XS GIS Cut Line= 6
     606864.5208    4340689.0901     606841.1933    4340658.6119
     606828.4933    4340654.8018     606825.5652    4340652.1031
     606815.8286    4340648.7164     606783.4895    4340599.2468
#Sta/Elev= 30
       0  540.06    2.95  538.79     5.9  537.77    8.86  536.52   11.81   535.8
   20.67  535.36   35.43  534.38   41.03  534.34   46.34  533.86   48.99  533.32
   51.64   532.5   53.63  532.55   55.62  532.87   57.25  532.97   58.69   533.4
   61.35  533.84      64  534.13   66.66  534.32   69.61  534.28   72.57  534.01
   81.43  532.72    90.3  532.85   93.25  533.16  105.07  534.87  110.98  535.81
  113.94  536.47  116.89  536.75  119.85  537.62   122.8  539.03  125.76  540.27
#Mann= 3 , 0 , 0
       0      .1       0   48.99     .05       0   58.69      .1       0
Bank Sta=48.99,58.69
XS Rating Curve= 0 ,0
Exp/Cntr=0.3,0.1

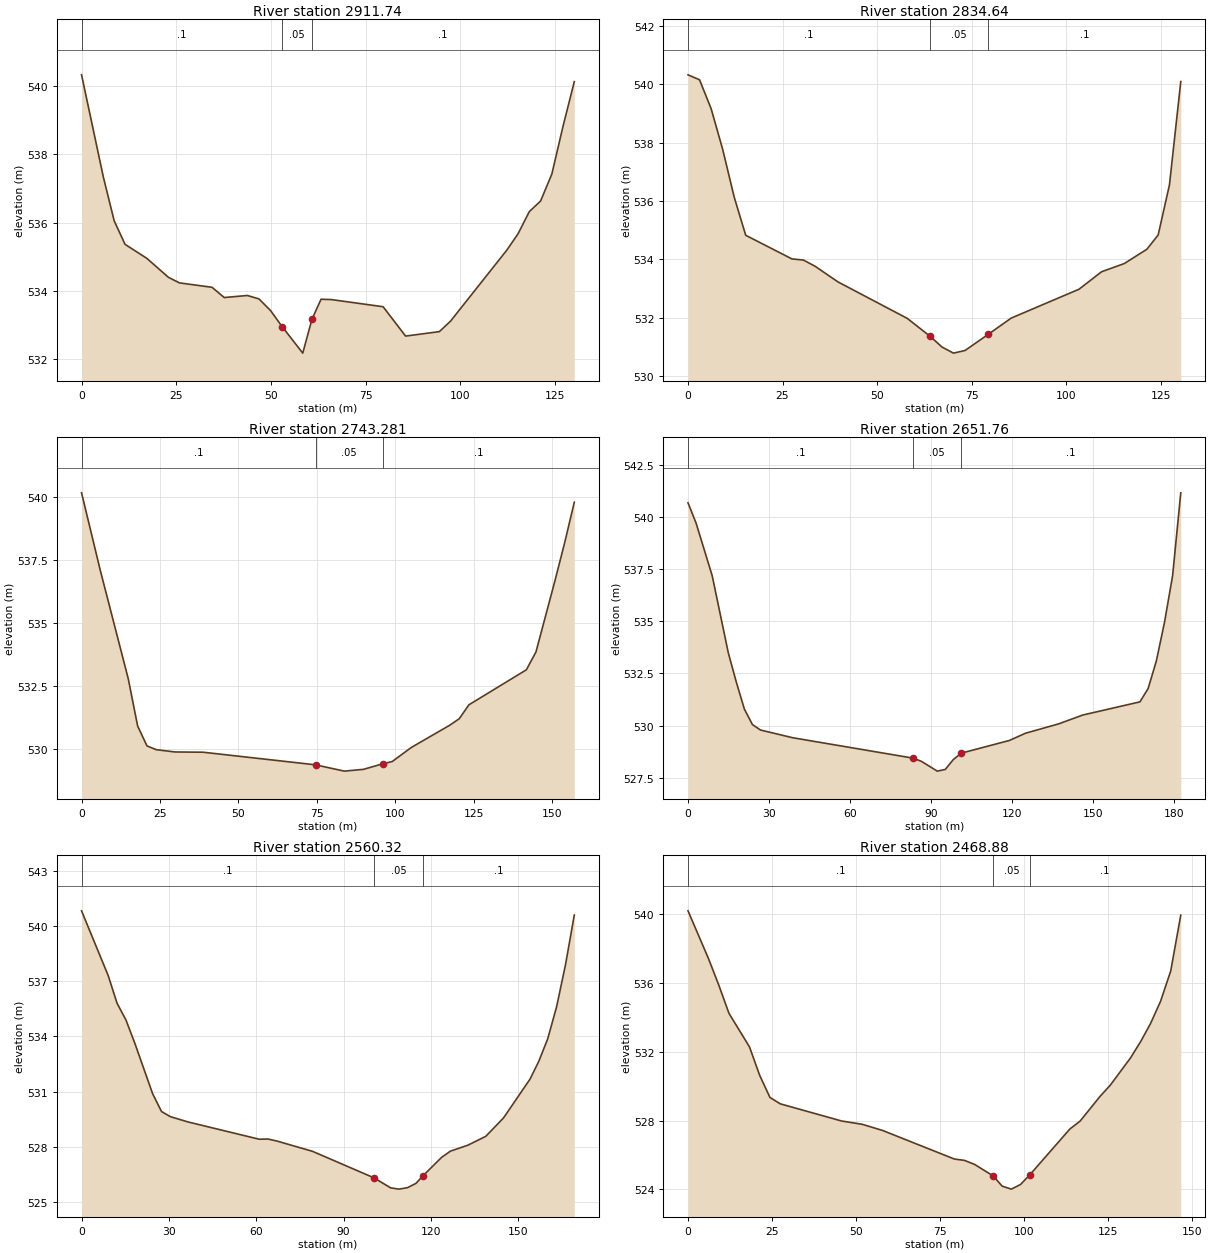
Type RM Length L Ch R = 1 ,2911.74 ,70.41,77.1,82.05
XS GIS Cut Line= 6
     606876.0014    4340682.1436     606851.9884    4340653.3202
     606833.9967    4340649.9335     606828.2816    4340645.4885
     606812.4066    4340641.4668     606784.5476     4340599.385
#Sta/Elev= 28
       0  540.33    5.74  537.34    8.61  536.05   11.48  535.36   17.22  534.95
   22.96  534.39   25.83  534.23   34.44   534.1   37.66   533.8   43.76  533.86
   46.82  533.76   49.87  533.42   52.92  532.95   58.38  532.17    60.8  533.16
   63.21  533.75   65.94  533.74   79.59  533.53   85.52  532.67   94.43   532.8
    97.4  533.11  112.24  535.19  115.21  535.67  118.18  536.32  121.15  536.63
  124.12  537.42  127.09  538.83  130.05  540.13
#Mann= 3 , 0 , 0
       0      .1       0   52.92     .05       0    60.8      .1       0
Bank Sta=52.92,60.8
XS Rating Curve= 0 ,0
Exp/Cntr=0.3,0.1

Type RM Length L Ch R = 1 ,2834.64 ,92.29,91.36,80.71
XS GIS Cut Line= 3
     606942.6325     4340638.343     606874.1784    4340587.1632
     606839.5901    4340558.6021
#Sta/Elev= 24
       0  540.33    3.05  540.16    6.11  539.17    9.16  537.78   12.21  536.14
   15.26  534.83   27.47  534.02   30.53  533.98   33.58  533.77   39.68  533.23
      58  531.98    64.1  531.36   67.16     531   70.21  530.79   73.26  530.88
   79.37  531.43   85.47  531.99  103.41  532.98  109.39  533.58  115.38  533.86
  121.36  534.35  124.35  534.84  127.34  536.56  130.33   540.1
#Mann= 3 , 0 , 0
       0      .1       0    64.1     .05       0   79.37      .1       0
Bank Sta=64.1,79.37
XS Rating Curve= 0 ,0
Exp/Cntr=0.3,0.1

Type RM Length L Ch R = 1 ,2743.281,85.69,91.52,89.67
XS GIS Cut Line= 3
     607014.8487    4340567.0387     606951.3905     4340534.115
     606871.3713     4340503.963
#Sta/Elev= 22
       0  540.16    5.96  537.09   14.89  532.78   17.87  530.91   20.85  530.12
   23.83  529.97   29.79  529.88   38.72  529.87   74.54  529.37   83.71  529.12
   89.81  529.19   95.92  529.41   98.98   529.5  105.08  530.06   117.3  530.94
  120.35   531.2  123.41  531.75  141.73  533.14  144.79  533.85  150.89   536.7
  153.95  538.19     157  539.79
#Mann= 3 , 0 , 0
       0      .1       0   74.54     .05       0   95.92      .1       0
Bank Sta=74.54,95.92
XS Rating Curve= 0 ,0
Exp/Cntr=0.3,0.1

Type RM Length L Ch R = 1 ,2651.76 ,89.27,91.44,96.45
XS GIS Cut Line= 4
      607074.608    4340511.8398     607008.0548    4340472.0925
     606976.8983    4340455.3516     606911.8526    4340430.9378
#Sta/Elev= 25
       0  540.68    2.98  539.71    8.94  537.19   14.91  533.49   17.89  532.08
   20.87  530.79   23.85  530.05   26.83  529.79   38.76  529.42   83.41  528.44
   86.36  528.29   92.26  527.82    95.2   527.9   98.15  528.37   101.1  528.68
  118.93  529.29  124.97  529.64  137.05  530.08  146.12  530.51  167.26  531.14
  170.28  531.78   173.3  533.09  176.32  534.94  179.34  537.19  182.36  541.16
#Mann= 3 , 0 , 0
       0      .1       0   83.41     .05       0   101.1      .1       0
Bank Sta=83.41,101.1
XS Rating Curve= 0 ,0
Exp/Cntr=0.3,0.1

Type RM Length L Ch R = 1 ,2560.32 ,74.56,91.44,92.39
XS GIS Cut Line= 4
     607141.2766    4340454.3914     607061.9575    4340402.8892
     607038.7442    4340391.1236     607003.8771    4340357.2358
#Sta/Elev= 30
       0  540.85    9.15  537.32    12.2  535.81   15.25   534.9    18.3  533.63
   24.41  530.88   27.46  529.91   30.51  529.63   36.61  529.34   61.01   528.4
   64.07  528.41   67.12   528.3   79.32  527.74  100.36   526.3  106.14  525.75
  109.03  525.68  111.92  525.76  114.81  525.99  117.29  526.41  123.64  527.41
  126.68  527.75  132.75  528.08  138.83  528.56  144.91  529.56  154.03  531.68
  157.06  532.66   160.1  533.88  163.14  535.62  166.18   537.9  169.22  540.62
#Mann= 3 , 0 , 0
       0      .1       0  100.36     .05       0  117.29      .1       0
Bank Sta=100.36,117.29
XS Rating Curve= 0 ,0
Exp/Cntr=0.3,0.1

Type RM Length L Ch R = 1 ,2468.88 ,80.63,91.44,90.43
XS GIS Cut Line= 4
     607171.2326    4340426.2165     607124.5384    4340354.6747
     607115.1006    4340341.3506     607085.0053     4340307.862
#Sta/Elev= 29
       0   540.2     6.1  537.42    9.15  535.89    12.2  534.24   18.31  532.29
   21.36  530.63   24.41  529.35   27.46  528.98   45.77  527.98   51.87  527.79
   57.97  527.43   79.33  525.77   82.38  525.69   85.43  525.45   90.87  524.79
    93.6  524.19   96.32  524.02   99.04  524.29  101.76  524.84  113.77  527.52
  116.77  527.97  122.77  529.42  125.77  530.06  131.78  531.64  134.78  532.58
  137.78  533.65  140.78  534.95  143.78   536.7  146.78  539.95
#Mann= 3 , 0 , 0
       0      .1       0   90.87     .05       0  101.76      .1       0
Bank Sta=90.87,101.76
XS Rating Curve= 0 ,0
Exp/Cntr=0.3,0.1

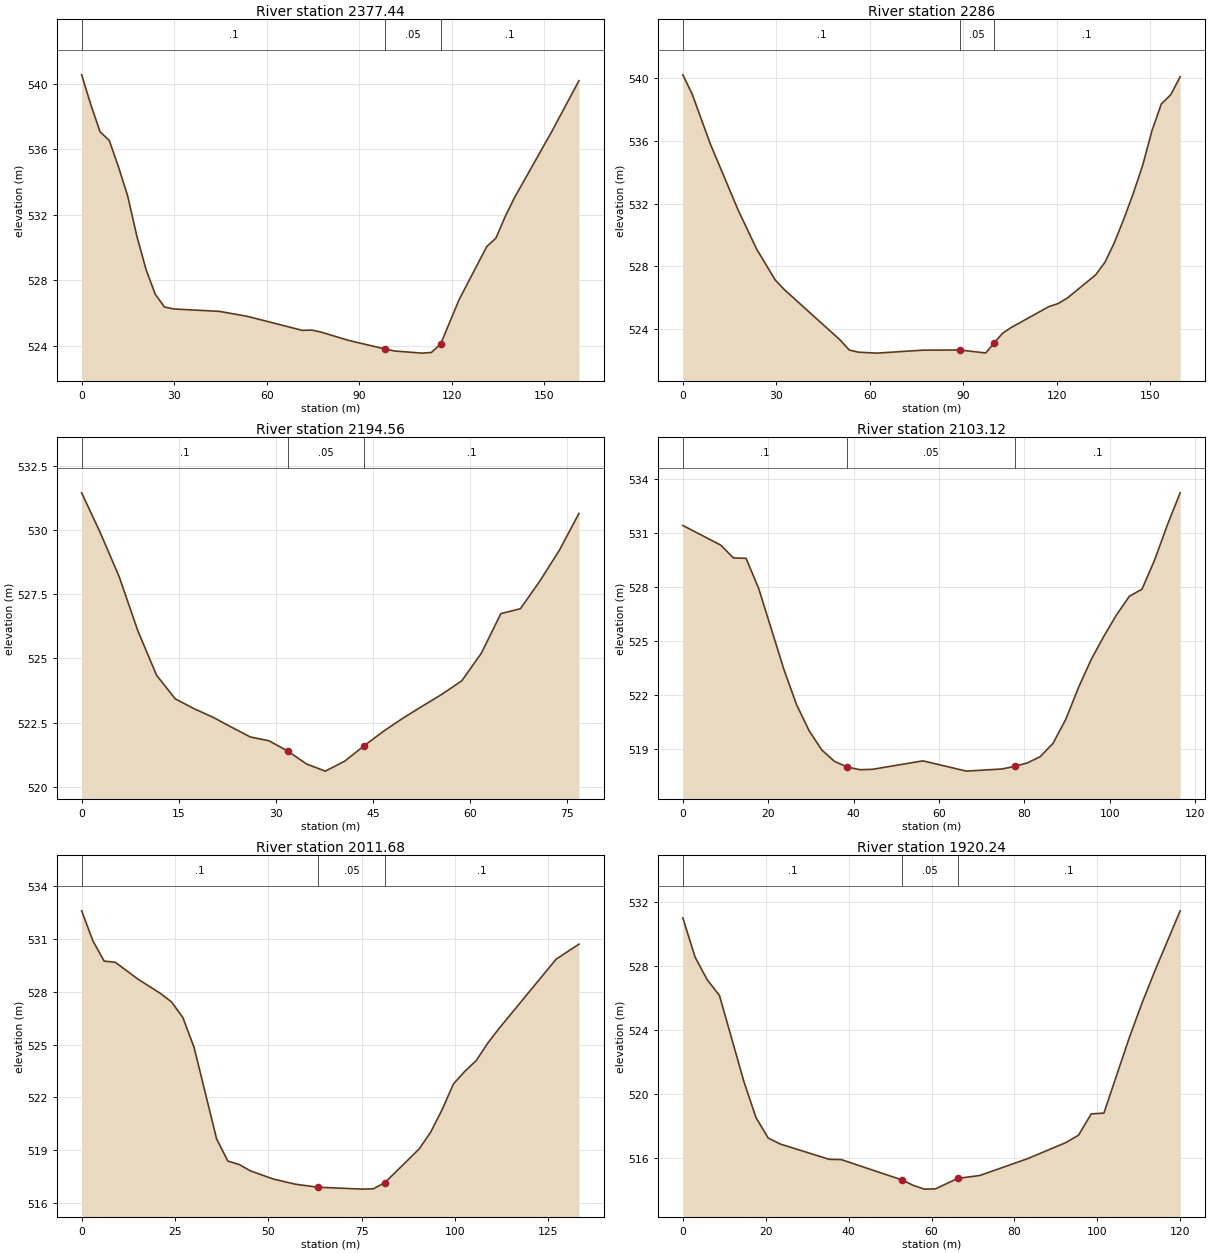
Type RM Length L Ch R = 1 ,2377.44 ,105.93,91.44,85.93
XS GIS Cut Line= 3
      607227.116    4340382.7711     607180.3719    4340296.1349
      607161.384    4340236.2681
#Sta/Elev= 29
       0  540.55    2.98  538.72    5.97  537.07    8.95  536.54   11.93  534.93
   14.92  533.15    17.9  530.69   20.88  528.65   23.86  527.14   26.85  526.36
   29.83  526.24   44.75  526.09    53.7  525.79   71.59  524.93   74.58  524.95
   77.56  524.83   86.51  524.32   98.44  523.79  101.43  523.67  110.41  523.54
   113.4  523.58  116.39  524.09  122.37   526.8  131.34  530.05  134.33  530.57
  137.32  531.88  140.31  533.03  152.28  537.03  161.25  540.19
#Mann= 3 , 0 , 0
       0      .1       0   98.44     .05       0  116.39      .1       0
Bank Sta=98.44,116.39
XS Rating Curve= 0 ,0
Exp/Cntr=0.3,0.1

Type RM Length L Ch R = 1 ,2286    ,87.78,91.44,92.75
XS GIS Cut Line= 5
     607333.2825    4340292.7322     607276.1574    4340250.2329
     607257.8693    4340240.7511     607246.9452    4340232.6995
     607207.2164    4340195.7309
#Sta/Elev= 30
       0  540.21    2.97  538.99     8.9  535.76    17.8  531.56   23.73  529.08
   29.67  527.12   32.63   526.5   50.43  523.31    53.4  522.66   56.37  522.52
    62.3  522.46   77.09  522.65   88.86  522.66   97.23  522.47   99.88   523.1
  102.66  523.73  105.37  524.09  117.43  525.42  120.45  525.62  123.46  525.98
  132.51  527.45  135.52  528.26  138.53  529.51  141.55  531.01  144.56  532.63
  147.58  534.42  150.59  536.65  153.61  538.36  156.62  538.94  159.64  540.09
#Mann= 3 , 0 , 0
       0      .1       0   88.86     .05       0   99.88      .1       0
Bank Sta=88.86,99.88
XS Rating Curve= 0 ,0
Exp/Cntr=0.3,0.1

Type RM Length L Ch R = 1 ,2194.56 ,87.41,91.44,101.4
XS GIS Cut Line= 3
     607342.7378    4340204.4785     607319.0305    4340175.2734
      607290.296    4340148.6314
#Sta/Elev= 29
       0  531.44    2.89  529.88    5.79  528.18    8.68  526.07   11.57  524.34
   14.47  523.42   17.36  523.04   20.25  522.71   23.15  522.32   26.04  521.94
   28.94  521.79   31.83  521.39   34.72  520.89   34.82  520.88   37.62  520.61
   38.73  520.75   40.63     521   43.64   521.6   46.66  522.17   49.67  522.68
   52.69  523.15    55.7  523.61   58.72  524.13   61.73   525.2   64.74  526.74
   67.76  526.93   70.77  528.01   73.79  529.21    76.8  530.64
#Mann= 3 , 0 , 0
       0      .1       0   31.83     .05       0   43.64      .1       0
Bank Sta=31.83,43.64
XS Rating Curve= 0 ,0
Exp/Cntr=0.3,0.1

Type RM Length L Ch R = 1 ,2103.12 ,84.24,91.44,91.65
XS GIS Cut Line= 4
     607411.8714    4340186.7157     607397.3008    4340129.3434
     607400.1427    4340120.1171     607388.1027    4340074.0227
#Sta/Elev= 30
       0  531.41    8.88  530.32   11.84  529.61    14.8  529.59   17.76  527.92
   23.68  523.42   26.64  521.47    29.6  520.02   32.56  518.96   35.52  518.33
   38.48  518.02   41.44  517.87    44.4  517.89   56.23  518.36   66.43  517.79
    74.8  517.91   77.78  518.06   80.76  518.25   83.74   518.6   86.71  519.33
   89.69  520.66   92.67  522.42   95.65  523.98   98.62  525.27   101.6  526.46
  104.58  527.48  107.56  527.88  110.53  529.51  113.51  531.45  116.49  533.22
#Mann= 3 , 0 , 0
       0      .1       0   38.48     .05       0   77.78      .1       0
Bank Sta=38.48,77.78
XS Rating Curve= 0 ,0
Exp/Cntr=0.3,0.1

Type RM Length L Ch R = 1 ,2011.68 ,93.1,91.44,97.05
XS GIS Cut Line= 4
     607467.1899    4340202.6527     607485.4269    4340135.7937
     607488.1922    4340127.3346      607487.173    4340072.2907
#Sta/Elev= 29
       0  532.58    3.01  530.88    6.03  529.73    9.04  529.66   15.07  528.71
   21.09   527.9    24.1  527.41   27.12  526.53   30.13  524.83   36.16  519.65
   39.17  518.39   42.18   518.2    45.2  517.84   51.22  517.38   57.25  517.08
   63.28  516.91   75.23   516.8    78.2  516.82   81.26  517.17   90.44  519.08
   93.49  520.02   96.55  521.29   99.61  522.76  102.67  523.48  105.73  524.09
  108.79  525.07  111.84  525.91  127.14  529.84  133.25  530.69
#Mann= 3 , 0 , 0
       0      .1       0   63.28     .05       0   81.26      .1       0
Bank Sta=63.28,81.26
XS Rating Curve= 0 ,0
Exp/Cntr=0.3,0.1

Type RM Length L Ch R = 1 ,1920.24 ,95.12,91.44,80.52
XS GIS Cut Line= 6
     607573.3345    4340189.0949     607576.6735    4340136.2811
     607579.2805    4340125.8534     607583.1466    4340118.8824
     607585.9169    4340107.6684     607585.5796    4340070.8815
#Sta/Elev= 25
       0  530.98    2.94  528.54    5.88  527.12    8.82  526.15    14.7   520.8
   17.64  518.53   20.58  517.26   23.52  516.88   35.28  515.93   38.22  515.91
   52.92  514.64   55.61   514.3   58.29  514.07   60.98  514.09   66.33  514.74
   71.64  514.92   83.19  515.97   92.39  516.97   95.45  517.43   98.52  518.76
  101.58  518.81  107.72  523.52  110.78  525.67  113.85  527.66  119.98  531.42
#Mann= 3 , 0 , 0
       0      .1       0   52.92     .05       0   66.33      .1       0
Bank Sta=52.92,66.33
XS Rating Curve= 0 ,0
Exp/Cntr=0.3,0.1