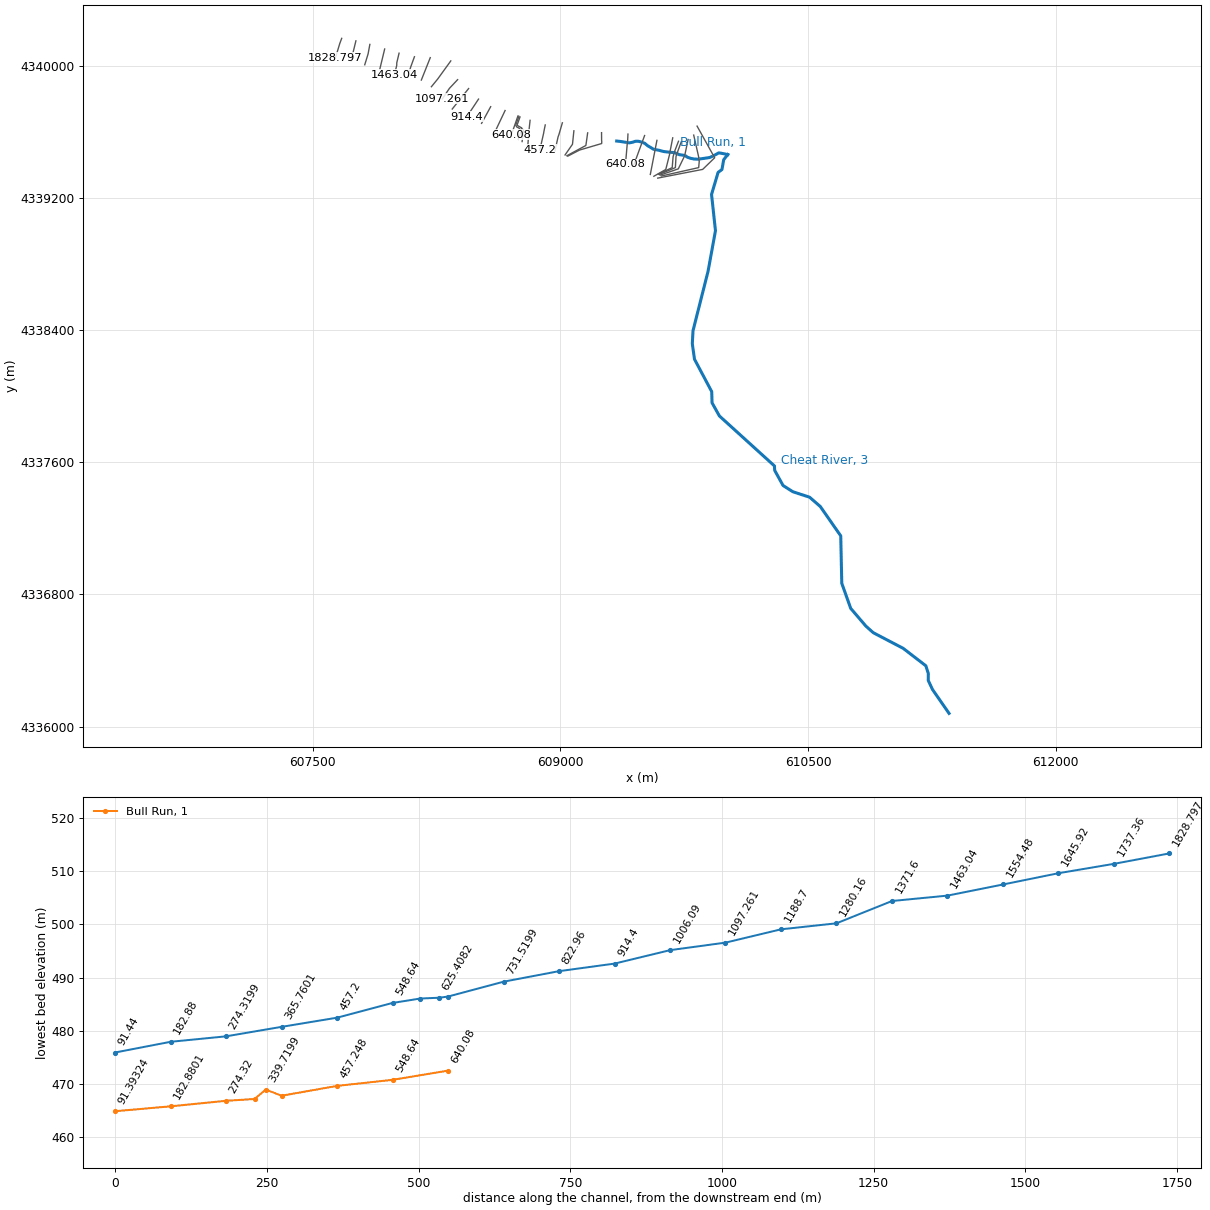
HEC-RAS study CheatRiver.prj: CheatRiver

--- CheatRiver.g01 (geometry) --- (continued)

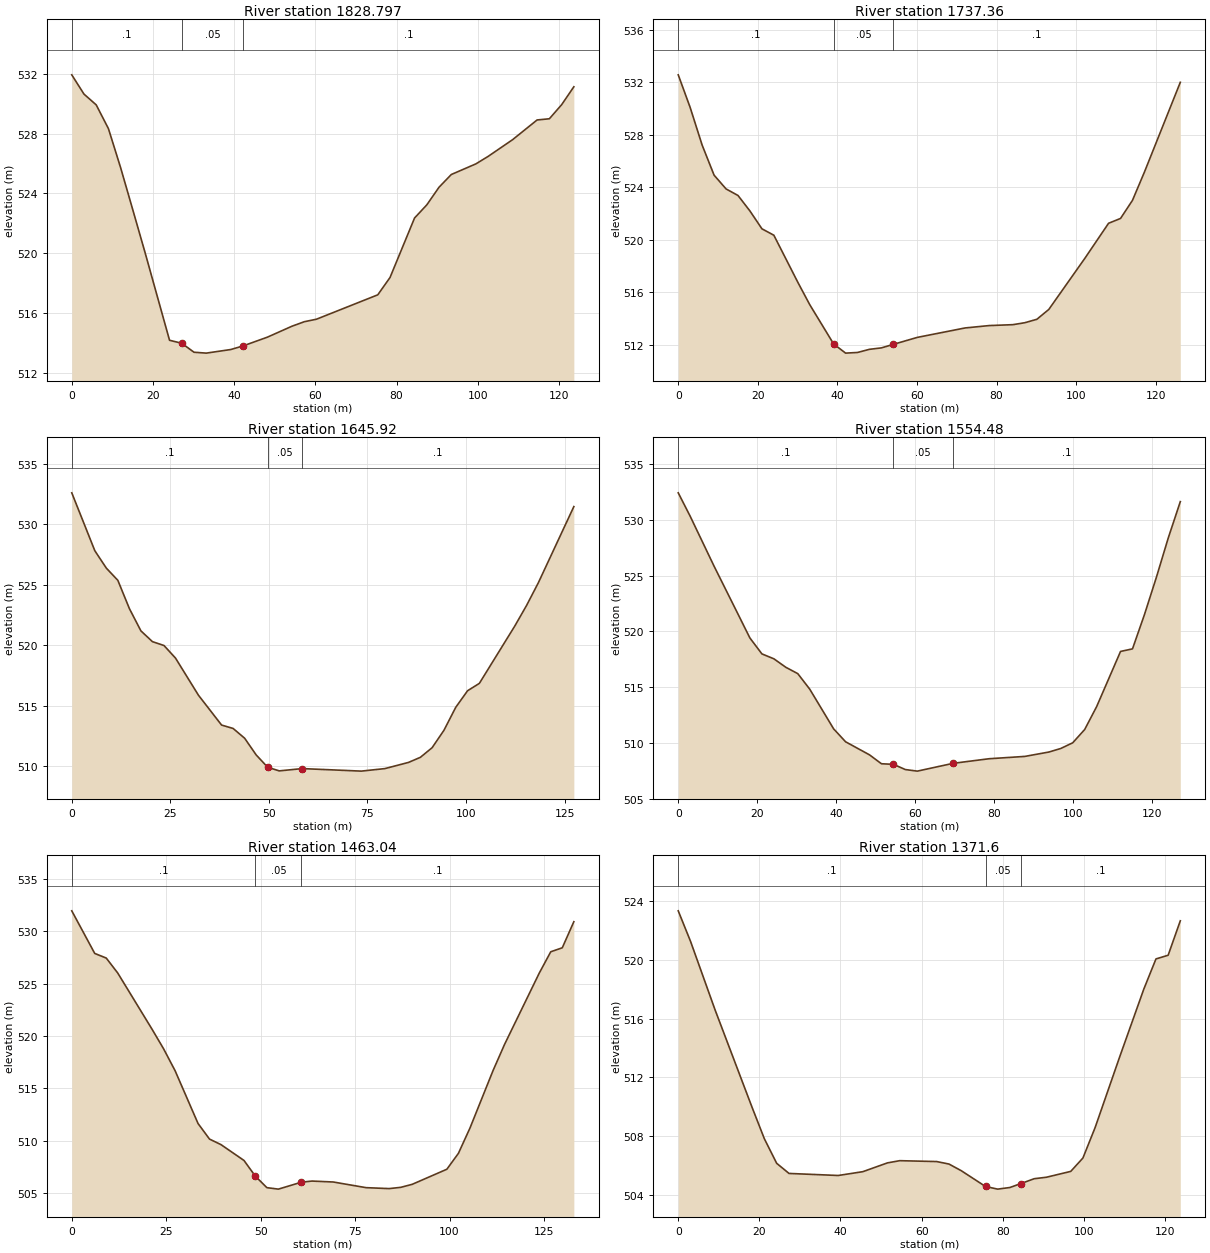
Type RM Length L Ch R = 1 ,1828.797,91.52,91.44,92.14
XS GIS Cut Line= 3
     607676.4796    4340167.1289     607664.8753    4340136.1222
     607638.6403    4340049.4586
#Sta/Elev= 30
       0  531.93    3.01  530.64    6.02  529.92    9.03  528.33   12.04  525.71
   15.05  522.88   18.06  520.03   24.08  514.17   27.09  513.97    30.1  513.37
   33.11  513.31   39.14  513.55   42.16  513.79    48.2  514.38   54.23  515.11
   57.25  515.41   60.27  515.58   75.36  517.21   78.38  518.37   84.42  522.35
   87.44  523.23   90.45  524.41   93.47  525.26   99.51  525.97  102.53  526.47
  108.56  527.59   114.6  528.91  117.62  528.99  120.64  529.93  123.65  531.13
#Mann= 3 , 0 , 0
       0      .1       0   27.09     .05       0   42.16      .1       0
Bank Sta=27.09,42.16
XS Rating Curve= 0 ,0
Exp/Cntr=0.3,0.1

Type RM Length L Ch R = 1 ,1737.36 ,91.91,91.44,90.52
XS GIS Cut Line= 2
     607762.3954    4340151.8696     607732.5632    4340029.2782
#Sta/Elev= 30
       0  532.57       3  530.08    6.01  527.21    9.01  524.92   12.02  523.87
   15.02  523.37   18.02  522.19   21.03  520.83   24.03  520.34   30.04  516.76
   33.04  515.05   39.05  512.05   42.06  511.35   45.06   511.4   48.06  511.64
   51.07  511.75   54.07  512.02   60.08  512.55    72.1  513.27    78.1  513.45
   84.11  513.52   87.12  513.67   90.12  513.93   93.12  514.68  102.14  518.56
  108.14  521.25  111.15  521.62  114.15     523  117.16  525.16  126.17     532
#Mann= 3 , 0 , 0
       0      .1       0   39.05     .05       0   54.07      .1       0
Bank Sta=39.05,54.07
XS Rating Curve= 0 ,0
Exp/Cntr=0.3,0.1

Type RM Length L Ch R = 1 ,1645.92 ,91.87,91.44,91.59
XS GIS Cut Line= 3
     607846.8866    4340130.3689     607836.2625    4340072.8793
     607816.0095    4340007.0523
#Sta/Elev= 30
       0  532.61    5.85  527.82    8.77  526.38   11.69  525.37   14.62  523.03
   17.54  521.19   20.46   520.3   23.39  519.98   26.31  518.94   32.15  515.86
      38   513.4   40.92  513.12   43.85  512.31   46.77  510.93   49.69  509.91
   52.62  509.61   58.46   509.8   73.44  509.59   79.42   509.8   85.41  510.31
   88.41  510.73    91.4  511.53    94.4  512.97   97.39  514.87  100.39  516.24
  103.38  516.85  112.36  521.59  115.36   523.3  118.35  525.18  127.34  531.47
#Mann= 3 , 0 , 0
       0      .1       0   49.69     .05       0   58.46      .1       0
Bank Sta=49.69,58.46
XS Rating Curve= 0 ,0
Exp/Cntr=0.3,0.1

Type RM Length L Ch R = 1 ,1554.48 ,92.04,91.44,92.62
XS GIS Cut Line= 2
        607936.6    4340102.5985     607906.7784    4339978.8824
#Sta/Elev= 30
       0  532.42    3.03  530.32    9.09  525.84   18.18   519.4   21.21  517.98
   24.24  517.54   27.27  516.78    30.3  516.21   33.33  514.82   39.39  511.26
   42.42   510.1   48.48  508.93   51.51  508.13   54.54  508.08   57.57  507.61
    60.6  507.47   69.69  508.17   78.78  508.58   87.87  508.79   93.93  509.18
   96.96   509.5   99.99  510.01  103.02   511.2  106.05  513.25  112.11   518.2
  115.14  518.43  118.17   521.5   121.2  524.85  124.23   528.4  127.26  531.63
#Mann= 3 , 0 , 0
       0      .1       0   54.54     .05       0   69.69      .1       0
Bank Sta=54.54,69.69
XS Rating Curve= 0 ,0
Exp/Cntr=0.3,0.1

Type RM Length L Ch R = 1 ,1463.04 ,89.2,91.44,89.04
XS GIS Cut Line= 4
     608023.7679    4340077.2348      608009.747    4340018.1068
     608009.7759     4340004.021     607995.8853    4339947.6647
#Sta/Elev= 30
       0  531.96    6.08  527.89    9.12  527.45   12.15  526.03   21.27  520.64
   24.31  518.78   27.35  516.69   33.42  511.65   36.46  510.16    39.5  509.63
   45.58  508.12   48.61  506.61   51.65  505.52   54.69  505.38   60.77  506.04
   63.58  506.15   69.22  506.06   77.91  505.52   84.02  505.43   87.07  505.55
   90.13  505.84   99.29  507.28  102.35   508.8   105.4  511.21  111.51   516.7
  114.57  519.21  123.73     526  126.79  528.05  129.84  528.43   132.9  530.92
#Mann= 3 , 0 , 0
       0      .1       0   48.61     .05       0   60.77      .1       0
Bank Sta=48.61,60.77
XS Rating Curve= 0 ,0
Exp/Cntr=0.3,0.1

Type RM Length L Ch R = 1 ,1371.6  ,92.93,91.44,90.73
XS GIS Cut Line= 3
     608116.8431    4340055.6832     608094.0206    4339992.9597
     608076.8488    4339938.5826
#Sta/Elev= 28
       0  523.35    3.03  521.27     9.1  516.58    18.2  509.95   21.24   507.8
   24.27  506.13   27.31  505.44   39.44   505.3   45.51  505.56   51.58  506.16
   54.61  506.31   63.71  506.25   66.75  506.08   69.75  505.63   75.75  504.55
   78.75  504.37   81.75  504.48   84.48  504.75   87.76  505.08   90.76  505.18
   96.76  505.58   99.76  506.49  102.76  508.56  108.76  513.34  114.77  518.01
  117.77  520.07  120.77  520.32  123.77  522.67
#Mann= 3 , 0 , 0
       0      .1       0   75.75     .05       0   84.48      .1       0
Bank Sta=75.75,84.48
XS Rating Curve= 0 ,0
Exp/Cntr=0.3,0.1

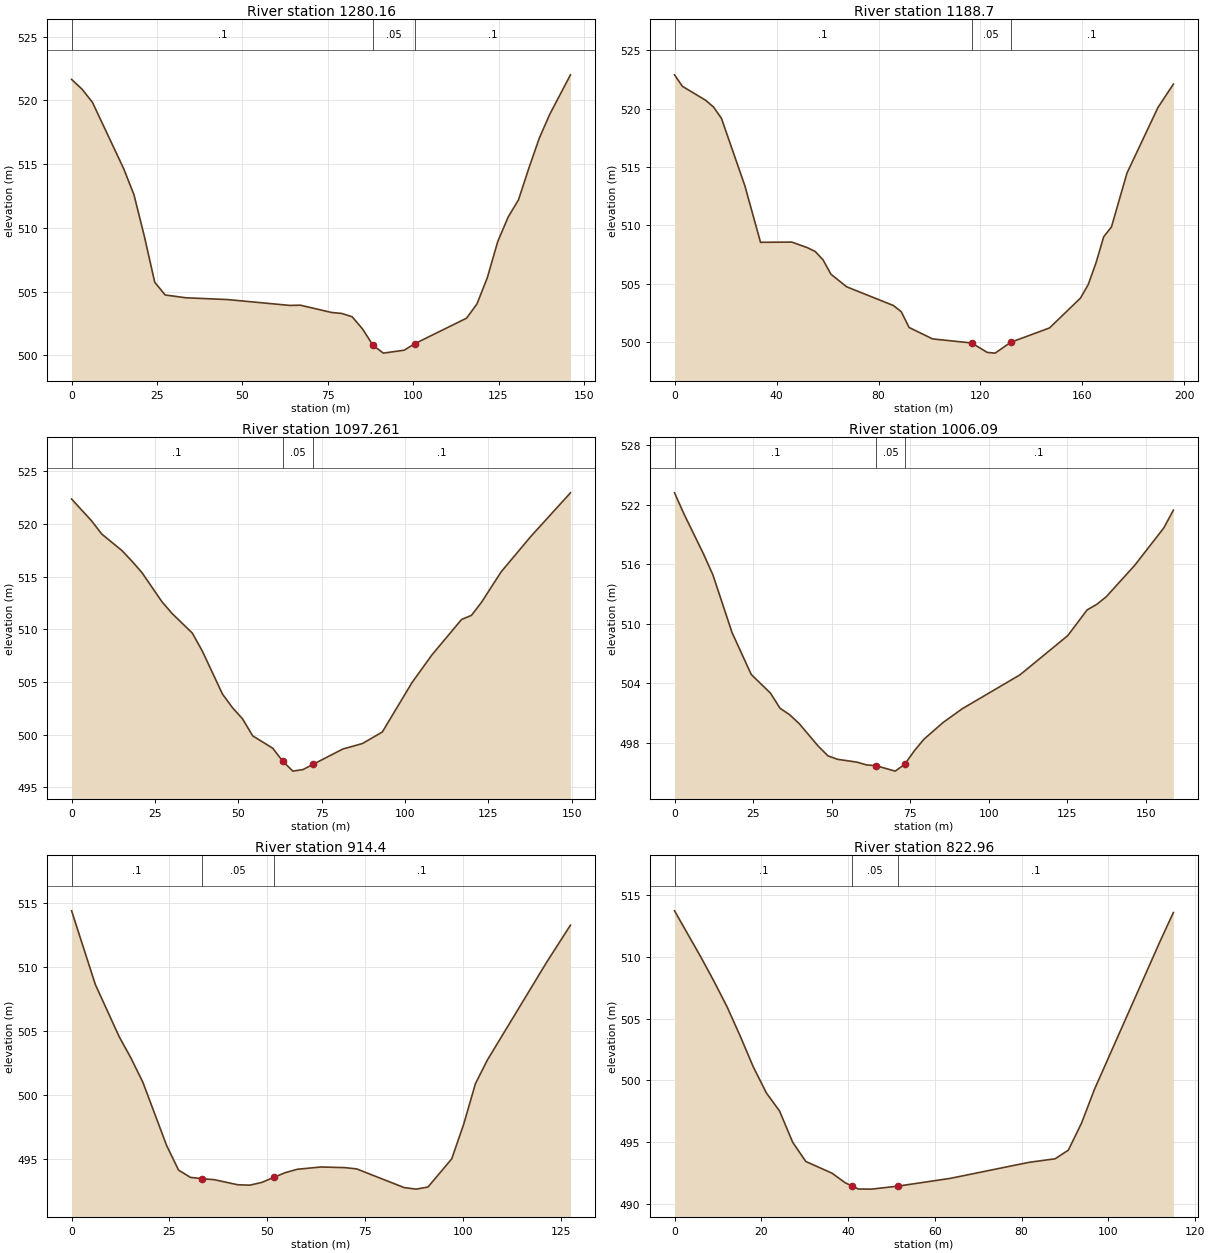
Type RM Length L Ch R = 1 ,1280.16 ,103.32,91.46,89.09
XS GIS Cut Line= 2
     608212.6434    4340050.2047     608158.6333    4339914.4871
#Sta/Elev= 30
       0  521.64    3.04  520.88    6.09  519.85   15.22  514.66   18.26   512.6
    21.3  509.34   24.34  505.74   27.39  504.74   33.47  504.52   45.65  504.38
   63.91  503.92   66.95  503.94   76.08  503.37   79.12  503.29   82.16  503.03
   85.21  502.07   88.25  500.79   91.29  500.18   97.38  500.41  100.42  500.91
  115.64  502.92  118.68  504.03  121.72  506.09  124.77  508.92  127.81  510.84
  130.85   512.2   133.9  514.69  136.94  517.03  139.98  518.89  146.07     522
#Mann= 3 , 0 , 0
       0      .1       0   88.25     .05       0  100.42      .1       0
Bank Sta=88.25,100.42
XS Rating Curve= 0 ,0
Exp/Cntr=0.3,0.1

Type RM Length L Ch R = 1 ,1188.7  ,92.26,91.44,91.17
XS GIS Cut Line= 3
     608336.9432     4340030.488     608257.8885    4339921.1355
      608219.468    4339874.1189
#Sta/Elev= 30
       0  522.91    3.07  521.93   12.27  520.72   15.33  520.14    18.4  519.18
    27.6  513.39   33.73  508.55      46  508.57   52.13  508.09    55.2  507.76
   58.27  507.04   61.33  505.82   67.47  504.74   85.87  503.13   88.93   502.6
      92  501.25   101.2  500.27  116.54  499.92  122.67  499.11  125.74  499.05
  131.87  499.98  147.08  501.21  159.22  503.77  162.26  504.93  165.29  506.78
  168.33  509.03  171.37  509.87  177.44  514.48  189.58   520.1  195.65  522.11
#Mann= 3 , 0 , 0
       0      .1       0  116.54     .05       0  131.87      .1       0
Bank Sta=116.54,131.87
XS Rating Curve= 0 ,0
Exp/Cntr=0.3,0.1

Type RM Length L Ch R = 1 ,1097.261,90.96,91.17,91.29
XS GIS Cut Line= 3
     608378.2183    4339916.9815     608328.6269    4339864.2438
     608285.3494       4339800.3
#Sta/Elev= 30
       0  522.35    6.03  520.27    9.05  519.03   15.08  517.47    18.1  516.46
   21.11  515.37   27.15  512.59   30.16  511.49    36.2  509.64   39.21  507.93
   45.24  503.86   48.26  502.56   51.28   501.5   54.29   499.9   60.33  498.72
   63.34  497.48   66.36  496.55   69.38   496.7   72.39  497.19    81.3  498.64
   87.24  499.17   93.18  500.26  102.09  504.95  108.03  507.56  116.94  510.93
  119.91  511.32  122.88  512.54  128.82  515.45  137.73  518.81   149.6  522.94
#Mann= 3 , 0 , 0
       0      .1       0   63.34     .05       0   72.39      .1       0
Bank Sta=63.34,72.39
XS Rating Curve= 0 ,0
Exp/Cntr=0.3,0.1

Type RM Length L Ch R = 1 ,1006.09 ,90.94,91.69,91.93
XS GIS Cut Line= 2
     608444.8212    4339863.0727     608345.6745    4339739.1811
#Sta/Elev= 30
       0  523.22    3.05  521.06    9.15   517.1   12.21  514.94   18.31  509.11
   24.41  504.89   30.52  503.01   33.57  501.48   36.62  500.83   39.67  499.93
   45.77  497.64   48.82  496.68   51.88  496.33   57.98  496.05   61.03  495.77
   64.08  495.69   70.19  495.14   73.24  495.83   76.29   497.2   79.34  498.36
   85.44  500.05   91.55  501.44  109.86  504.85  125.11  508.82  131.22   511.4
  134.27  511.96  137.32  512.73  146.47  515.94  155.63  519.68  158.68  521.47
#Mann= 3 , 0 , 0
       0      .1       0   64.08     .05       0   73.24      .1       0
Bank Sta=64.08,73.24
XS Rating Curve= 0 ,0
Exp/Cntr=0.3,0.1

Type RM Length L Ch R = 1 ,914.4   ,90.24,91.44,92.31
XS GIS Cut Line= 2
     608504.8297    4339799.1881     608434.4074    4339692.9369
#Sta/Elev= 28
       0  514.35    6.07  508.59   12.14  504.53   15.18  502.84   18.21  500.96
   24.28  496.02   27.32   494.1   30.35  493.53   33.39  493.42   36.42  493.35
   42.49  492.95   45.53  492.92   48.56  493.13    51.6  493.52   54.63   493.9
   57.67  494.16   63.73  494.34   69.81  494.29   72.84  494.19   84.98  492.73
   88.01  492.61   91.05  492.77   97.12  494.97  100.16  497.65  103.19  500.85
  106.23  502.69   121.4  510.34  127.47  513.23
#Mann= 3 , 0 , 0
       0      .1       0   33.39     .05       0    51.6      .1       0
Bank Sta=33.39,51.6
XS Rating Curve= 0 ,0
Exp/Cntr=0.3,0.1

Type RM Length L Ch R = 1 ,822.96  ,91.24,91.44,92.63
XS GIS Cut Line= 2
     608578.4542    4339753.3236     608523.3572    4339652.4089
#Sta/Elev= 24
       0  513.74    6.05  510.01    9.08  508.04    12.1  505.97   15.13   503.6
   18.15   501.1   21.18  498.98   24.21  497.52   27.23  494.99   30.26  493.43
   36.31  492.48   39.33  491.71   40.96  491.43   42.36   491.2   45.39  491.19
   51.44  491.43   63.54  492.06   81.69  493.36   87.74  493.65   90.77  494.35
    93.8  496.53   96.82   499.3  111.95   511.3  114.98   513.6
#Mann= 3 , 0 , 0
       0      .1       0   40.96     .05       0   51.44      .1       0
Bank Sta=40.96,51.44
XS Rating Curve= 0 ,0
Exp/Cntr=0.3,0.1

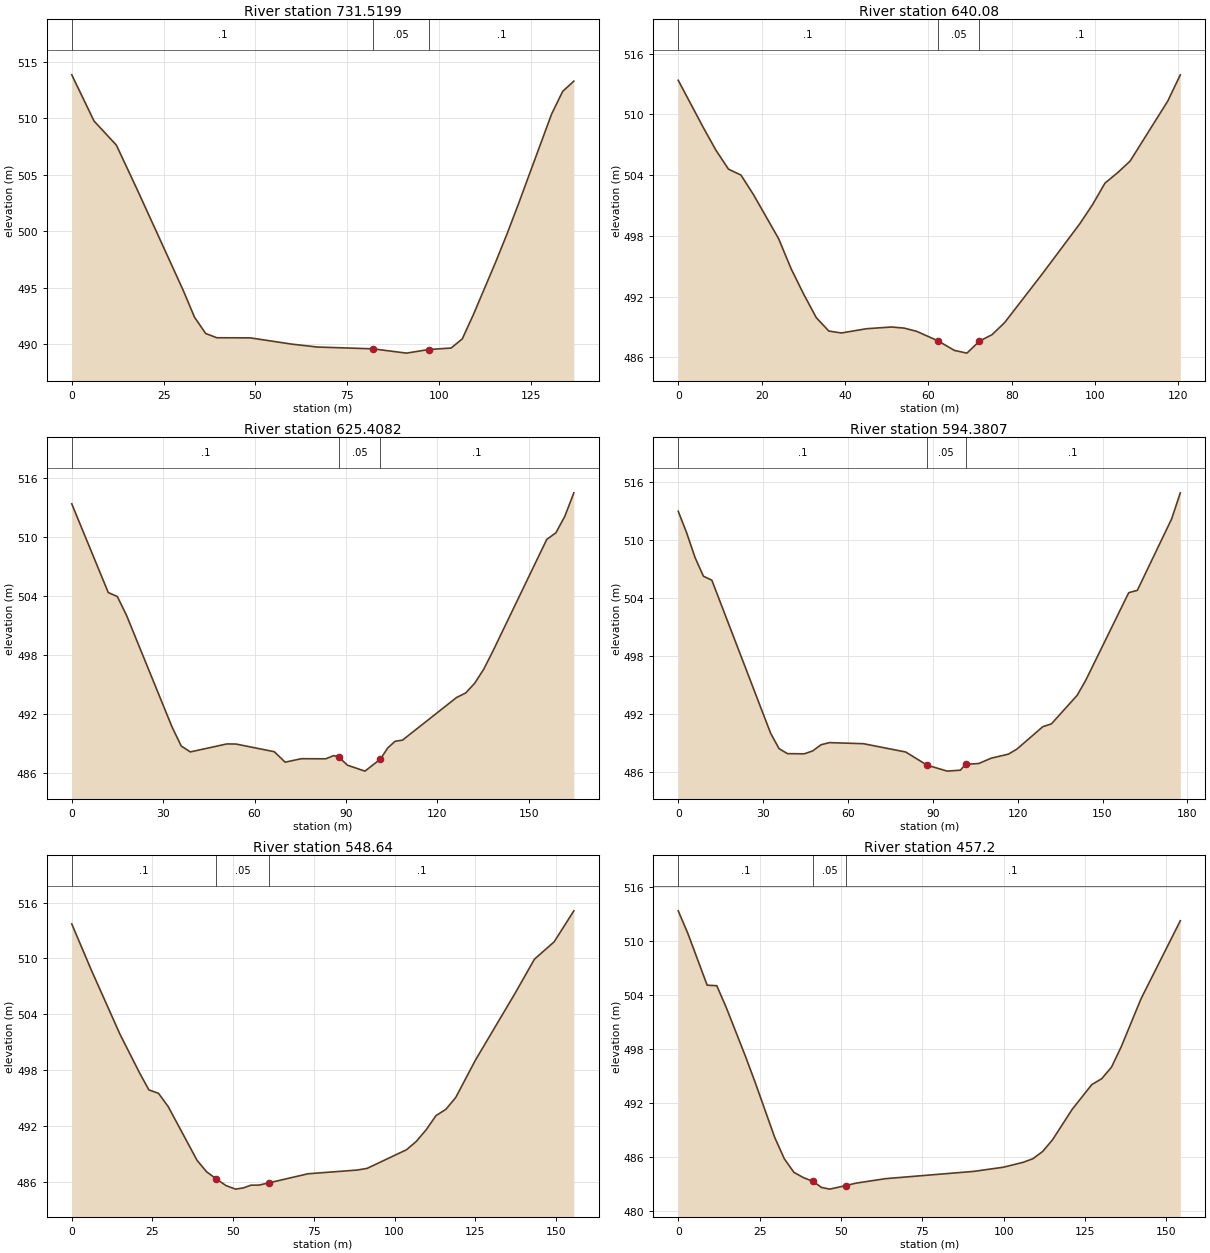
Type RM Length L Ch R = 1 ,731.5199,90.63,91.44,93.66
XS GIS Cut Line= 2
     608665.6734    4339730.0359     608607.1106    4339606.5451
#Sta/Elev= 23
       0  513.83    6.07  509.74   12.15  507.61   18.22  503.39   30.37  494.74
   33.41  492.39   36.45  490.95   39.48  490.57   48.59  490.56    59.8  490.01
   66.82  489.75      82  489.59   91.12  489.21   97.19  489.53  103.26  489.66
   106.3  490.47  109.34  492.63  115.41  497.28  118.45  499.73  121.49  502.32
   130.6  510.35  133.64  512.37  136.67  513.27
#Mann= 3 , 0 , 0
       0      .1       0      82     .05       0   97.19      .1       0
Bank Sta=82,97.19
XS Rating Curve= 0 ,0
Exp/Cntr=0.3,0.1

Type RM Length L Ch R = 1 ,640.08  ,5.77,14.67,39.2
XS GIS Cut Line= 2
     608743.4987    4339696.9791     608703.7197    4339583.2662
#Sta/Elev= 30
       0  513.36    6.02  508.69    9.04  506.46   12.05  504.59   15.06     504
   18.07  502.06   24.09  497.72   27.11  494.73   30.12  492.23   33.13  489.92
   36.14   488.6   39.15  488.41   45.18  488.83    51.2     489   54.21  488.89
   57.22  488.57   62.34  487.63   66.26  486.69   69.27  486.42   72.28  487.61
   75.29  488.24   78.31  489.43   87.34  494.24   96.38  499.21   99.39  501.07
   102.4  503.21  105.41  504.23  108.42  505.38  117.46  511.31  120.47   513.9
#Mann= 3 , 0 , 0
       0      .1       0   62.34     .05       0   72.28      .1       0
Bank Sta=62.34,72.28
XS Rating Curve= 0 ,0
Exp/Cntr=0.3,0.1

Type RM Length L Ch R = 1 ,625.4082,7.5,31.03,21.13
XS GIS Cut Line= 6
     608749.3728    4339694.8151     608730.0907    4339641.2807
     608736.0812    4339630.8469     608750.1306    4339623.2268
     608764.3917    4339608.6549     608745.3417    4339555.7381
#Sta/Elev= 30
       0  513.33   11.98  504.33   14.97  503.92   17.97  502.02   32.94  490.67
   35.94  488.75   38.93  488.15   50.91  488.96   53.91  488.95    66.5  488.17
   70.05  487.11   75.37  487.46   83.37  487.45   86.03  487.78   87.67  487.62
   90.53   486.8   96.26   486.2  101.33  487.42  103.75  488.56  106.17  489.23
   108.6  489.35  126.36  493.68  129.32  494.13  132.28  495.12  135.24  496.54
   138.2  498.34  155.96  509.73  158.92  510.38  161.88  512.07  164.84  514.45
#Mann= 3 , 0 , 0
       0      .1       0   87.67     .05       0  101.33      .1       0
Bank Sta=87.67,101.33
XS Rating Curve= 0 ,0
Exp/Cntr=0.3,0.1

Type RM Length L Ch R = 1 ,594.3807,76.12,45.74,32.91
XS GIS Cut Line= 6
     608756.0289     4339691.244     608737.9333    4339640.9341
     608766.5084    4339624.5299     608765.2384     4339620.667
     608777.4092    4339612.7295     608768.7441    4339542.0132
#Sta/Elev= 30
       0  512.94    2.97  510.72    5.94  508.16    8.91  506.22   11.88  505.81
   32.67  489.97   35.64  488.38   38.61  487.86   44.55  487.84   47.52  488.14
   50.49  488.78   53.47     489   65.45  488.89   80.42  488.03   87.96  486.67
   95.12  486.05   99.76  486.15  101.57  486.75  106.27  486.84  110.67  487.39
  116.75  487.81  119.79  488.34   128.9  490.65  131.94  490.94  141.05   493.9
  144.09  495.46  159.28  504.52  162.32  504.76  174.47  512.17  177.51  514.85
#Mann= 3 , 0 , 0
       0      .1       0   87.96     .05       0  101.57      .1       0
Bank Sta=87.96,101.57
XS Rating Curve= 0 ,0
Exp/Cntr=0.3,0.1

Type RM Length L Ch R = 1 ,548.64  ,91.65,91.44,91.38
XS GIS Cut Line= 4
     608817.0063    4339670.7475     608811.5164     4339620.273
     608810.4098     4339613.166     608803.2723    4339515.8194
#Sta/Elev= 30
       0   513.7    5.97  508.82   14.93  501.86   20.91  497.77   23.89  495.88
   26.88  495.51   29.87  494.09   38.83  488.31   41.81  487.07    44.8  486.32
   47.79   485.6   50.77  485.22   53.17  485.35   55.57  485.65   57.96  485.65
   61.02  485.89   73.22  486.87   88.47  487.27   91.52  487.45  103.72  489.45
  106.77  490.35  109.82   491.6  112.87  493.12  115.92  493.79  118.97  495.06
  125.07  499.07  137.27   506.2  143.37  509.92  149.47  511.78  155.57  515.11
#Mann= 3 , 0 , 0
       0      .1       0    44.8     .05       0   61.02      .1       0
Bank Sta=44.8,61.02
XS Rating Curve= 0 ,0
Exp/Cntr=0.3,0.1

Type RM Length L Ch R = 1 ,457.2   ,93.56,91.44,90.25
XS GIS Cut Line= 4
     608908.7706     4339642.834     608900.5243    4339602.1738
      608898.922    4339592.2071     608876.2974    4339492.0069
#Sta/Elev= 30
       0  513.33    2.96  510.82    8.89  505.08   11.85  505.02   14.82  502.55
   20.74  497.11   23.71  494.23   29.63  488.21    32.6  485.82   35.56  484.31
   38.52  483.72   41.49   483.3   44.01  482.64   46.54  482.45   51.58  482.85
    54.6  483.11   63.67  483.61   90.86  484.42   99.92  484.88  105.97  485.42
  108.99  485.82  112.01  486.63  115.03  487.92  121.07   491.3  127.11  494.05
  130.14   494.7  133.16  495.98  136.18  498.27  142.22  503.56  154.31  512.23
#Mann= 3 , 0 , 0
       0      .1       0   41.49     .05       0   51.58      .1       0
Bank Sta=41.49,51.58
XS Rating Curve= 0 ,0
Exp/Cntr=0.3,0.1

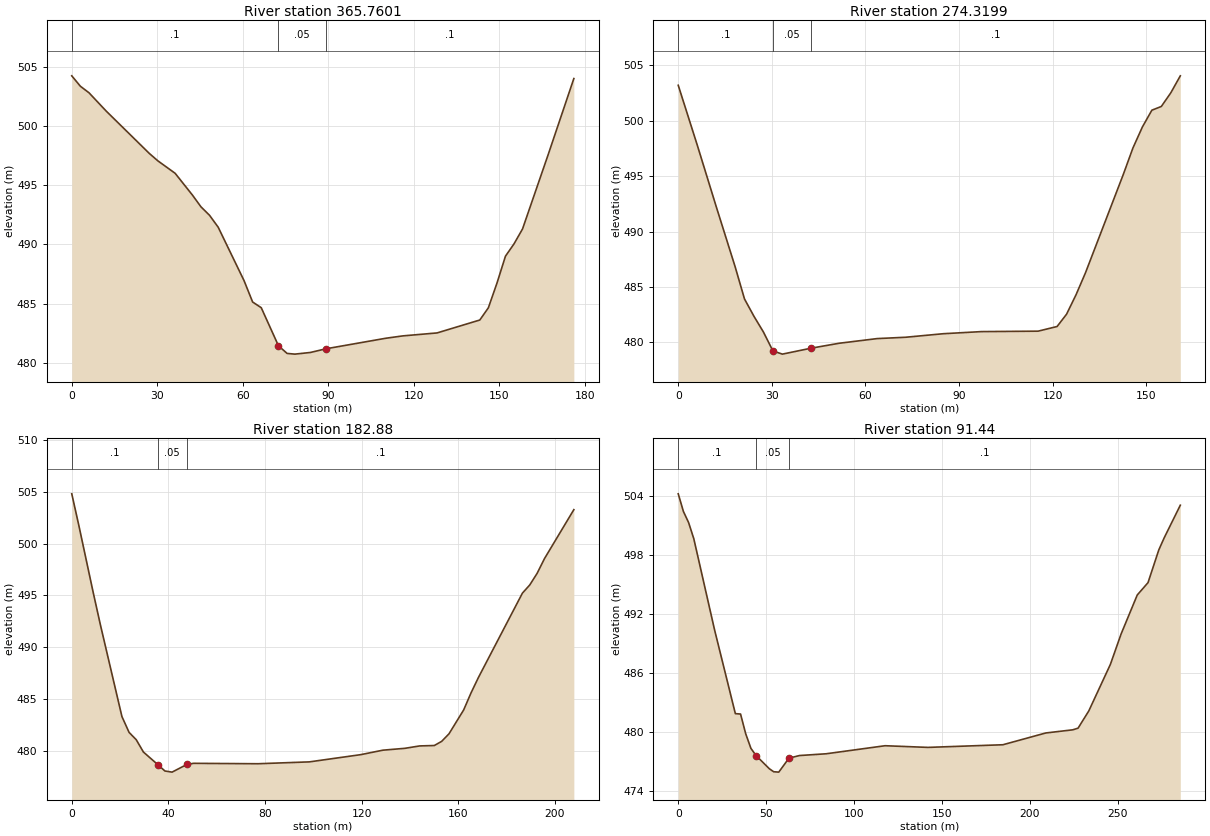
Type RM Length L Ch R = 1 ,365.7601,87.23,91.44,92.62
XS GIS Cut Line= 4
     609012.4676    4339655.8037     608991.2592    4339583.3054
     608986.4962    4339570.5405     608967.5789    4339485.6569
#Sta/Elev= 30
       0  504.23    3.02  503.35    6.04   502.8   12.09  501.25   27.19  497.68
   30.21  497.05   36.26     496    42.3  494.17   45.32  493.17   48.34  492.45
   51.36  491.45   60.43  486.94   63.45  485.13   66.47  484.65   72.52  481.43
   75.54  480.79   78.26  480.73   83.71  480.87   89.16  481.18  110.15  482.07
  116.15  482.27  128.15  482.52  143.14  483.61  146.14  484.64  149.14  486.71
  152.14     489  155.14  490.04  158.13   491.3  167.13  497.58  176.13     504
#Mann= 3 , 0 , 0
       0      .1       0   72.52     .05       0   89.16      .1       0
Bank Sta=72.52,89.16
XS Rating Curve= 0 ,0
Exp/Cntr=0.3,0.1

Type RM Length L Ch R = 1 ,274.3199,86.01,91.44,88.07
XS GIS Cut Line= 3
     609082.2549    4339607.3931     609073.7488    4339525.9146
     609028.6977    4339461.0506
#Sta/Elev= 27
       0  503.19    6.07  497.82   12.14  492.28    18.2  486.86   21.24  483.92
   24.27  482.36   27.31  480.94   30.34  479.24   33.38  478.95   42.48  479.48
   51.58  479.93   63.72  480.35   72.82  480.47   84.96  480.79   97.11  480.98
  115.33  481.02  121.41  481.44  124.45  482.55  127.48   484.3  130.52  486.29
  142.67  495.18  145.71  497.53  148.75  499.43  151.78  500.94  154.82  501.28
  157.86  502.51   160.9  504.04
#Mann= 3 , 0 , 0
       0      .1       0   30.34     .05       0   42.48      .1       0
Bank Sta=30.34,42.48
XS Rating Curve= 0 ,0
Exp/Cntr=0.3,0.1

Type RM Length L Ch R = 1 ,182.88  ,89.42,91.44,92.55
XS GIS Cut Line= 3
     609165.5998    4339594.7962     609154.8128    4339518.4512
     609039.8102    4339456.2881
#Sta/Elev= 30
       0   504.8    2.97   501.7     8.9  495.24   11.86  492.14   20.76  483.29
   23.72  481.76   26.69  481.05   29.66  479.86   35.59  478.65   38.55  478.03
   41.52  477.92   47.64  478.66   50.41  478.77    77.1  478.73   98.38  478.91
  119.67  479.61  128.79  480.04  137.91  480.22  143.99  480.45  150.07  480.49
  153.11  480.89  156.15  481.62  162.23  483.93  165.27  485.57  168.31  487.05
  186.55  495.21  189.59     496  192.63  497.12  195.67  498.54  207.83  503.27
#Mann= 3 , 0 , 0
       0      .1       0   35.59     .05       0   47.64      .1       0
Bank Sta=35.59,47.64
XS Rating Curve= 0 ,0
Exp/Cntr=0.3,0.1

Type RM Length L Ch R = 1 ,91.44   ,96.98,91.44,55.21
XS GIS Cut Line= 6
     609249.7247    4339595.9862     609249.9435    4339551.6994
     609250.9482    4339541.7788     609250.3109    4339530.2057
     609115.9729    4339490.5465     609045.3665    4339453.9068
#Sta/Elev= 30
       0  504.27    2.95  502.47     5.9  501.34    8.86  499.69   20.67   490.4
   32.48  481.87   35.43  481.83   38.38  479.81   41.33  478.33   44.29  477.59
   51.77  476.26   54.26  475.95   57.16  475.91   62.95  477.33   68.89   477.6
   84.12  477.78  117.61   478.6  141.97  478.43   184.6   478.7  208.98   479.9
  224.28  480.22  227.34  480.39  233.45  482.15  245.69  486.88  251.81  489.99
  260.99  493.96  267.11  495.22  273.23  498.55  276.29  499.78  285.47  503.11
#Mann= 3 , 0 , 0
       0      .1       0   44.29     .05       0   62.95      .1       0
Bank Sta=44.29,62.95
XS Rating Curve= 0 ,0
Exp/Cntr=0.3,0.1

River Reach=Bull Run        ,1
Reach XY= 30
     609341.4219    4339545.2405     609360.2073    4339543.3885
     609375.5378    4339540.9611      609417.622     4339534.128
     609437.1698    4339537.9232     609455.5849    4339544.0616
     609472.9416    4339544.0616      609490.118    4339539.4197
     609511.0201    4339531.7468     609528.4461    4339517.1877
     609544.6223    4339507.6696     609563.8046    4339495.7634
     609598.7297    4339489.0165     609625.7172    4339481.8727
     609665.0079    4339477.1102     609689.6142    4339475.5227
     609720.5705    4339462.8227     609748.7487    4339458.8539
     609757.6867    4339455.9551     609769.5401    4339447.4885
     609788.0394    4339440.9945      609808.677    4339436.6289
     609833.6801    4339435.4382     609871.7802    4339440.5976
     609903.1334    4339445.3601     609924.9616    4339454.4883
     609948.3772    4339467.5852      609958.696    4339473.5383
     609971.6822    4339472.0418     610013.6323    4339463.5057

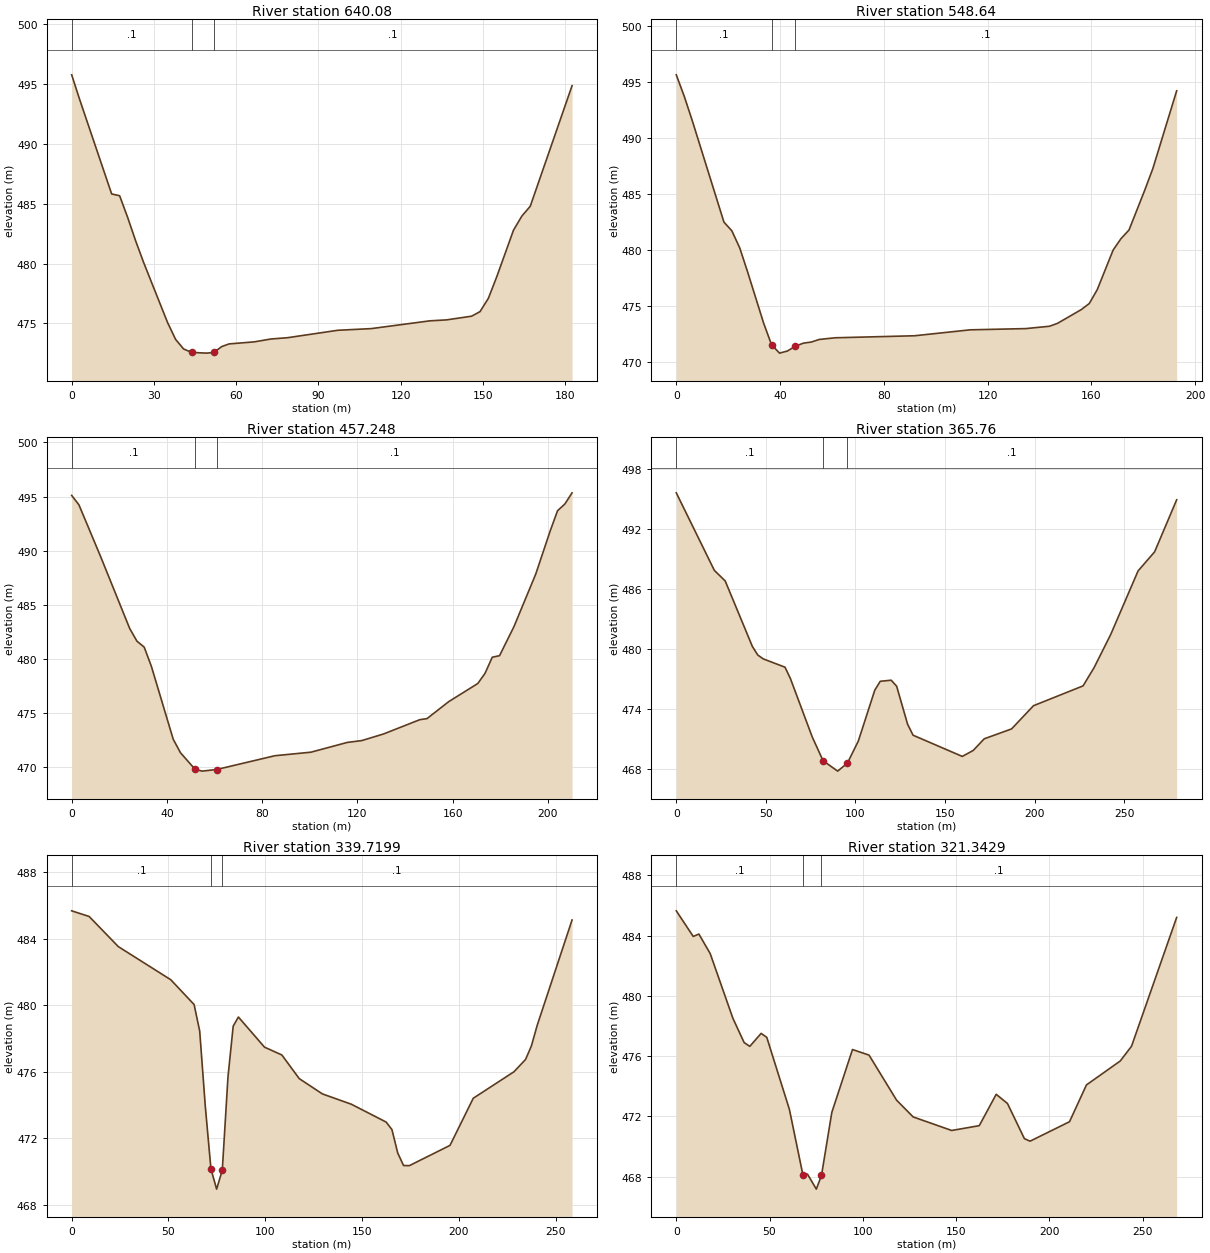
Type RM Length L Ch R = 1 ,640.08  ,90.64,91.44,85.49
XS GIS Cut Line= 4
     609409.5324    4339587.4626     609407.5295    4339543.7732
     609405.3415    4339530.2979     609394.7604    4339405.6183
#Sta/Elev= 30
       0  495.78    2.92  493.71   14.58  485.82   17.49  485.67   20.41  483.86
   23.33   481.9   26.24  480.09   34.99  475.06    37.9  473.66   40.82  472.86
   43.74  472.57    49.2  472.51   51.93  472.57   54.66  473.05   57.39  473.28
   66.54  473.45   72.65  473.69   78.75   473.8   97.06  474.42  109.27  474.56
  130.63  475.21  136.74  475.29  145.89   475.6  148.94  475.98     152   477.1
  155.05   478.9  161.15  482.79   164.2  483.97  167.26  484.79  182.51  494.87
#Mann= 3 , 0 , 0
       0      .1       0   43.74     .05       0   51.93      .1       0
Bank Sta=43.74,51.93
XS Rating Curve= 0 ,0
Exp/Cntr=0.3,0.1

Type RM Length L Ch R = 1 ,548.64  ,89.04,91.39,90.43
XS GIS Cut Line= 2
     609510.3153    4339578.5995     609443.8529    4339397.5461
#Sta/Elev= 30
       0  495.63    3.06  493.72    6.12  491.57   18.37  482.48   21.43   481.7
   24.49  480.16   27.55  477.99   33.68  473.45   36.74  471.52    39.8  470.78
   42.86  470.97   45.92   471.4   48.98  471.67   52.04  471.77    55.1     472
   61.23  472.15   91.84  472.33  113.27  472.86   134.7  472.97  143.88  473.18
  146.95  473.44  156.13  474.67  159.19  475.21  162.25  476.44  168.38  479.98
  171.44  481.01   174.5  481.77  180.62  485.36  183.68  487.25  192.87   494.2
#Mann= 3 , 0 , 0
       0      .1       0   36.74     .05       0   45.92      .1       0
Bank Sta=36.74,45.92
XS Rating Curve= 0 ,0
Exp/Cntr=0.3,0.1

Type RM Length L Ch R = 1 ,457.248 ,90.87,91.49,92.22
XS GIS Cut Line= 2
      609584.959     4339549.491     609544.9229    4339343.1829
#Sta/Elev= 30
       0   495.1    3.05  494.23   12.18  489.44   24.37  482.81   27.41  481.64
   30.46  481.09    33.5   479.3   42.64  472.59   45.69  471.34   51.78  469.82
   54.76  469.64   60.91  469.79   85.28  471.06  100.51  471.39  115.74  472.29
  121.83  472.46  130.97  473.07   146.2  474.39  149.24  474.49  158.38  476.06
  170.56  477.73  173.61  478.67  176.65  480.16   179.7   480.3  185.79     483
  194.93  487.85  201.02  491.85  204.07  493.69  207.11   494.3  210.16  495.34
#Mann= 3 , 0 , 0
       0      .1       0   51.78     .05       0   60.91      .1       0
Bank Sta=51.78,60.91
XS Rating Curve= 0 ,0
Exp/Cntr=0.3,0.1

Type RM Length L Ch R = 1 ,365.76  ,27.17,26.04,24.19
XS GIS Cut Line= 5
     609680.6544    4339564.6396     609664.8211    4339484.2659
     609663.1862    4339470.7779     609638.4951    4339373.0605
     609566.3542    4339332.0704
#Sta/Elev= 30
       0  495.61   21.24  487.86   27.31   486.8   42.48  480.25   45.51  479.39
   48.54  479.01   60.68  478.18   63.71  477.04   75.85  471.22   81.92  468.83
   90.07  467.79   95.51  468.59  101.61   470.8  110.78  475.88  113.83  476.77
  119.94  476.88  122.99  476.28   129.1  472.48  132.16  471.38  159.64  469.26
  165.75  469.86  171.86  471.02  187.13  472.01  199.37  474.33  227.02  476.31
  233.17  478.13  242.39  481.42  257.76  487.81  266.97  489.71  279.27  494.91
#Mann= 3 , 0 , 0
       0      .1       0   81.92     .05       0   95.51      .1       0
Bank Sta=81.92,95.51
XS Rating Curve= 0 ,0
Exp/Cntr=0.3,0.1

Type RM Length L Ch R = 1 ,339.7199,18.45,18.38,17.23
XS GIS Cut Line= 6
     609715.6109    4339543.9856     609692.8567    4339484.9834
      609687.565    4339468.3146     609682.8025    4339450.0584
     609677.5108    4339384.4416     609593.3417    4339344.7704
#Sta/Elev= 30
       0  485.67    9.03  485.33   24.09  483.52   51.19  481.53   63.24  480.04
   66.13  478.45   69.02  473.93   71.94  470.16   74.87  468.95    77.8  470.09
   80.73  475.68   83.43  478.74   86.12  479.29    99.6  477.48  108.57  477.01
  117.55  475.59  129.52  474.67  144.48  474.05  162.43  472.98  165.43  472.53
  168.43  471.12  171.43  470.37  174.43  470.36  195.44  471.58  207.45  474.41
  228.46     476  234.46  476.74  237.47  477.55  240.47  478.79  258.48  485.12
#Mann= 3 , 0 , 0
       0      .1       0   71.94     .05       0    77.8      .1       0
Bank Sta=71.94,77.8
XS Rating Curve= 0 ,0
Exp/Cntr=0.3,0.1

Type RM Length L Ch R = 1 ,321.3429,46.68,47.02,46.59
XS GIS Cut Line= 6
     609732.5443    4339541.0752     609711.5429    4339484.1765
     609709.2411    4339474.7308     609700.6189     4339452.218
     609696.6502    4339384.3523     609599.1626    4339343.1829
#Sta/Elev= 30
       0  485.64     9.1  483.94   12.13   484.1    18.2   482.8   30.33  478.52
   36.39   476.9   39.42  476.65   45.49  477.51   48.52  477.25   60.65  472.47
   67.94   468.1   70.37  468.17   75.09  467.18   77.86  468.09    83.4  472.27
   94.48  476.44  103.35  476.07  118.13  473.08  126.99  471.97  147.68  471.07
  162.46  471.39  171.53  473.47  177.58  472.86  186.65  470.53  189.68  470.36
  210.84  471.65  219.91  474.09  238.05  475.68   244.1  476.66  268.29   485.2
#Mann= 3 , 0 , 0
       0      .1       0   67.94     .05       0   77.86      .1       0
Bank Sta=67.94,77.86
XS Rating Curve= 0 ,0
Exp/Cntr=0.3,0.1

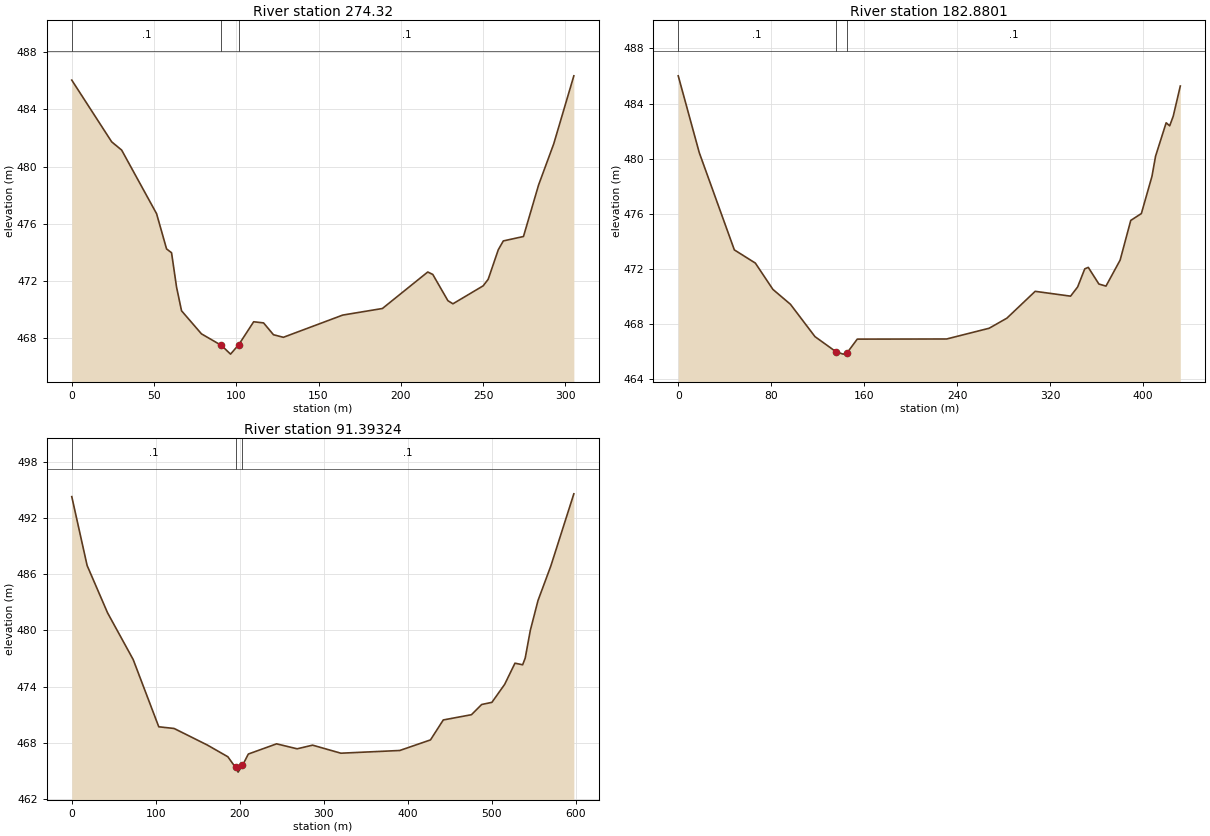
Type RM Length L Ch R = 1 ,274.32  ,81.85,91.44,105.69
XS GIS Cut Line= 5
     609773.7879      4339554.85     609755.0255    4339465.8265
     609749.9136    4339450.0648     609714.4306    4339376.9631
     609604.4543    4339338.9495
#Sta/Elev= 30
       0  486.06   24.26  481.73   30.33  481.15   51.55  476.69   57.62  474.22
   60.65  473.95   63.69  471.54   66.72  469.88   78.85  468.26   90.98  467.45
    96.5  466.84  101.55  467.51  110.56  469.11  116.58  469.03   122.6   468.2
  128.62  468.02  164.73  469.58  188.81  470.04  216.37   472.6  219.43  472.43
  228.61  470.59  231.68  470.37  250.05  471.63  253.11  472.09  259.24  474.16
   262.3  474.78  274.55  475.09  283.73   478.7  292.92  481.58  305.17  486.36
#Mann= 3 , 0 , 0
       0      .1       0   90.98     .05       0  101.55      .1       0
Bank Sta=90.98,101.55
XS Rating Curve= 0 ,0
Exp/Cntr=0.3,0.1

Type RM Length L Ch R = 1 ,182.8801,82.79,91.49,35.01
XS GIS Cut Line= 5
     609807.6547    4339581.3084     609837.0788    4339451.8098
     609841.1612    4339421.6626     609837.7929    4339384.4376
     609611.8626    4339333.6579
#Sta/Elev= 30
       0  486.01   18.11  480.43   48.29  473.37    66.4  472.41   81.49   470.5
   96.58  469.42  117.71  467.07  135.84  465.97  141.93   465.8  144.97  465.85
  154.09  466.89  231.07   466.9  267.63  467.68  282.87  468.41  307.24  470.36
  337.71  470.01   343.8  470.68   349.9  471.99  352.94   472.1  362.09  470.89
  368.18  470.74  380.37  472.63  389.51  475.51  398.65  476.01  407.79  478.72
  410.84  480.17  419.98   482.6  423.02  482.38  426.07  483.08  432.16  485.27
#Mann= 3 , 0 , 0
       0      .1       0  135.84     .05       0  144.97      .1       0
Bank Sta=135.84,144.97
XS Rating Curve= 0 ,0
Exp/Cntr=0.3,0.1

Type RM Length L Ch R = 1 ,91.39324,57.36,91.39,14.27
XS GIS Cut Line= 4
     609828.1114    4339635.6803     609934.5172    4339443.9272
     609861.9582    4339373.6338     609589.7213    4339320.8255
#Sta/Elev= 30
       0  494.29   18.27  486.94   42.64  481.88    73.1   476.9  103.56  469.72
  121.83  469.54  161.43  467.77  185.79  466.52  194.93  465.38  197.98  464.88
   203.2  465.59  210.16  466.81  243.79   467.9  268.28  467.37  286.65  467.76
  320.32   466.9  390.41  467.19  426.98  468.32  442.22  470.45  475.74  471.01
  487.93   472.1  500.12  472.33  515.35  474.26  527.54  476.51  536.69  476.34
  539.73  477.05  545.83  480.02  554.97   483.2  570.21  486.88  597.63  494.59
#Mann= 3 , 0 , 0
       0      .1       0  194.93     .05       0   203.2      .1       0
Bank Sta=194.93,203.2
XS Rating Curve= 0 ,0
Exp/Cntr=0.3,0.1

River Reach=Cheat River     ,3
Reach XY= 30
     611353.6544    4336080.1225     611253.4586    4336224.5949
     611227.7392    4336279.6397     611228.0586    4336321.4326
     611213.1627    4336368.2155     611075.5791    4336474.0491
     610894.9406    4336568.4805     610850.2063    4336608.3632
     610758.3518    4336715.6243     610704.1825    4336867.5337
     610697.8325    4337154.8718     610574.0072    4337332.6721
      610509.166    4337388.9298     610407.8203    4337422.1425
     610348.5818    4337459.6724     610297.7817    4337551.7476
     610296.6544    4337578.0864     609963.1727    4337880.7839
      609918.639    4337960.5834     609916.7809    4338027.9985
     609812.4319    4338224.3215     609799.1964     4338318.051
      609803.421    4338397.0697     609894.5559    4338756.6625
      609939.379    4339002.2734     609915.6663     4339222.041
     609955.3539    4339355.6559     609978.6936    4339372.6137
     609989.2554    4339432.2632     610013.6323    4339463.5057