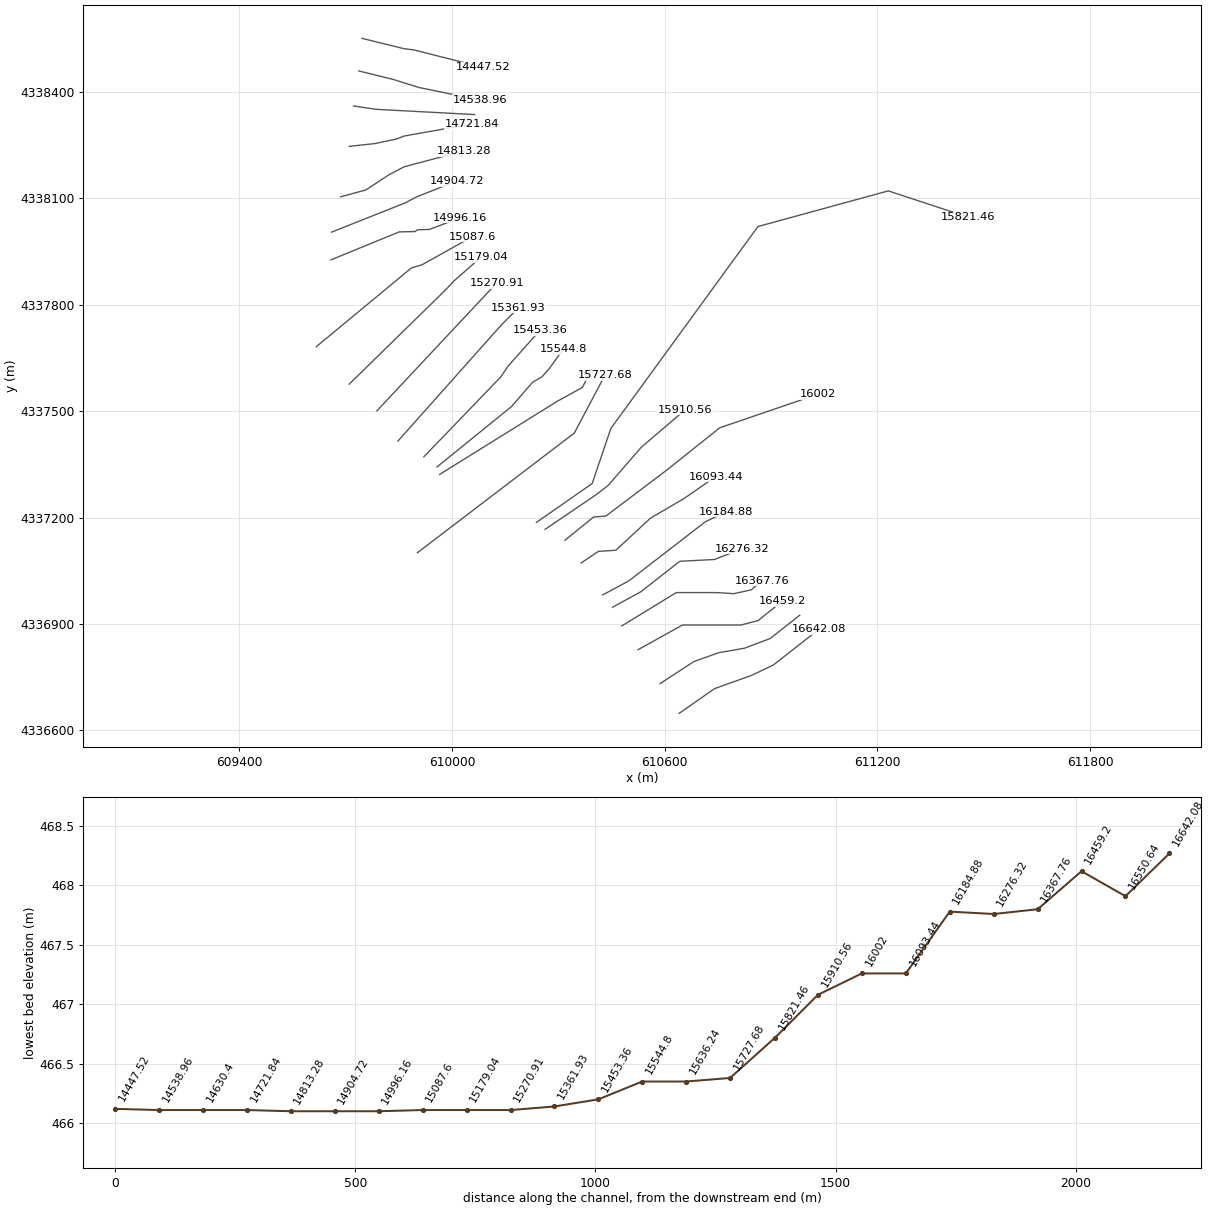
HEC-RAS study CheatRiver.prj: CheatRiver

--- CheatRiver.g01 (geometry) --- (continued)

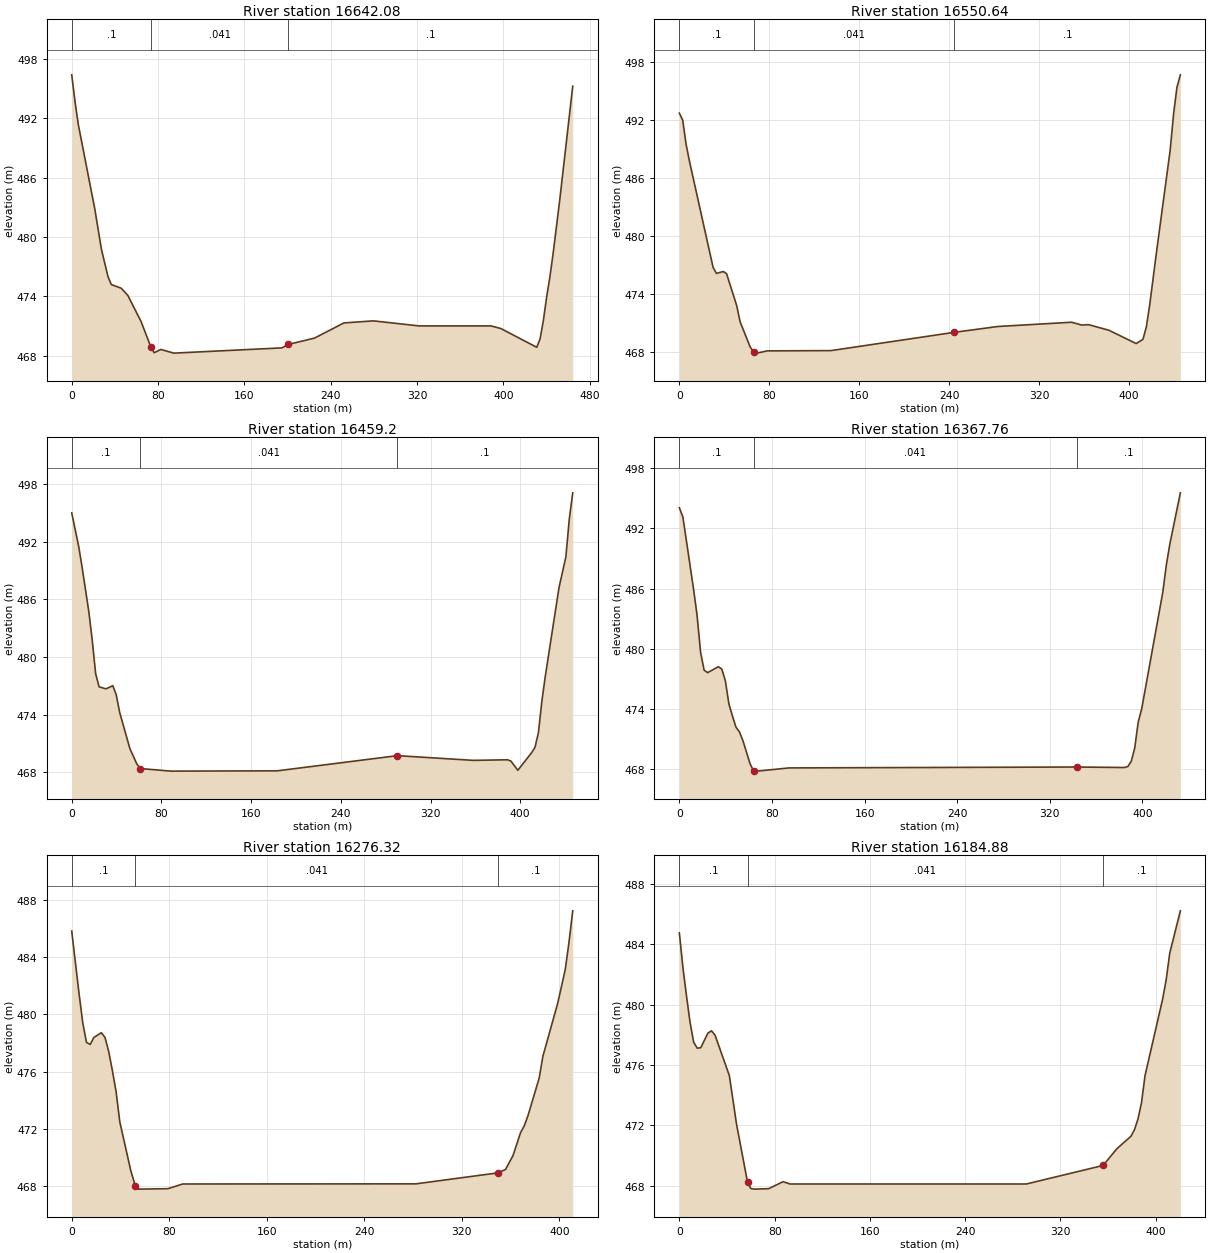
Type RM Length L Ch R = 1 ,16642.08,102.06,91.44,75.63
XS GIS Cut Line= 5
     610640.3904    4336647.4855     610740.6469    4336717.4537
     610843.0754    4336753.9786     610905.9675    4336783.7238
     611034.7891    4336884.6189
#Sta/Elev= 30
       0  496.39    3.06  493.69    6.11  491.37    21.4  482.83   27.51  478.77
   33.62  475.99   36.68   475.2   45.85  474.83   51.96  474.11   64.19  471.48
   73.35  468.89   76.41  468.31   82.52  468.64   94.75  468.27  194.75   468.8
   200.8  469.15  224.96  469.79  252.18  471.32   279.4  471.53  321.79  471.02
  388.45  471.02  397.54  470.76  430.87  468.86   433.9  469.69  436.93  471.51
  439.96  473.89  442.99  475.93  446.02  478.33  452.08  483.66   464.2  495.24
#Mann= 3 , 0 , 0
       0      .1       0   73.35    .041       0   200.8      .1       0
Bank Sta=73.35,200.8
XS Rating Curve= 0 ,0
Exp/Cntr=0.3,0.1

Type RM Length L Ch R = 1 ,16550.64,112.81,91.44,63.23
XS GIS Cut Line= 6
     610586.6234    4336731.4003     610682.1315    4336793.6674
     610752.1373    4336818.6308     610825.1372    4336831.4018
     610897.4218    4336858.7585     610980.5494    4336924.3065
#Sta/Elev= 30
       0  492.69       3  491.97       6  489.49       9  487.72      30  476.77
      33  476.14      39  476.34      42  476.12   51.01  472.82   54.01  471.16
   63.01  468.54   66.01  468.06   69.01  467.91   78.01  468.14  134.82  468.17
  244.66  470.06  283.25  470.66  348.81   471.1  357.88  470.81  363.93  470.85
  382.08  470.27  406.28   468.9  412.32  469.33  415.35  470.61  418.37  472.93
  424.42  478.38  436.52  488.85  439.55  492.58  442.57  495.37   445.6  496.65
#Mann= 3 , 0 , 0
       0      .1       0   66.01    .041       0  244.66      .1       0
Bank Sta=66.01,244.66
XS Rating Curve= 0 ,0
Exp/Cntr=0.3,0.1

Type RM Length L Ch R = 1 ,16459.2 ,83.25,91.44,90.34
XS GIS Cut Line= 5
     610524.6339    4336827.1134     610650.0653    4336896.8049
     610815.4302    4336896.8049     610863.0553    4336909.2887
     610932.4884    4336964.5419
#Sta/Elev= 30
       0  494.98    6.11  491.57    9.16  489.41   15.27   484.7   18.32  481.72
   21.37  478.24   24.42  476.89   30.53  476.68   36.64  477.01   39.69  476.07
   42.74  474.24    51.9  470.46   58.01  468.88   61.06  468.39   88.54  468.12
   183.3  468.15  290.48  469.73  358.09  469.24  388.69   469.3  391.75  469.16
  397.87  468.21  410.11  470.03  413.17  470.59  416.23  472.12  419.29  475.38
  422.35  477.98  434.59  487.21  440.71   490.4  443.77  494.35  446.83  497.07
#Mann= 3 , 0 , 0
       0      .1       0   61.06    .041       0  290.48      .1       0
Bank Sta=61.06,290.48
XS Rating Curve= 0 ,0
Exp/Cntr=0.3,0.1

Type RM Length L Ch R = 1 ,16367.76,57.44,91.44,111.34
XS GIS Cut Line= 6
     610478.5395    4336894.0601     610632.3382    4336988.2449
     610746.1093    4336988.2449     610795.2038     4336985.221
     610844.0053    4336996.0722     610874.0202    4337021.6946
#Sta/Elev= 30
       0  494.06    3.06  493.14   12.23  485.99   15.28  483.37   18.34  479.65
    21.4  477.87   24.45  477.62   33.62  478.21   36.68  477.98   39.74  476.81
   42.79  474.51   45.85   473.3   48.91  472.19   51.96   471.7   55.02   470.8
   61.13  468.52   64.19  467.81   67.25   467.8   94.76  468.12   343.3  468.21
  384.48  468.16  387.42  468.26  390.36  468.79   393.3  470.07  396.33  472.67
  399.37  474.01  417.58  485.63  420.62  488.34  423.65  490.43  432.76  495.55
#Mann= 3 , 0 , 0
       0      .1       0   64.19    .041       0   343.3      .1       0
Bank Sta=64.19,343.3
XS Rating Curve= 0 ,0
Exp/Cntr=0.3,0.1

Type RM Length L Ch R = 1 ,16276.32,44.34,91.44,110.08
XS GIS Cut Line= 5
     610452.7713    4336946.9163     610532.6232    4336990.6813
     610642.2957    4337076.4906     610740.1991    4337081.6434
      610817.294     4337111.539
#Sta/Elev= 30
       0  485.84    6.07  481.43    9.11  479.39   12.14  478.04   15.18   477.9
   18.21  478.39   24.28  478.72   27.32  478.39   30.35   477.4   33.39  476.06
   36.42  474.58   39.46  472.47   48.56  469.02   52.17     468   54.64  467.76
   78.92  467.79   91.06  468.12  282.39  468.13  349.79   468.9  355.91  469.14
  362.04  470.11  368.16   471.7  371.23  472.19  374.29   472.9  383.48  475.53
  386.54  477.06  398.79  480.81  404.91  483.15  407.98  485.07  411.04  487.26
#Mann= 3 , 0 , 0
       0      .1       0   52.17    .041       0  349.79      .1       0
Bank Sta=52.17,349.79
XS Rating Curve= 0 ,0
Exp/Cntr=0.3,0.1

Type RM Length L Ch R = 1 ,16184.88,121.12,91.44,89.4
XS GIS Cut Line= 4
     610425.0431    4336981.6449     610498.9497    4337021.5182
     610713.7107    4337187.4705     610772.4296    4337215.9593
#Sta/Elev= 30
       0  484.76       3  482.46       6  480.59       9  478.83      12  477.52
      15  477.12   17.99  477.15   23.99  478.12   26.99  478.27   29.99  477.98
   41.99   475.3   47.99   472.1   57.26  468.23   59.98  467.82   62.98  467.78
   74.98  467.81   87.03  468.27   93.13  468.12  291.34  468.12  355.81  469.35
  367.25  470.45  379.12  471.28  382.08  471.71  385.05  472.42  388.02   473.5
  390.98   475.3  405.82  480.39  408.78  481.67  411.75  483.42  420.65  486.22
#Mann= 3 , 0 , 0
       0      .1       0   57.26    .041       0  355.81      .1       0
Bank Sta=57.26,355.81
XS Rating Curve= 0 ,0
Exp/Cntr=0.3,0.1

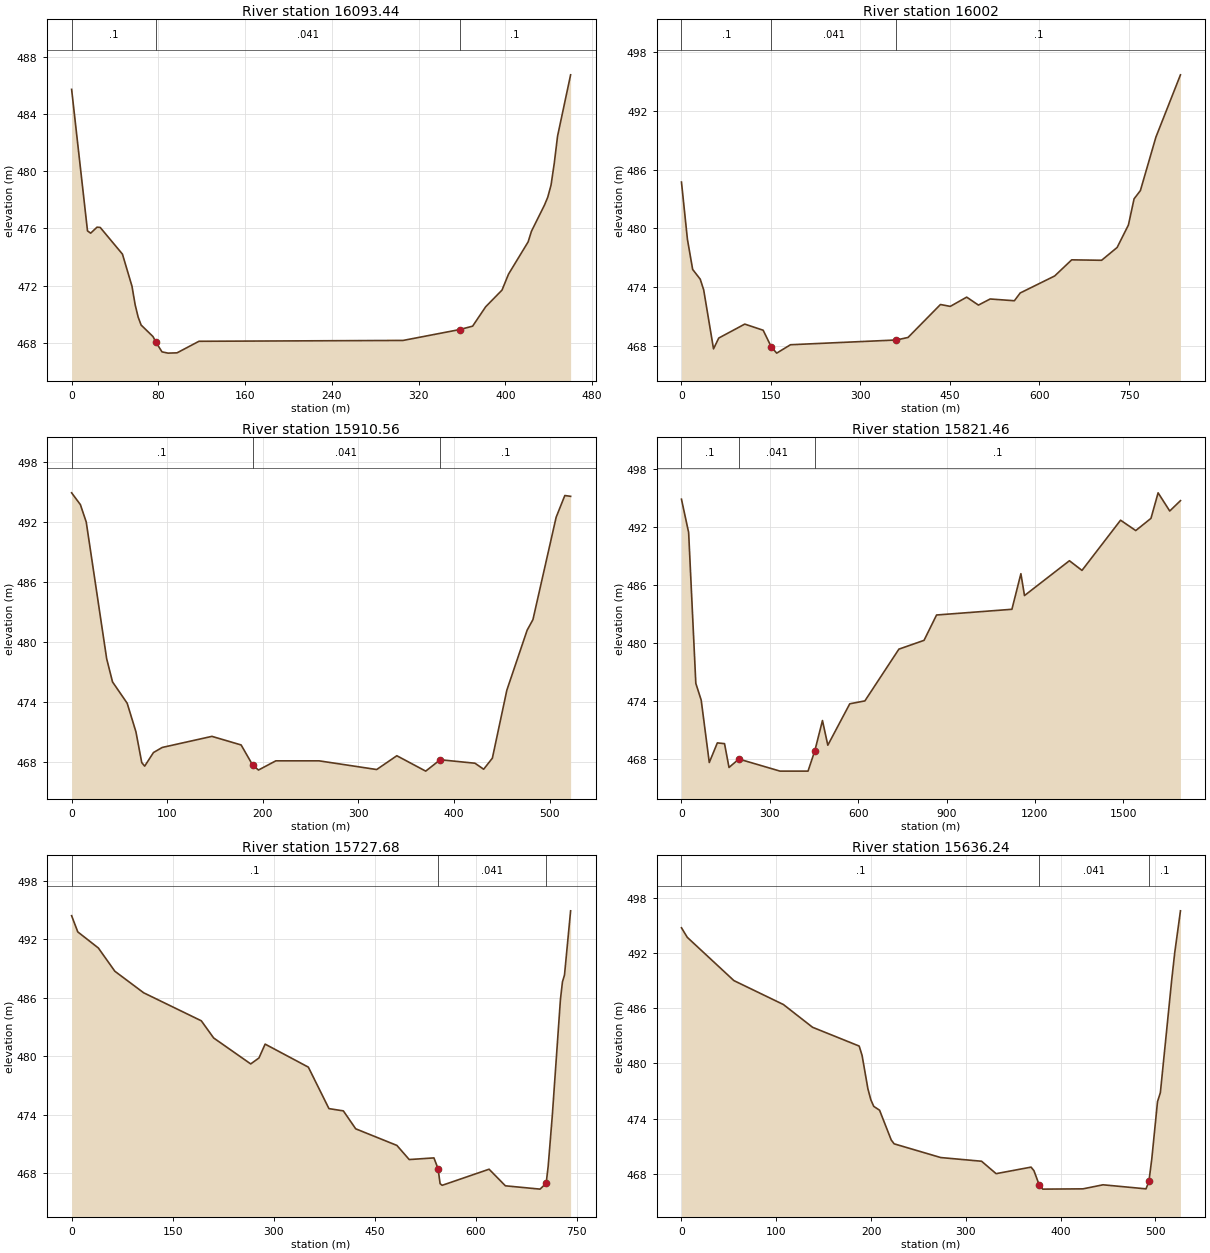
Type RM Length L Ch R = 1 ,16093.44,95.92,91.44,89.87
XS GIS Cut Line= 6
     610364.0781    4337071.8343     610412.7755    4337104.4523
     610461.9881    4337107.6273     610559.5077    4337198.0746
     610654.7745    4337253.8404     610743.9122    4337315.6591
#Sta/Elev= 30
       0  485.75   14.65  475.83   17.58  475.67   23.44  476.09   26.38  476.07
   46.89   474.2   55.68  471.95   58.61  470.65   61.36  469.79    64.1  469.23
   75.08  468.42   77.82  468.02   83.35  467.35   88.91  467.26   97.26  467.28
  117.46  468.09  305.79  468.15  357.81  468.91  369.87  469.15  381.92  470.51
  396.99  471.68  403.01   472.8  421.09  475.06  424.11   475.8  436.16  477.64
  439.17  478.19  442.18  479.03   445.2  480.58  448.21  482.47  460.26  486.77
#Mann= 3 , 0 , 0
       0      .1       0   77.82    .041       0  357.81      .1       0
Bank Sta=77.82,357.81
XS Rating Curve= 0 ,0
Exp/Cntr=0.3,0.1

Type RM Length L Ch R = 1 ,16002   ,58.15,91.44,137.11
XS GIS Cut Line= 6
     610318.4654    4337135.8982     610399.1825    4337201.4223
      610433.694    4337204.0867610603.9921429044337332.54102063
610755.0419937954337453.09933912611030.5332108434337547.29243912
#Sta/Elev= 30
       0 484.732  10.018 478.873   18.76 475.809  31.466 474.812  37.253 473.718
  53.729 467.696  62.471 468.799 106.095 470.225 136.929 469.598  150.79 467.867
 159.623  467.26 182.728 468.117  360.08 468.602 379.701  468.86  434.06 472.226
 450.503 472.035 478.037 472.979 497.704 472.168 517.371  472.79 557.944  472.61
 567.691 473.403 625.524 475.142 654.032 476.789 704.149 476.743 730.141 478.051
 749.057 480.344  758.56  483.02 769.129 483.861 795.121 489.318 836.302 495.686
#Mann= 3 , 0 , 0
       0      .1       0  150.79    .041       0  360.08      .1       0
Bank Sta=150.79,360.08
XS Rating Curve= 0 ,0
Exp/Cntr=0.3,0.1

Type RM Length L Ch R = 1 ,15910.56,32.45,89.1,113.87
XS GIS Cut Line= 5
     610262.4147    4337166.6571     610406.6129    4337264.5531
     610440.1871    4337290.4015     610533.0009    4337397.3763
     610657.3328    4337503.8566
#Sta/Elev= 30
       0  494.94    9.17  493.76   15.29  492.02   36.69  478.32   42.81  476.01
    58.1  473.88   67.27  471.02   73.38  467.93   76.44  467.58   85.62  468.94
   94.79  469.45  146.77  470.56  177.32   469.7  189.42  467.68  195.48  467.19
  213.63  468.11  258.85  468.11  319.11  467.24  340.21  468.62  370.41  467.08
  385.57  468.22  421.95  467.87  431.04  467.27  440.14  468.38  455.29  475.19
  476.51  481.19  482.58  482.25  506.83  492.49  515.92  494.67  521.98  494.59
#Mann= 3 , 0 , 0
       0      .1       0  189.42    .041       0  385.57      .1       0
Bank Sta=189.42,385.57
XS Rating Curve= 0 ,0
Exp/Cntr=0.3,0.1

Type RM Length L Ch R = 1 ,15821.46,152.6,93.78,142.1
XS GIS Cut Line= 6
     610237.8084    4337186.0776     610395.2358    4337295.8799
      610447.745    4337451.0856     610862.8206    4338020.8192
     611230.5922    4338121.3611     611455.4885    4338047.2776
#Sta/Elev= 30
       0  494.83   24.37  491.39   48.75  475.79   67.03  474.06   94.45  467.61
  121.86  469.64  146.24  469.56  161.47   467.1  194.96  467.97  334.75  466.72
  429.73  466.72  453.04  468.85  478.82  471.95  496.97   469.4  571.49  473.68
  622.84  473.98  738.33  479.33  823.71  480.24   866.2  482.86 1122.11  483.45
 1152.62  487.13 1164.83  484.87 1317.35  488.47 1360.06  487.47 1491.06  492.66
 1542.66  491.59 1594.27  492.85 1618.56  495.49 1658.02  493.61 1694.45  494.68
#Mann= 3 , 0 , 0
       0      .1       0  194.96    .041       0  453.04      .1       0
Bank Sta=194.96,453.04
XS Rating Curve= 0 ,0
Exp/Cntr=0.3,0.1

Type RM Length L Ch R = 1 ,15727.68,104.58,91.44,40.19
XS GIS Cut Line= 3
     609902.2489    4337100.7288     610344.7635    4337438.2185
     610431.1664    4337601.4228
#Sta/Elev= 30
       0   494.4    9.17  492.74   39.75  491.09   64.21  488.71  107.02   486.5
  192.64  483.63  210.99  481.87  266.03  479.21  278.26  479.82  287.44  481.24
  351.65  478.88  382.23  474.63  403.63   474.4  421.98  472.56  483.14  470.86
  501.48  469.41  538.18  469.58  544.29  468.48  547.35  466.94  550.41  466.77
   620.1  468.42  644.32  466.72  695.78  466.38  704.86  466.97  707.89  468.74
  713.94  473.87  726.05   485.8  729.08  487.62  732.11  488.32  741.19   494.9
#Mann= 3 , 0 , 0
       0      .1       0  544.29    .041       0  704.86      .1       0
Bank Sta=544.29,704.86
XS Rating Curve= 0 ,0
Exp/Cntr=0.3,0.1

Type RM Length L Ch R = 1 ,15636.24,77.52,91.44,103.88
XS GIS Cut Line= 4
     609964.6907    4337321.3917     610296.1641    4337527.5758
     610367.6126    4337566.9957     610392.8906    4337615.2779
#Sta/Elev= 30
       0  494.74    6.15   493.7   55.33     489  107.58   486.4  138.32  483.93
   187.5  481.89  190.57  480.87  196.72  477.24  199.79  476.06  202.87  475.34
  209.02  474.92  221.31  471.69  224.38  471.27  273.56  469.78   316.6  469.38
  331.97  468.03  368.85  468.74  371.92  468.35  377.45   466.8  381.15  466.35
  423.61  466.38  444.77  466.82  490.13  466.38  493.16  467.18  496.19   469.6
  502.25  475.85  505.27  476.83  517.38  489.22  520.41  492.02  526.47  496.58
#Mann= 3 , 0 , 0
       0      .1       0  377.45    .041       0  493.16      .1       0
Bank Sta=377.45,493.16
XS Rating Curve= 0 ,0
Exp/Cntr=0.3,0.1

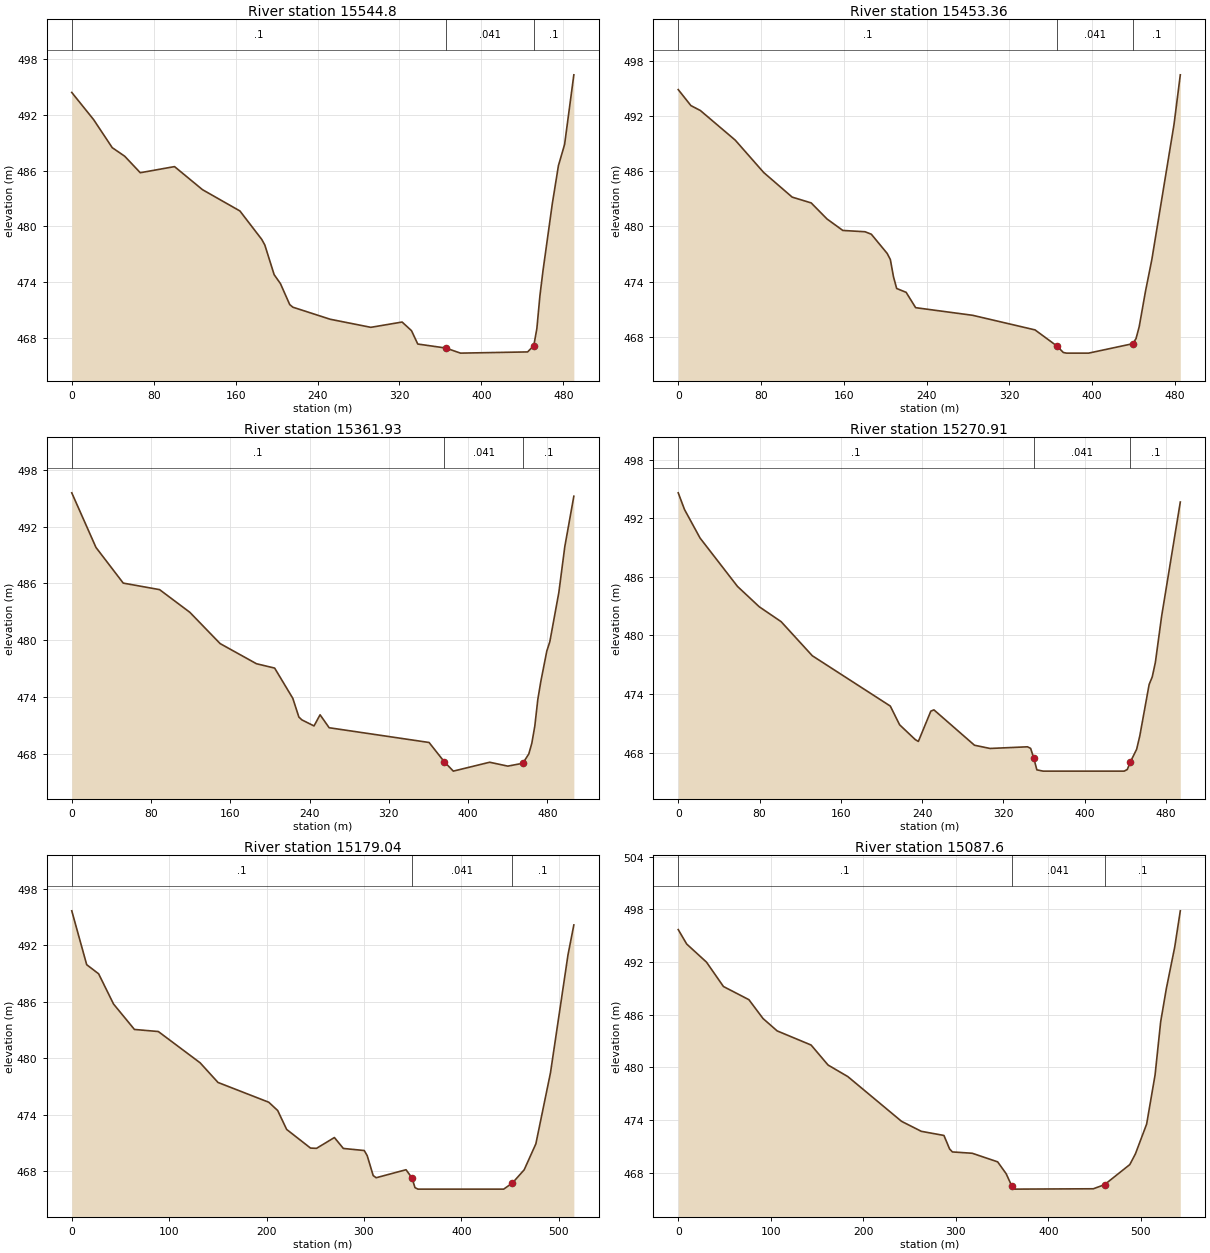
Type RM Length L Ch R = 1 ,15544.8 ,80.72,91.44,89.02
XS GIS Cut Line= 6
     609957.2824    4337342.5585     610167.5699    4337512.9064
      610227.666    4337582.1772     610252.8572    4337596.1218
     610274.7892    4337620.7247     610313.2317    4337674.6271
#Sta/Elev= 30
       0  494.44   21.29  491.52   39.53  488.49   51.69  487.57    66.9  485.79
  100.35  486.45  127.71  483.96   164.2  481.67  185.49  478.61  188.53     478
  197.65   474.8  203.73  473.85  212.85  471.58  215.89   471.3  252.38     470
  292.03  469.13  322.59   469.7  331.76  468.77  337.88  467.33  365.21   466.9
  379.61  466.35  445.15  466.48  451.17  467.15  454.18     469  457.19  472.56
   460.2  475.26  469.23  482.43  475.25  486.56  481.26  488.84  490.29  496.34
#Mann= 3 , 0 , 0
       0      .1       0  365.21    .041       0  451.17      .1       0
Bank Sta=365.21,451.17
XS Rating Curve= 0 ,0
Exp/Cntr=0.3,0.1

Type RM Length L Ch R = 1 ,15453.36,93.52,91.43,90.42
XS GIS Cut Line= 4
     609920.2406    4337371.1335     610136.7153    4337595.9136
     610158.6394    4337627.8457     610248.1108    4337728.2129
#Sta/Elev= 30
       0   494.9   12.24  493.16   21.42  492.62   55.07   489.4   82.61  485.87
  110.14  483.19   128.5  482.56   143.8  480.81  159.09  479.56  180.51  479.42
  186.63  479.15  201.93  477.06  204.99   476.4  208.05  474.51  211.11  473.24
  220.28  472.82  229.46  471.15  284.53  470.32  344.84  468.73  366.08  466.97
  372.19  466.27  375.25   466.2  396.64   466.2  439.42  467.23  442.48  467.79
  445.53  469.08  451.65  472.96  457.76   476.4  479.15  491.09  485.26  496.51
#Mann= 3 , 0 , 0
       0      .1       0  366.08    .041       0  439.42      .1       0
Bank Sta=366.08,439.42
XS Rating Curve= 0 ,0
Exp/Cntr=0.3,0.1

Type RM Length L Ch R = 1 ,15361.93,92.84,91.02,91.53
XS GIS Cut Line= 3
     609847.2155    4337415.5836     610137.7995    4337741.8834
     610186.9411    4337791.2927
#Sta/Elev= 30
       0  495.58   24.44   489.8   51.94  486.03   88.61  485.34  119.16  482.94
  149.72  479.63  186.38   477.5  204.72  477.04  223.05  473.84  229.16  471.86
  232.22  471.56  244.44  470.92  250.55   472.1  259.72  470.73  360.55  469.17
  375.82  467.14  384.99  466.14  421.66  467.08  439.96  466.67  455.11  466.97
  461.17  467.96   464.2  469.08  467.23   470.9  470.26  473.72  473.29  475.62
  479.35  478.85  482.38  479.83  491.47  485.03  497.53  489.91  506.62  495.22
#Mann= 3 , 0 , 0
       0      .1       0  375.82    .041       0  455.11      .1       0
Bank Sta=375.82,455.11
XS Rating Curve= 0 ,0
Exp/Cntr=0.3,0.1

Type RM Length L Ch R = 1 ,15270.91,95.48,91.86,89.36
XS GIS Cut Line= 2
     609787.8682    4337500.8226     610125.7281    4337861.4925
#Sta/Elev= 30
       0   494.6    6.14   492.9   21.49  489.97   58.32  485.02   79.81  482.93
   101.3  481.41  131.99  477.92  208.73  472.77  217.94  470.85  233.29  469.34
  236.36  469.15  248.63  472.25   251.7  472.38  291.61  468.76  306.96  468.43
  343.79   468.6  346.86  468.44  349.93  467.46     353  466.24  359.14  466.11
  438.95  466.11  442.02  466.28  445.09  467.06  451.22  468.35  454.29   469.7
   463.5  474.97  466.57  475.76  469.64  477.23  475.78  481.95   494.2  493.66
#Mann= 3 , 0 , 0
       0      .1       0  349.93    .041       0  445.09      .1       0
Bank Sta=349.93,445.09
XS Rating Curve= 0 ,0
Exp/Cntr=0.3,0.1

Type RM Length L Ch R = 1 ,15179.04,113.42,91.44,79.12
XS GIS Cut Line= 4
      609709.816     4337576.229     609981.4384    4337841.9334
     610006.5398    4337868.4969      610080.994    4337933.7342
#Sta/Elev= 30
       0  495.67   15.32  489.95   27.58  488.98    42.9  485.77   64.35  483.07
   88.86  482.85  131.76  479.53  150.15  477.44  202.24  475.34  211.44  474.46
  220.63  472.45  245.14  470.47  251.27  470.44  269.66  471.59  278.85  470.43
   300.3  470.21  303.36  469.66  309.49  467.55  312.56  467.32   343.2  468.17
  349.33   467.3  352.39  466.27  355.46  466.11  443.52  466.11  452.51  466.77
  464.51  468.16  476.51  470.92  491.51  478.46  509.51     491  515.51  494.17
#Mann= 3 , 0 , 0
       0      .1       0  349.33    .041       0  452.51      .1       0
Bank Sta=349.33,452.51
XS Rating Curve= 0 ,0
Exp/Cntr=0.3,0.1

Type RM Length L Ch R = 1 ,15087.6 ,117.62,91.44,76.43
XS GIS Cut Line= 4
     609617.2116    4337682.0625     609885.4995     4337904.178
     609914.8876    4337912.7922     610057.8915    4337992.5984
#Sta/Elev= 30
       0   495.7    9.17  494.05   30.55  491.99   48.88  489.21   76.38  487.71
   91.66  485.56  106.93  484.15   143.6  482.54  161.93  480.26  183.32  478.94
  241.37  473.84  262.75   472.7   287.2  472.23  293.31  470.69  296.36  470.35
  317.75   470.2  345.25  469.22  354.43  467.87  360.55  466.46  363.61  466.11
  448.68  466.15  460.81  466.62   488.1  468.91  494.17  470.13   506.3  473.53
   515.4  479.12  521.46  485.19  527.53  488.94  536.63   493.7  542.69  497.84
#Mann= 3 , 0 , 0
       0      .1       0  360.55    .041       0  460.81      .1       0
Bank Sta=360.55,460.81
XS Rating Curve= 0 ,0
Exp/Cntr=0.3,0.1

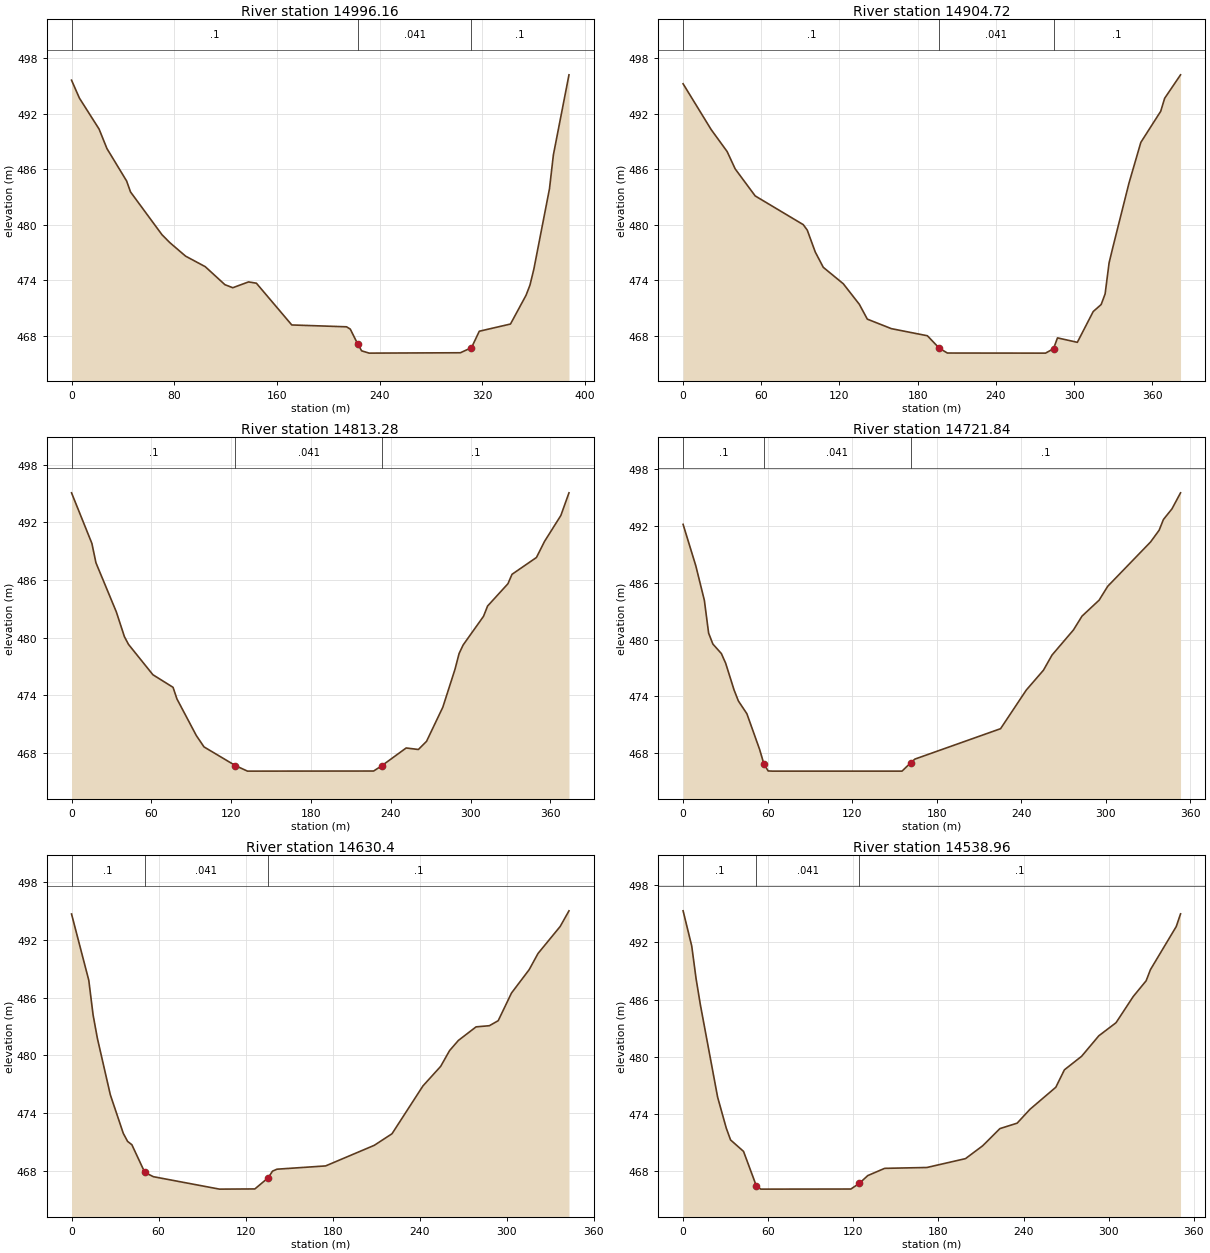
Type RM Length L Ch R = 1 ,14996.16,75.26,91.44,98.05
XS GIS Cut Line= 6
     609658.2221    4337926.8026     609850.9574    4338005.7173
     609895.0246    4338006.6381     609902.9755     4338011.707
     609936.2878    4338012.6252     610022.4217    4338045.5319
#Sta/Elev= 30
       0  495.65    6.13  493.71   21.44  490.36   27.56  488.25   42.88  484.74
   45.94  483.55   70.44  478.92   76.57  478.06   88.82   476.6  104.13  475.46
  119.45  473.51  125.57  473.18  137.82  473.81  143.95  473.67  171.51  469.15
  214.14  468.95  217.08   468.7  222.96  467.06   225.9  466.35  231.77   466.1
  302.81  466.14  311.46  466.69  317.53  468.47  341.83  469.25  353.97  472.37
  357.01  473.47  360.05  475.21  372.19  483.89  375.23  487.56  387.38  496.23
#Mann= 3 , 0 , 0
       0      .1       0  222.96    .041       0  311.46      .1       0
Bank Sta=222.96,311.46
XS Rating Curve= 0 ,0
Exp/Cntr=0.3,0.1

Type RM Length L Ch R = 1 ,14904.72,83.57,91.44,89.13
XS GIS Cut Line= 4
      609659.545    4338004.8549     609868.0608    4338087.6448
     609899.4286    4338104.3174     610012.7645    4338149.0531
#Sta/Elev= 30
       0  495.26   21.51  490.31   33.81  487.92   39.95  486.05   55.32  483.12
    92.2  480.01   95.27  479.42  101.42  477.05  107.57  475.39  122.93  473.61
  135.22  471.39  141.37  469.78  159.81  468.75  187.47  467.98  196.69  466.62
  202.84  466.11  278.15   466.1  284.24  466.58  287.29  467.75  302.52  467.27
   314.7   470.6   320.8  471.36  323.84  472.51  326.89  475.87  329.93  477.64
  342.12  484.49  351.26  488.92  366.49  492.28  369.53  493.69  381.72  496.23
#Mann= 3 , 0 , 0
       0      .1       0  196.69    .041       0  284.24      .1       0
Bank Sta=196.69,284.24
XS Rating Curve= 0 ,0
Exp/Cntr=0.3,0.1

Type RM Length L Ch R = 1 ,14813.28,115.94,91.44,83.34
XS GIS Cut Line= 6
     609686.0034    4338104.8676     609756.8775    4338123.9426
     609788.4237    4338144.8038      609821.066    4338166.2203
     609864.5749     4338189.346     610033.1374    4338233.9845
#Sta/Elev= 30
       0  495.06   15.29   489.8   18.35  487.78   33.64  482.68   39.76  480.09
   42.81  479.29   61.16  476.13   76.31  474.82   79.21  473.62   93.76  469.81
   99.58  468.62  123.23  466.67  132.24   466.1  227.06  466.11  233.18  466.66
  251.54  468.51  260.71  468.35  266.83   469.2  279.07  472.75  288.25  476.71
  291.31  478.34  294.36  479.23  309.66  482.21  312.72  483.28  328.02   485.6
  331.07  486.58  349.43  488.33  355.55  490.01  367.78   492.7   373.9  495.06
#Mann= 3 , 0 , 0
       0      .1       0  123.23    .041       0  233.18      .1       0
Bank Sta=123.23,233.18
XS Rating Curve= 0 ,0
Exp/Cntr=0.3,0.1

Type RM Length L Ch R = 1 ,14721.84,102.34,91.44,71.65
XS GIS Cut Line= 5
     609709.7982    4338247.0214     609781.8036    4338254.7748
     609842.1429    4338267.4071     609864.8444    4338276.1256
     610056.4208    4338310.1846
#Sta/Elev= 30
       0  492.16    9.05  487.77   15.09  484.14   18.11  480.68   21.12  479.53
   27.16  478.52   30.18  477.51   36.21  474.66   39.23  473.52   45.26  472.17
   54.32  468.39   57.33  466.87   60.35  466.13   63.37  466.11  155.35  466.11
  161.43  466.98  164.47  467.38  225.27  470.59  243.52  474.67  255.68  476.76
  261.76  478.36  276.96  481.01  283.04  482.47   295.2  484.16  301.28  485.62
  331.69   490.3  337.77  491.54  340.81  492.67  346.89   493.8  352.97  495.49
#Mann= 3 , 0 , 0
       0      .1       0   57.33    .041       0  161.43      .1       0
Bank Sta=57.33,161.43
XS Rating Curve= 0 ,0
Exp/Cntr=0.3,0.1

Type RM Length L Ch R = 1 ,14630.4 ,95.38,91.44,78.02
XS GIS Cut Line= 3
     609721.9599    4338360.7996     609786.6496    4338351.3878
     610063.8292     4338336.643
#Sta/Elev= 30
       0  494.68   11.89   487.8   14.86   484.2   17.83  481.76   26.74  475.91
   35.66  471.91   38.63  471.07    41.6  470.72   50.51  467.84   56.46   467.4
  101.97  466.11  126.38  466.13  135.53  467.28  138.58  467.98  141.63  468.18
  175.18  468.52  208.73  470.66  220.93  471.86  242.28  476.83  254.49  478.86
  260.59  480.49  266.69  481.55  278.89  482.96  288.04  483.08  294.14   483.6
  303.29  486.47  315.49   488.9  321.59  490.58  336.84  493.38  342.94  495.01
#Mann= 3 , 0 , 0
       0      .1       0   50.51    .041       0  135.53      .1       0
Bank Sta=50.51,135.53
XS Rating Curve= 0 ,0
Exp/Cntr=0.3,0.1

Type RM Length L Ch R = 1 ,14538.96,91.52,91.44,97.78
XS GIS Cut Line= 4
     609736.8834     4338459.734     609834.3864     4338435.712
     609905.3477    4338413.3123     610077.5875    4338377.9181
#Sta/Elev= 30
       0  495.31    6.09  491.62    9.13  488.21   12.17  485.46   24.34  475.76
   30.43  472.51   33.47  471.27    42.6  470.07   51.73  466.41   54.77  466.11
  118.28  466.12  124.23  466.72  130.18  467.53  142.09  468.29  171.85  468.38
  199.08  469.31  211.21  470.66  223.34  472.46  235.47  473.03  244.56  474.49
  262.75   476.8  268.81  478.63  280.94  480.05  293.07   482.2  305.19  483.57
  317.32  486.32  326.42  487.97  329.45  489.14  347.64  493.66  350.67  494.99
#Mann= 3 , 0 , 0
       0      .1       0   51.73    .041       0  124.23      .1       0
Bank Sta=51.73,124.23
XS Rating Curve= 0 ,0
Exp/Cntr=0.3,0.1

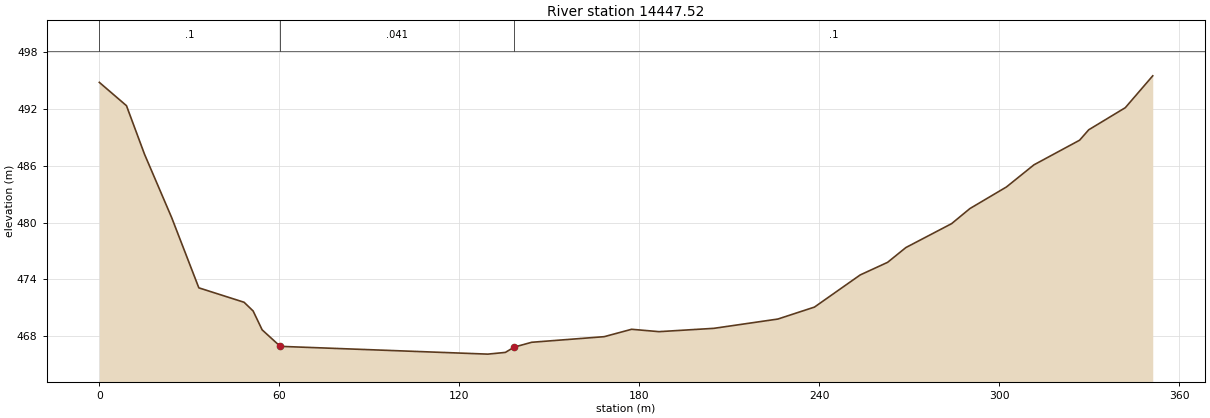
Type RM Length L Ch R = 1 ,14447.52,90.43,91.44,79.68
XS GIS Cut Line= 4
     609745.8315    4338551.7037     609865.9043    4338522.1212
     609892.1186    4338519.1459     610087.1126    4338469.5523
#Sta/Elev= 30
       0  494.78    9.05  492.32   15.08  487.19   24.13  480.51   33.18  473.11
   48.26  471.59   51.28  470.67   54.29  468.68   60.32  466.94  129.53  466.12
  135.39   466.3  138.32  466.86  144.18  467.37  168.34  467.96  177.48  468.74
  186.63  468.49  204.92  468.84  226.26  469.82  238.45  471.08   253.7  474.47
  262.84   475.8  268.94  477.36  284.18  479.88  290.28  481.47  302.47  483.75
  311.62  486.08  326.86  488.68  329.91  489.78   342.1  492.11  351.25  495.47
#Mann= 3 , 0 , 0
       0      .1       0   60.32    .041       0  138.32      .1       0
Bank Sta=60.32,138.32
XS Rating Curve= 0 ,0
Exp/Cntr=0.3,0.1