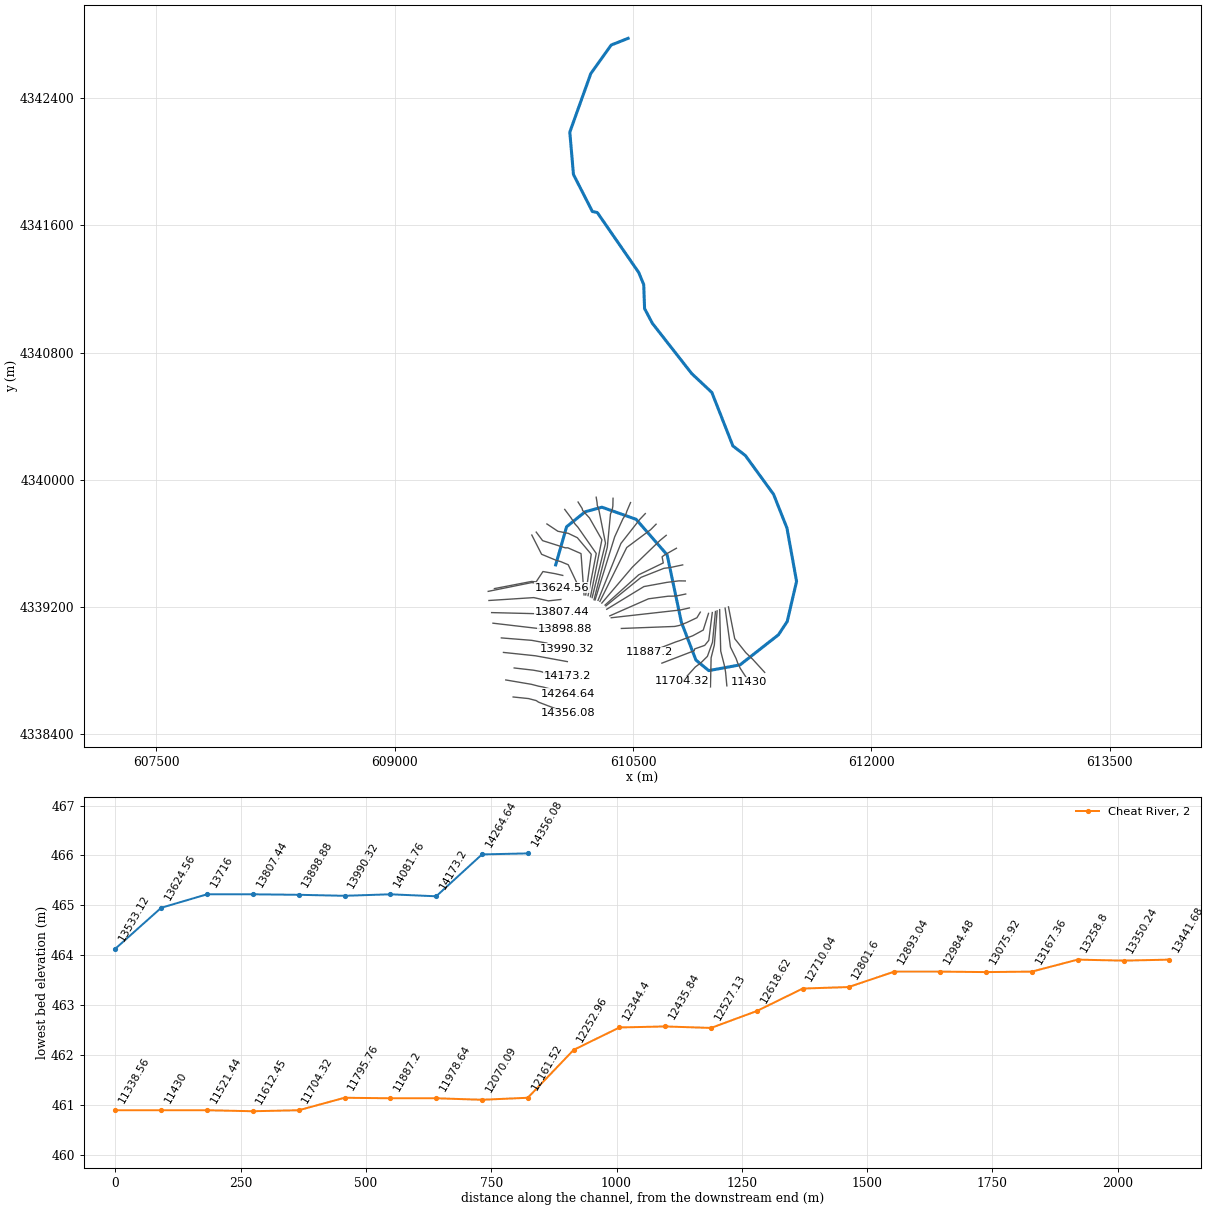
HEC-RAS study CheatRiver.prj: CheatRiver

--- CheatRiver.g01 (geometry) --- (continued)

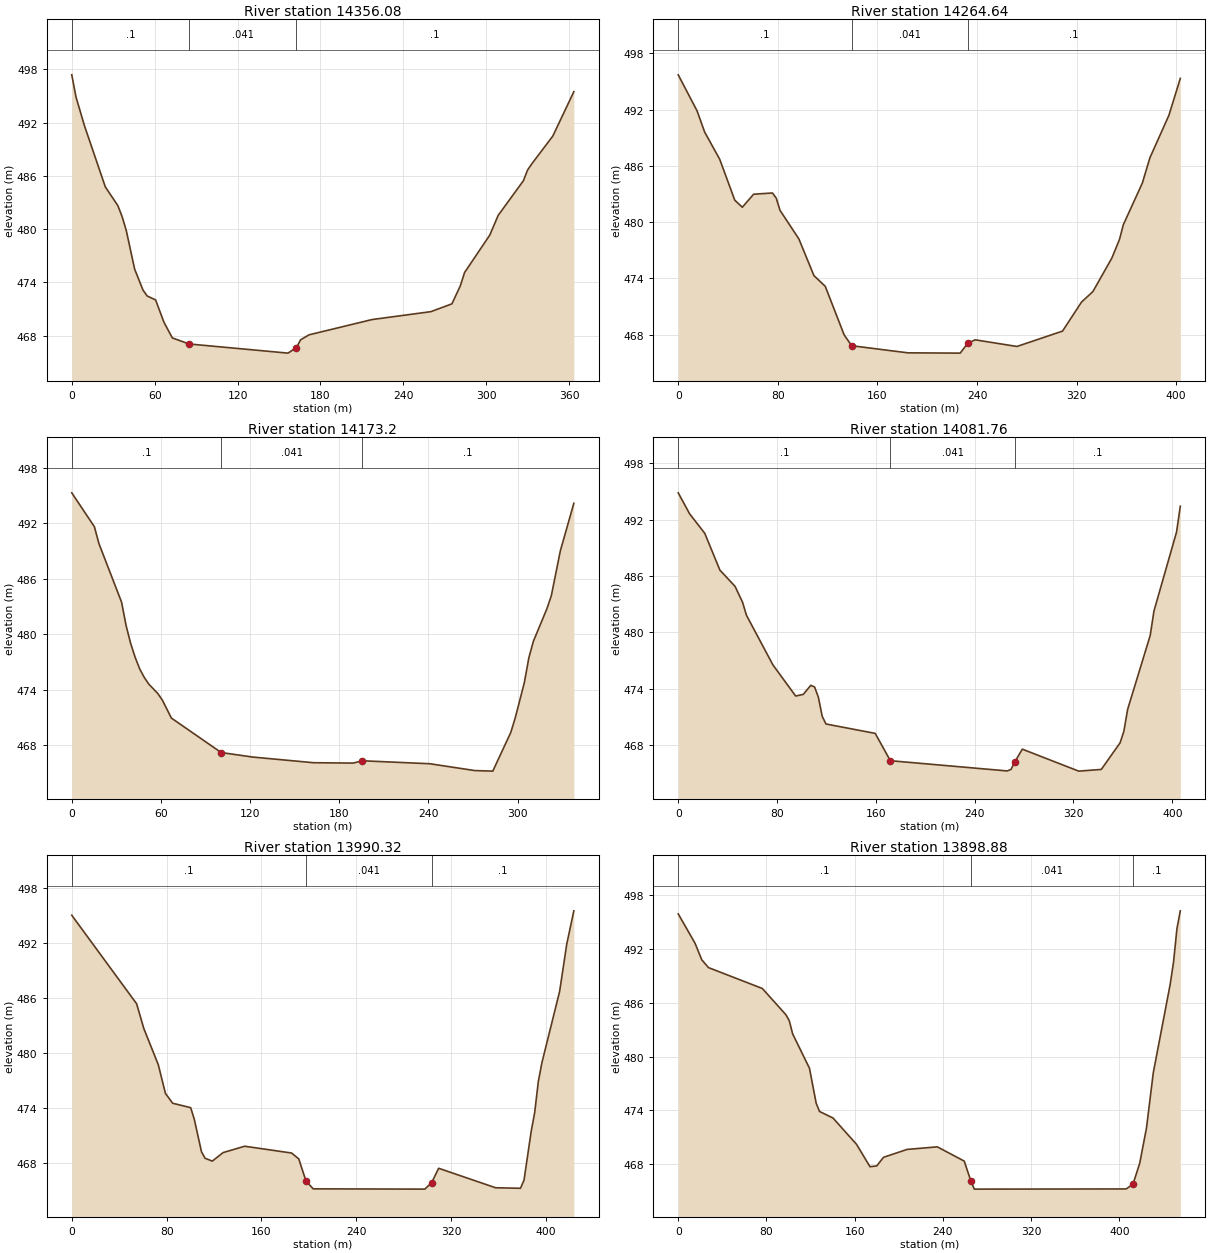
Type RM Length L Ch R = 1 ,14356.08,93.18,91.44,101.06
XS GIS Cut Line= 5
     609745.7994    4338632.2714     609842.3855     4338622.319
     609891.0686    4338609.6178     609906.2517    4338599.4691
     610091.0813    4338529.0837
#Sta/Elev= 30
       0  497.37    3.03   494.9     9.1  491.68   24.27  484.76   33.38  482.64
   36.41  481.43   39.45  479.85   45.51   475.5   51.58  473.13   54.62  472.47
   60.69  472.03   66.75  469.51   72.82  467.75   84.96  467.07  156.54  466.04
  162.63  466.67  165.67  467.54  171.76   468.1   217.4  469.82     260  470.71
  275.21  471.59   281.3  473.63  284.34  475.11   302.6  479.33  308.68  481.55
  326.94  485.45  329.98  486.66  333.02  487.35  348.24  490.48  363.45  495.47
#Mann= 3 , 0 , 0
       0      .1       0   84.96    .041       0  162.63      .1       0
Bank Sta=84.96,162.63
XS Rating Curve= 0 ,0
Exp/Cntr=0.3,0.1

Type RM Length L Ch R = 1 ,14264.64,88.14,91.44,91.56
XS GIS Cut Line= 5
     609699.4972    4338739.4279     609860.6973    4338712.0423
     609907.0971    4338699.9369     609933.6639    4338695.0518
     610092.4042    4338650.7923
#Sta/Elev= 30
       0  495.72   15.14  491.87    21.2  489.62   33.31  486.71   45.42  482.34
   51.48  481.59   60.56  482.98    75.7  483.11   78.73  482.56   81.75  481.26
   96.89  478.21  109.01  474.29  118.09  473.15  133.23  467.98  139.29  466.81
  184.49  466.05  226.47  466.02  232.47  467.06  238.47  467.44  272.04  466.73
  308.67  468.37  323.92  471.47  333.08  472.59  348.34  476.18  354.44  478.16
  357.49  479.72  372.75  484.16  378.86  486.87  394.11   491.4  403.27  495.34
#Mann= 3 , 0 , 0
       0      .1       0  139.29    .041       0  232.47      .1       0
Bank Sta=139.29,232.47
XS Rating Curve= 0 ,0
Exp/Cntr=0.3,0.1

Type RM Length L Ch R = 1 ,14173.2 ,91.39,91.44,95.05
XS GIS Cut Line= 5
      609752.414    4338814.8343     609873.4951    4338800.8796
     609922.2673    4338791.9788     609944.8369    4338783.8179
     610086.1766     4338766.376
#Sta/Elev= 30
       0  495.29   15.24  491.62   18.28   489.8   33.52  483.46   36.56  480.93
   39.61  479.01   42.66  477.49   45.71  476.24   48.75  475.33    51.8   474.6
   57.89  473.58   60.94  472.87   67.04  470.92  100.55  467.19  121.88   466.7
  162.71  466.09  189.46  466.05  195.46   466.3  240.91  465.98  271.21  465.24
  283.33  465.18  295.45  469.37  298.48  470.97  304.54  474.74  307.57  477.42
   310.6  479.21  319.69  482.73  322.72  484.16  328.78  489.01  337.87  494.16
#Mann= 3 , 0 , 0
       0      .1       0  100.55    .041       0  195.46      .1       0
Bank Sta=100.55,195.46
XS Rating Curve= 0 ,0
Exp/Cntr=0.3,0.1

Type RM Length L Ch R = 1 ,14081.76,94.08,91.44,82.17
XS GIS Cut Line= 3
     609684.9451    4338912.7303     609886.2345    4338891.5049
     610087.0053     4338854.865
#Sta/Elev= 30
       0  494.86     9.2  492.63   21.47  490.55   33.73  486.63      46   484.9
   52.13  483.19    55.2  481.83   76.67  476.53   95.07  473.22   101.2  473.39
  107.34  474.36   110.4  474.18  113.47  473.09  116.54  471.07   119.6  470.24
  159.47  469.24  171.74  466.33  266.37  465.24  269.42   465.4  272.47  466.19
  278.56  467.56  324.25  465.22  342.52   465.4  357.76  468.24   360.8  469.47
  363.85   471.8  382.12  479.67  385.17  482.28  403.45  490.69  406.49  493.43
#Mann= 3 , 0 , 0
       0      .1       0  171.74    .041       0  272.47      .1       0
Bank Sta=171.74,272.47
XS Rating Curve= 0 ,0
Exp/Cntr=0.3,0.1

Type RM Length L Ch R = 1 ,13990.32,79.22,91.44,121.71
XS GIS Cut Line= 5
     609671.7159    4339004.0117      609862.564    4338988.7749
     609958.5964    4338971.2494     609971.3173    4338959.4575
     610085.6876    4338934.7479
#Sta/Elev= 30
       0  495.01    54.7  485.37   60.78  482.67   72.94  478.75   79.01  475.61
   85.09  474.54  100.29  474.06  103.33   472.8   109.4  469.26  112.44  468.55
  118.52  468.24  127.64  469.17  145.87  469.86  185.38  469.12  191.46  468.48
  197.56  466.06  203.66  465.22  297.75  465.19  303.53   465.9  309.42  467.46
  357.42  465.34  378.42  465.28  381.43  466.18  387.43  471.45  390.43  473.55
  393.43  476.86  396.43  478.92  411.43  486.71  417.43  491.85  423.43  495.49
#Mann= 3 , 0 , 0
       0      .1       0  197.56    .041       0  303.53      .1       0
Bank Sta=197.56,303.53
XS Rating Curve= 0 ,0
Exp/Cntr=0.3,0.1

Type RM Length L Ch R = 1 ,13898.88,89.35,91.44,92.1
XS GIS Cut Line= 4
     609618.9755     4339096.669      609906.851     4339063.011
     610000.9936    4339075.0385     610069.8264    4339059.6272
#Sta/Elev= 30
       0  495.94   15.25  492.66   21.36  490.81   27.46  489.94   76.27  487.61
   97.63  484.68  100.68  484.02  103.73  482.55  118.99  478.71  125.09   474.8
  128.14  473.88  140.34  473.15   161.7  470.21   173.9  467.71     180   467.8
  186.11  468.76  207.46  469.64  234.92  469.93  259.33  468.34  265.43  466.09
  268.48  465.21  406.21  465.23  412.35  465.76  418.48   468.1  424.61  472.04
  430.75  478.18  446.08  488.06  449.15  490.57  452.21  494.27  455.28  496.28
#Mann= 3 , 0 , 0
       0      .1       0  265.43    .041       0  412.35      .1       0
Bank Sta=265.43,412.35
XS Rating Curve= 0 ,0
Exp/Cntr=0.3,0.1

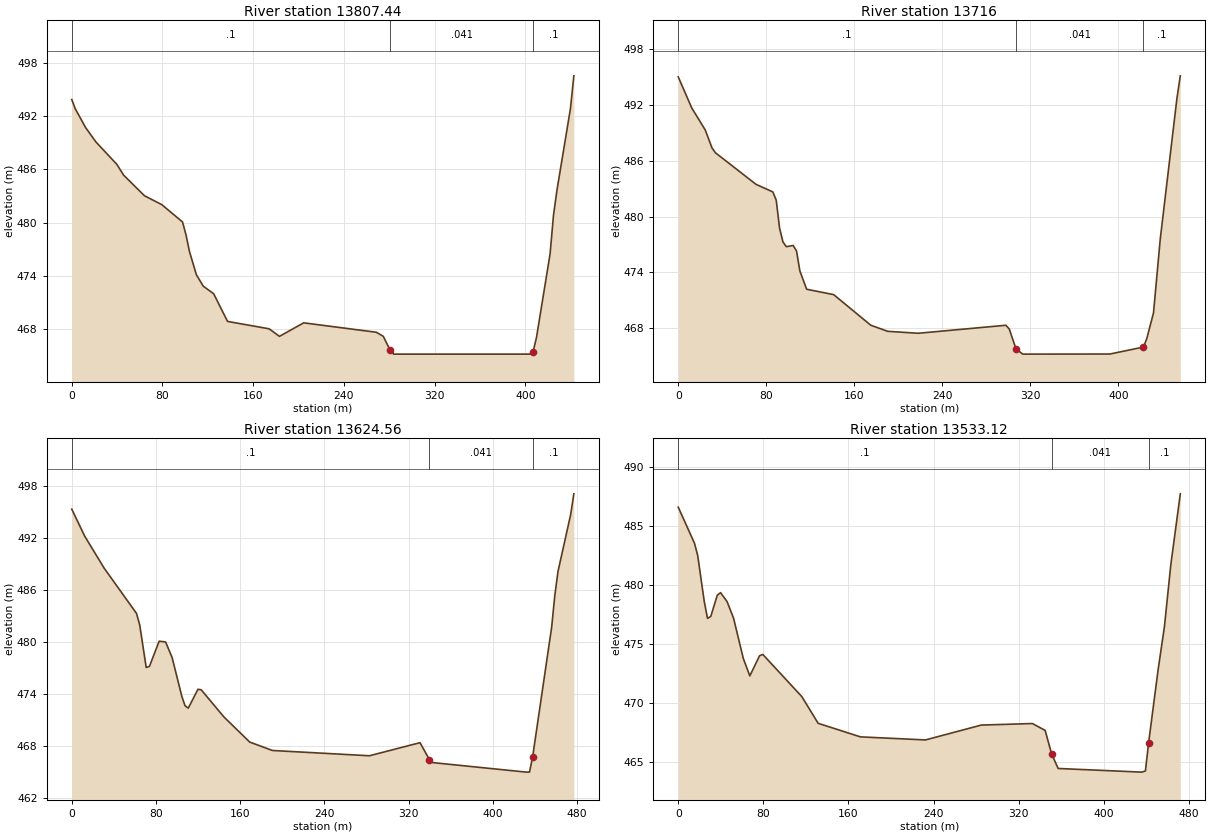
Type RM Length L Ch R = 1 ,13807.44,99.89,91.44,79.87
XS GIS Cut Line= 4
     609610.5088    4339163.3441     609909.5962    4339155.9961
     609989.9798     4339162.925     610052.8817    4339164.0033
#Sta/Elev= 30
       0  493.86    3.05  492.83   12.21  490.71   21.37  489.08   39.69  486.58
   45.79  485.35   64.11  483.04   79.37  482.04   97.69  480.09  100.74  478.64
   103.8  476.77   109.9  474.15  116.01  472.86  125.17  472.01  137.38   468.9
  174.01  468.07  183.17  467.22  204.54  468.74  268.65  467.68  274.76  467.22
  280.86  465.63  283.91  465.22  403.83  465.22  406.82  465.49  409.82  467.09
   421.8  476.48   424.8  480.81  427.79  483.59  439.78  492.85  442.77  496.53
#Mann= 3 , 0 , 0
       0      .1       0  280.86    .041       0  406.82      .1       0
Bank Sta=280.86,406.82
XS Rating Curve= 0 ,0
Exp/Cntr=0.3,0.1

Type RM Length L Ch R = 1 ,13716   ,96.71,91.44,77.89
XS GIS Cut Line= 4
     609593.5755    4339239.5443     609875.4984    4339257.7658
      609967.835    4339237.2465      610046.535    4339245.9664
#Sta/Elev= 30
       0     495   12.28  491.66   24.57  489.29   30.71  487.36   33.78  486.85
   70.63  483.46   85.98  482.64   89.05  481.76   92.12  478.73   95.19  477.26
   98.26  476.76  104.41  476.89  107.48  476.31  110.55  474.15  116.69  472.19
  141.26  471.61  175.03  468.32  190.39  467.67  218.02  467.46  297.77  468.32
  300.82  467.92  306.92   465.8  313.02  465.22  392.33  465.23  422.78  465.98
  425.83  466.89  431.92  469.65  438.01  477.53  453.24  492.72  456.28  495.11
#Mann= 3 , 0 , 0
       0      .1       0  306.92    .041       0  422.78      .1       0
Bank Sta=306.92,422.78
XS Rating Curve= 0 ,0
Exp/Cntr=0.3,0.1

Type RM Length L Ch R = 1 ,13624.56,7.37,91.44,84.75
XS GIS Cut Line= 5
     609588.8243    4339296.9127     609862.9806    4339352.4179
     609922.5072    4339344.3722     609986.2384    4339320.7906
     610055.3948    4339320.2527
#Sta/Elev= 30
       0  495.32    12.3   492.2   30.74  488.51   61.48  483.28   64.55  481.94
    70.7  477.04   73.77  477.16   82.99  480.07   89.14  479.98   95.29  478.19
  104.51  473.72  107.58  472.62  110.66  472.34  119.88  474.52  122.95  474.46
  144.47  471.33  169.06  468.42  190.58  467.45  282.72  466.84  330.78  468.35
  339.79  466.38  342.74  466.05   431.8  464.95   434.8  464.96  437.81  466.75
  455.85  481.71  458.86  485.39  461.86  488.13  473.89   494.7   476.9  497.09
#Mann= 3 , 0 , 0
       0      .1       0  339.79    .041       0  437.81      .1       0
Bank Sta=339.79,437.81
XS Rating Curve= 0 ,0
Exp/Cntr=0.3,0.1

Type RM Length L Ch R = 1 ,13533.12,20.02,91.44,80.98
XS GIS Cut Line= 6
     609628.0391     4339314.455     609862.3474    4339359.5061
     609890.5255     4339356.728     609933.5349    4339421.8506
     610008.7612    4339408.5307     610058.2156    4339397.4226
#Sta/Elev= 30
       0   486.6   15.29  483.54   18.35  482.48   24.47   478.6   27.53  477.17
   30.59  477.33   36.71  479.13   39.77  479.35   45.88   478.6      52  477.19
   61.18  473.77    67.3  472.29   76.47     474   79.53  474.11  116.24  470.53
  131.54  468.27   171.3  467.12  232.48  466.86  284.92  468.12  332.95  468.25
  344.96  467.67  351.07  465.67  357.18  464.44  435.93  464.13  439.24  464.23
  442.23  466.61  451.17  472.81  457.13  476.48   463.1  481.71  472.04  487.73
#Mann= 3 , 0 , 0
       0      .1       0  351.07    .041       0  442.23      .1       0
Bank Sta=351.07,442.23
XS Rating Curve= 0 ,0
Exp/Cntr=0.3,0.1

River Reach=Cheat River     ,2
Reach XY= 30
     610013.6323    4339463.5057     610082.3542    4339703.5836
     610199.1066    4339797.8558     610304.5821    4339826.7507
     610520.0321    4339750.4395      610715.295    4339526.6015
     610804.6681    4339102.9783     610896.2704    4338864.6127
     610977.1238    4338798.1529     611174.0834    4338834.4501
     611415.3839     4339023.363     611470.9465    4339107.5007
     611529.6842    4339359.9137      611469.359    4339694.8768
     611385.2214    4339907.6023      611207.421    4340152.0778
     611128.9152    4340212.4038     610996.4914    4340548.9291
     610869.4911    4340667.9918     610622.1052    4340984.1695
     610573.1572    4341076.7739     610567.6572    4341228.4049
     610535.9072    4341304.6051     610275.5004     4341681.348
     610244.4945    4341687.8476     610125.5485    4341920.7144
     610102.5188    4342187.2568     610234.6856    4342555.8938
     610363.0657    4342735.6427     610469.2423     4342777.681

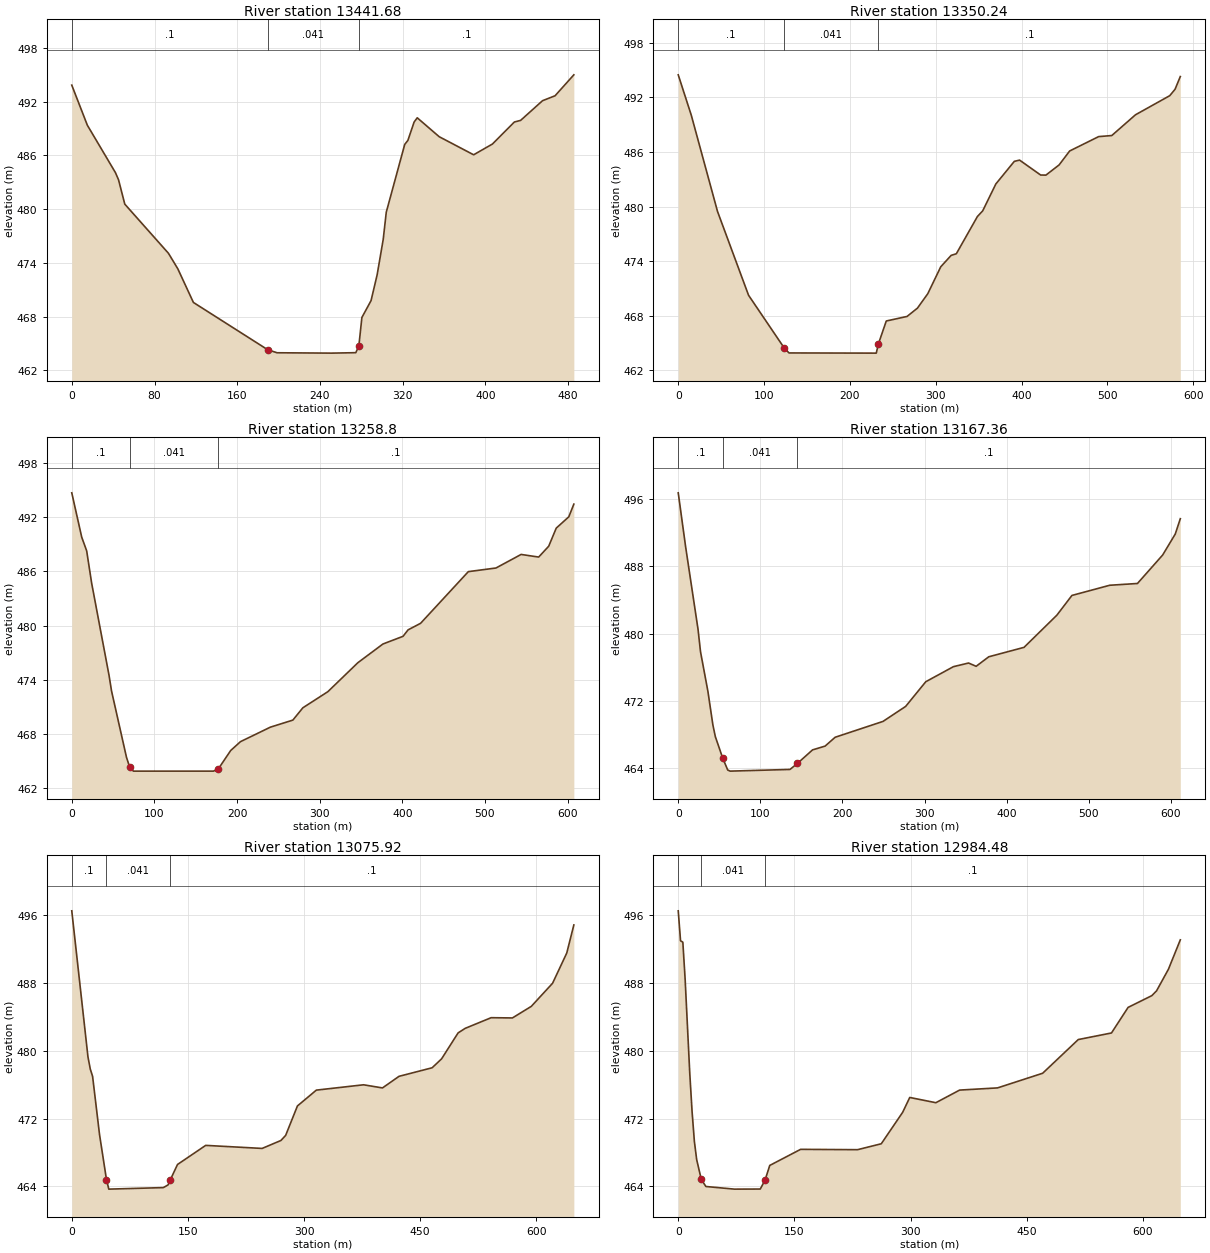
Type RM Length L Ch R = 1 ,13441.68,98.27,91.44,101.24
XS GIS Cut Line= 6
     609863.3893     4339651.379     609924.9515    4339530.4331
     610016.0499    4339492.8169     610046.2304    4339483.8546
     610092.4713    4339464.5557      610165.372    4339311.4328
#Sta/Elev= 30
       0  493.84   15.08  489.36   42.22  484.07   45.24  483.26   51.27  480.55
   93.49  475.06  102.54  473.33  117.62  469.57  189.59  464.28  198.57  463.95
   251.5  463.91  274.65  463.96  277.62  464.72  280.54  467.89  289.39  469.77
  295.28  472.65  301.18  476.62  304.12  479.65  321.97  487.22     325  487.66
  331.06  489.72  334.08  490.19  355.28  488.08   388.6  486.06  406.77  487.26
  427.96  489.72  434.02   489.9  455.22   492.1  467.33  492.65   485.5  494.99
#Mann= 3 , 0 , 0
       0      .1       0  189.59    .041       0  277.62      .1       0
Bank Sta=189.59,277.62
XS Rating Curve= 0 ,0
Exp/Cntr=0.3,0.1

Type RM Length L Ch R = 1 ,13350.24,93.96,91.44,82.13
XS GIS Cut Line= 6
     609891.1706    4339669.8998     609931.4364    4339616.2029
     610074.4668    4339570.8562     610090.0482    4339571.1203
     610173.1365    4339534.7558      610192.095    4339274.4793
#Sta/Elev= 30
       0  494.47   15.25  490.02   45.76  479.46   81.93  470.25  123.32  464.48
  129.06  463.91  230.73  463.89  233.33  464.93   242.4  467.42  266.59  467.92
  278.68  468.83  290.77  470.42  305.89  473.38  317.98  474.63  324.03  474.81
  348.59   478.9  354.73  479.52  370.08  482.48  391.57  484.96  397.71   485.1
  422.27  483.46  428.41  483.45  443.77  484.57  456.05   486.1  489.82  487.68
  505.17   487.8   532.8  490.08  572.71  492.18  578.85  492.88  584.99  494.28
#Mann= 3 , 0 , 0
       0      .1       0  123.32    .041       0  233.33      .1       0
Bank Sta=123.32,233.33
XS Rating Curve= 0 ,0
Exp/Cntr=0.3,0.1

Type RM Length L Ch R = 1 ,13258.8 ,124.83,91.44,56.34
XS GIS Cut Line= 6
     609958.5528    4339721.2313     610027.4346    4339675.2482
     610093.0716    4339662.1199     610149.9603    4339634.6761
     610237.4212    4339530.4835     610202.6784    4339274.4793
#Sta/Elev= 30
       0  494.67   12.04  489.77   18.05  488.25   24.07  484.68   45.13  474.48
   48.14  472.76    66.2  465.44   70.05  464.36   74.52  463.91  171.49  463.91
  177.44  464.17  192.31  466.19   204.2  467.17  240.33  468.77  267.53  469.55
  279.63  470.91  309.86  472.69  346.13  475.89  376.51  477.96  400.83  478.81
   406.9  479.52   422.1  480.25  479.85  485.96  513.28  486.36  543.68  487.86
  564.95  487.57  577.11  488.77  586.23  490.77  601.43  492.02  607.51  493.42
#Mann= 3 , 0 , 0
       0      .1       0   70.05    .041       0  177.44      .1       0
Bank Sta=70.05,177.44
XS Rating Curve= 0 ,0
Exp/Cntr=0.3,0.1

Type RM Length L Ch R = 1 ,13167.36,94.86,91.44,90.72
XS GIS Cut Line= 6
     610070.5666    4339812.7208     610110.2624    4339759.5745
     610135.2445    4339721.0277      610153.125    4339701.3661
     610268.9248    4339535.4662     610217.4951    4339270.2459
#Sta/Elev= 30
       0   496.7    9.05  490.26   24.12   480.5   27.14  477.84   36.18  473.12
   42.21  469.15   45.23  467.75   54.27  465.19    60.3   463.8   63.32  463.67
  136.09  463.87  145.17  464.58  163.56  466.19  178.89  466.64  191.15  467.69
  249.39  469.57  276.98  471.35  301.51  474.28  335.23  476.07  353.64   476.5
  362.85  476.11   378.2  477.24  421.18  478.36  461.09  482.17  479.51  484.52
  525.56  485.73  559.33  485.94  590.03  489.32  605.38  491.81  611.52  493.63
#Mann= 3 , 0 , 0
       0      .1       0   54.27    .041       0  145.17      .1       0
Bank Sta=54.27,145.17
XS Rating Curve= 0 ,0
Exp/Cntr=0.3,0.1

Type RM Length L Ch R = 1 ,13075.92,105.07,91.44,59.42
XS GIS Cut Line= 6
     610154.6455    4339859.2116     610180.0773     4339818.709
     610183.1583    4339806.5384     610226.3227    4339759.2414
     610304.4061    4339621.9802     610232.5763    4339262.9258
#Sta/Elev= 30
       0  496.55   20.92  479.29   23.91  477.85    26.9  476.99   35.87   470.1
   44.84  464.78   47.83  463.66  118.31  463.84  124.41  464.16  127.45  464.79
  136.56  466.57     173  468.83  245.89  468.47  270.18  469.41  276.26  470.01
  291.48  473.49  315.89  475.36  376.92  475.99  401.33  475.62  422.69  476.99
  465.41     478  477.62  479.05  498.98  482.12  508.13  482.66   541.7  483.92
  569.16  483.89  593.57  485.26  621.04  487.99  639.34  491.56   648.5  494.88
#Mann= 3 , 0 , 0
       0      .1       0   44.84    .041       0  127.45      .1       0
Bank Sta=44.84,127.45
XS Rating Curve= 0 ,0
Exp/Cntr=0.3,0.1

Type RM Length L Ch R = 1 ,12984.48,102.38,91.44,57.47
XS GIS Cut Line= 6
     610268.5926    4339889.5674     610274.2823    4339854.2868
      610275.433    4339838.5969     610285.3604    4339810.3207
      610327.199    4339599.9418     610243.1597    4339257.6341
#Sta/Elev= 30
       0  496.55    2.98  493.01    5.96  492.85    8.93  488.43   14.89  477.37
   17.87  472.84   20.85  469.31   23.82  467.15   29.78  464.82   35.74  463.98
   72.45  463.67  105.95  463.68  112.08  464.73  118.21  466.47  158.04  468.37
  231.59  468.33  262.23  469.03  289.81  472.74     299   474.5  332.72  473.88
  363.37  475.37  412.41  475.63  470.64  477.36  516.61  481.34  559.52  482.12
  580.98  485.14  611.63  486.53  617.76   487.1  633.08  489.65  648.41  493.12
#Mann= 3 , 0 , 0
       0      .1       0   29.78    .041       0  112.08      .1       0
Bank Sta=29.78,112.08
XS Rating Curve= 0 ,0
Exp/Cntr=0.3,0.1

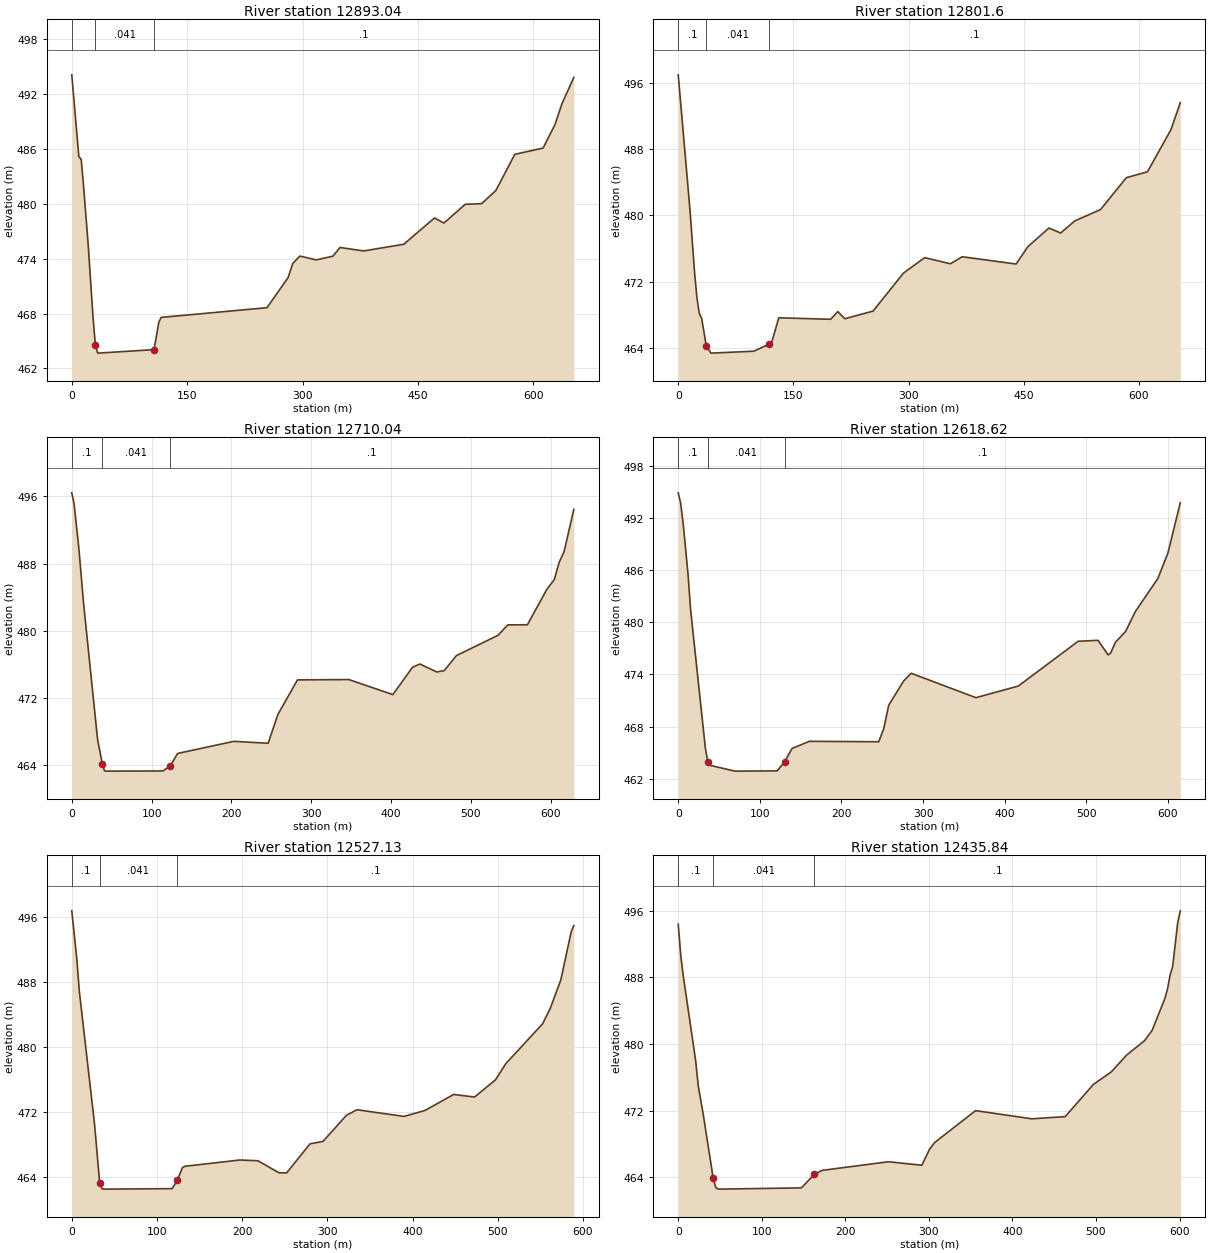
Type RM Length L Ch R = 1 ,12893.04,102.46,91.44,73.55
XS GIS Cut Line= 6
     610374.6463    4339882.8756     610373.5009    4339833.7927
     610368.4159    4339805.3131     610358.6273    4339784.6659
      610338.586    4339574.7503      610255.066    4339244.4049
#Sta/Elev= 30
       0  494.12    9.21  485.17   12.27  484.87   15.34  481.94   21.48  475.37
   27.62   467.6   30.69  464.55   33.75  463.67  106.99  464.05   113.1  467.04
  116.16  467.58  253.68  468.64  281.19  471.94   287.3  473.49  296.47  474.29
  317.89  473.87  339.37  474.28  348.58  475.23  379.28  474.85  431.47  475.58
  471.37  478.46  483.65   477.9  511.28  479.95  532.77  480.03  551.19  481.47
  575.74  485.42  612.58  486.11  627.93  488.67  637.14  490.98  652.49  493.84
#Mann= 3 , 0 , 0
       0      .1       0   30.69    .041       0  106.99      .1       0
Bank Sta=30.69,106.99
XS Rating Curve= 0 ,0
Exp/Cntr=0.3,0.1

Type RM Length L Ch R = 1 ,12801.6 ,103.94,91.56,79.05
XS GIS Cut Line= 6
     610484.7879    4339855.8313     610462.0893    4339802.5539
     610454.8946    4339780.3453     610437.2087    4339754.5034
     610384.9088    4339639.9446     610261.6806     4339243.082
#Sta/Elev= 30
       0     497   15.24  480.72   21.34  473.03   24.38  470.03   27.43  468.15
   30.48  467.58   36.58  464.22   42.67  463.36   98.34  463.59  118.71  464.45
  121.79  464.69     131  467.63  198.57  467.45  207.79  468.38     217  467.52
  253.78  468.44   293.5  473.04     321   474.9  354.61  474.16  369.89  475.01
  440.17  474.13  455.45  476.23  482.95  478.48  498.22  477.88  516.56  479.34
  550.17  480.72  583.78  484.57  611.28  485.28  641.83  490.37  654.06  493.64
#Mann= 3 , 0 , 0
       0      .1       0   36.58    .041       0  118.71      .1       0
Bank Sta=36.58,118.71
XS Rating Curve= 0 ,0
Exp/Cntr=0.3,0.1

Type RM Length L Ch R = 1 ,12710.04,94.61,91.41,71.31
XS GIS Cut Line= 4
     610577.7014    4339786.5705      610543.283    4339750.3959
     610424.1839    4339598.5588     610280.2014    4339240.4361
#Sta/Elev= 30
       0   496.4    2.94  495.08    8.81  489.89   14.69  483.36   32.31  467.11
   38.25  464.17   41.12  463.36   44.06  463.33  114.26  463.35  123.45  463.97
  132.64  465.43  203.09  466.87  245.97  466.64  258.22  470.07  282.73  474.17
  347.06  474.21   402.2  472.42  426.71  475.66   435.9  476.06  457.34  475.11
  466.53  475.28  481.85  477.06  533.93  479.47  546.18  480.71  570.69  480.72
  595.19  484.95  604.38  486.08  610.51  488.15  616.64   489.4  628.89  494.44
#Mann= 3 , 0 , 0
       0      .1       0   38.25    .041       0  123.45      .1       0
Bank Sta=38.25,123.45
XS Rating Curve= 0 ,0
Exp/Cntr=0.3,0.1

Type RM Length L Ch R = 1 ,12618.62,91.55,91.49,103.62
XS GIS Cut Line= 4
     610645.5713    4339719.8127     610611.5652    4339685.4892
     610460.7071    4339572.8633     610292.1077    4339233.8215
#Sta/Elev= 30
       0   494.9    3.02  493.69    6.04  491.38   12.08  485.46    15.1  481.51
   33.22  465.53   36.24  463.98   39.26  463.54   69.57  462.88  121.19  462.91
   130.3  463.95  139.41  465.48  160.67  466.31  245.74  466.26  251.85  467.78
  257.95  470.47  276.28  473.26  285.44  474.14  364.83  471.33  416.74  472.67
  490.03  477.82  514.46  477.93  526.67  476.26  529.73  476.44  535.83  477.72
  548.05  478.93  560.26  481.26  587.75  485.05  599.96  487.95  615.23  493.77
#Mann= 3 , 0 , 0
       0      .1       0   36.24    .041       0   130.3      .1       0
Bank Sta=36.24,130.3
XS Rating Curve= 0 ,0
Exp/Cntr=0.3,0.1

Type RM Length L Ch R = 1 ,12527.13,96.96,91.29,106.91
XS GIS Cut Line= 4
     610709.3326    4339649.6193     610670.1815    4339617.5884
     610496.6873    4339449.9008      610304.014    4339223.2382
#Sta/Elev= 30
       0  496.76    5.95  490.82    8.93  486.81   26.78  470.49   32.73  463.35
   35.71  462.57   38.68  462.54  117.78   462.6  123.89  463.62     130   465.2
  133.05  465.35  197.19  466.12  218.57  466.03     243  464.56  252.17  464.53
  279.65  468.11  294.94  468.41  322.54  471.63  334.81   472.3  390.01  471.48
  414.55  472.21  448.28  474.18  472.82  473.86  497.35  475.98  509.62  477.99
  552.56  482.85  561.76  484.78  574.02  488.25  586.29   494.2  589.36  494.95
#Mann= 3 , 0 , 0
       0      .1       0   32.73    .041       0  123.89      .1       0
Bank Sta=32.73,123.89
XS Rating Curve= 0 ,0
Exp/Cntr=0.3,0.1

Type RM Length L Ch R = 1 ,12435.84,102.27,91.44,30.53
XS GIS Cut Line= 6
      610773.427    4339568.4063     610698.0682    4339525.5913
     610683.2982    4339514.5236     610690.8388    4339476.0266
     610536.2222    4339401.2793     610324.3869    4339210.8028
#Sta/Elev= 30
       0   494.4    2.99  490.68    5.98  488.22   20.92  477.96   23.91  475.01
   29.89  471.57   41.84  463.89   44.83  462.78   47.82  462.57  147.42  462.72
  162.76  464.33  171.96  464.82  251.69  465.86  291.56  465.44  300.76  467.35
  306.89  468.17  355.92     472  423.31  471.02  463.13  471.28  496.82  475.14
  518.27  476.65  536.64  478.67  558.09   480.4  567.28  481.65  582.59   485.5
  585.66  486.62  588.72  488.28  591.78   489.3  597.91  494.65  600.97  496.01
#Mann= 3 , 0 , 0
       0      .1       0   41.84    .041       0  162.76      .1       0
Bank Sta=41.84,162.76
XS Rating Curve= 0 ,0
Exp/Cntr=0.3,0.1

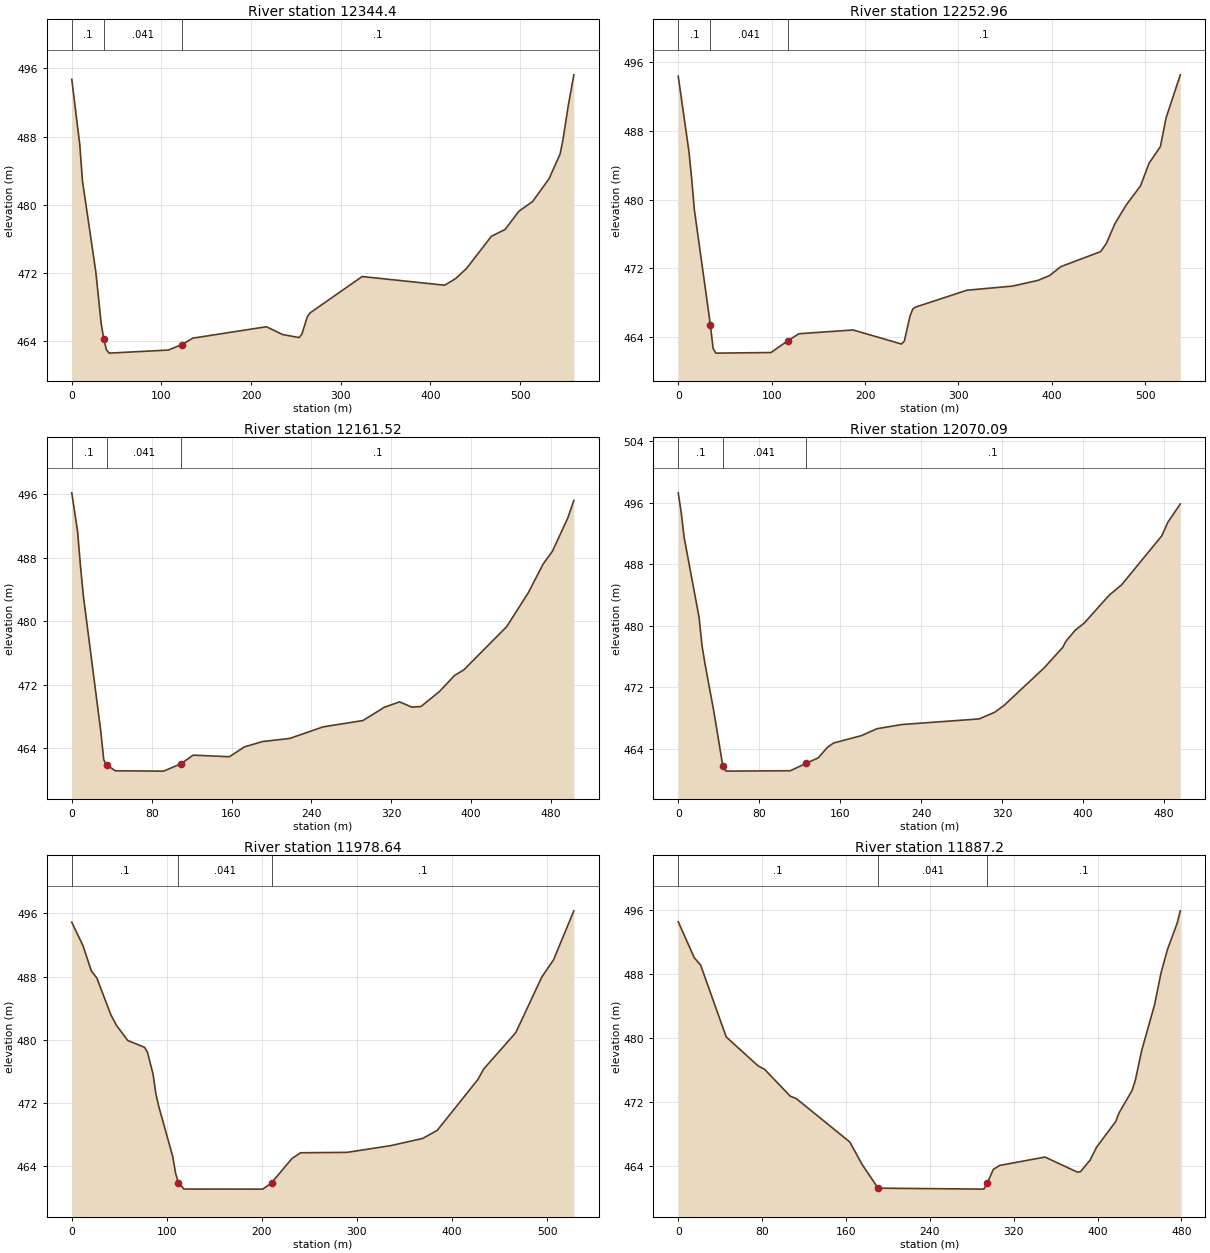
Type RM Length L Ch R = 1 ,12344.4 ,97.93,91.44,85.95
XS GIS Cut Line= 5
     610812.9036    4339463.6065     610731.3547     4339446.302
     610695.1515    4339442.1599     610551.0417    4339385.2175
     610329.6786    4339205.5111
#Sta/Elev= 30
       0  494.72    8.93  487.05   11.91  482.81    26.8  472.11   32.75  466.06
   35.73   464.2   38.71  462.93   41.68  462.55  107.66  462.91  122.84  463.56
     135  464.31  217.03  465.65  235.26  464.73  253.49  464.38  256.53  464.76
   262.6   466.8  265.64  467.27  323.81  471.55  415.79  470.53  428.05  471.31
  440.31  472.51   467.9  476.28  483.23  477.08  498.56  479.22  513.89  480.36
  532.29  483.05  544.55  485.95  547.62  487.53  553.75   491.7  559.88  495.25
#Mann= 3 , 0 , 0
       0      .1       0   35.73    .041       0  122.84      .1       0
Bank Sta=35.73,122.84
XS Rating Curve= 0 ,0
Exp/Cntr=0.3,0.1

Type RM Length L Ch R = 1 ,12252.96,91.06,91.44,86.35
XS GIS Cut Line= 5
     610829.4719    4339362.4947     610789.2999    4339363.1503
     610713.0455    4339353.5259     610569.0156    4339327.1642
     610334.9703    4339184.3444
#Sta/Elev= 30
       0  494.37   11.48  485.58   14.35  482.48   17.22  478.85   34.44  465.39
   37.31  462.66   40.18   462.1    99.3  462.17  117.04  463.52  129.24  464.36
   187.2   464.8  239.06  463.16  242.11   463.5  248.21  466.43  251.26  467.25
  254.31  467.47  309.16  469.43   357.9  469.91  385.32  470.58   397.5  471.13
  409.69  472.18  452.34  473.93  458.43  474.88  467.57  477.17  479.76  479.37
  494.99  481.58  504.13  484.22  516.31  486.17  522.41  489.52  537.64  494.53
#Mann= 3 , 0 , 0
       0      .1       0   34.44    .041       0  117.04      .1       0
Bank Sta=34.44,117.04
XS Rating Curve= 0 ,0
Exp/Cntr=0.3,0.1

Type RM Length L Ch R = 1 ,12161.52,91.08,91.43,94.43
XS GIS Cut Line= 6
      610832.134    4339280.3467     610786.5576    4339270.6387
     610758.8174    4339267.1375     610720.9044    4339266.4498
     610597.9208    4339250.2408     610354.1085    4339142.8929
#Sta/Elev= 30
       0  496.14    5.82  491.29    8.74  486.89   11.65  483.15   29.12  466.09
   32.04  462.56   34.95  461.92   43.69  461.18   92.06  461.14  109.56  462.08
  121.55  463.15  157.86  462.95  172.99  464.19  191.14  464.86  218.37  465.25
  251.84  466.71  291.64   467.5  313.08  469.17  328.39  469.85  340.63  469.19
  349.82  469.27  368.19  471.14   383.5  473.18  392.69  473.87  435.56   479.3
  456.99  483.51   472.3  487.21  481.49   488.8   496.8  492.96  502.92  495.18
#Mann= 3 , 0 , 0
       0      .1       0   34.95    .041       0  109.56      .1       0
Bank Sta=34.95,109.56
XS Rating Curve= 0 ,0
Exp/Cntr=0.3,0.1

Type RM Length L Ch R = 1 ,12070.09,86.51,91.45,97.7
XS GIS Cut Line= 3
     610855.1339    4339192.7842     610797.8431    4339179.7653
      610363.369    4339130.9866
#Sta/Elev= 30
       0   497.3    2.94  494.75    5.88  491.47   20.56  481.13    23.5  477.42
   26.44  475.06   35.25  468.81   44.06  461.76      47   461.1  110.73  461.15
  126.01   462.1  138.24  462.82  147.42   464.2  153.53  464.76  181.05  465.72
  196.33  466.62  220.79  467.16  297.23  467.89  312.51  468.75  321.68  469.63
  361.43  474.53  379.77  477.19  382.83  477.97     392  479.41  401.18  480.38
  425.64  483.98  437.86  485.32  477.61   491.7  483.72  493.49  495.95  495.86
#Mann= 3 , 0 , 0
       0      .1       0   44.06    .041       0  126.01      .1       0
Bank Sta=44.06,126.01
XS Rating Curve= 0 ,0
Exp/Cntr=0.3,0.1

Type RM Length L Ch R = 1 ,11978.64,91.05,91.44,105.06
XS GIS Cut Line= 6
     610923.9296    4339166.3086     610902.5722    4339131.1389
     610838.3961    4339100.7376     610792.1279    4339082.4709
     610762.9897    4339076.2636     610426.8691    4339063.5177
#Sta/Elev= 30
       0  494.89   11.76  491.93   20.57  488.74   26.45  487.81   41.15  483.18
   47.06  481.84    58.9  479.93   76.65  479.06   79.61  478.44   85.53  475.67
   88.49  473.17   91.45  471.62  106.24  465.24   109.2  463.15  112.16  461.96
  117.98  461.14  200.95  461.13  210.12  461.92  231.52  464.99   240.7  465.73
  289.62  465.78  335.49  466.63  369.13  467.54  384.42  468.56  427.23     475
  433.34  476.33  466.98  480.91   494.5  487.97  506.73  490.12  528.14  496.33
#Mann= 3 , 0 , 0
       0      .1       0  112.16    .041       0  210.12      .1       0
Bank Sta=112.16,210.12
XS Rating Curve= 0 ,0
Exp/Cntr=0.3,0.1

Type RM Length L Ch R = 1 ,11887.2 ,85.99,91.44,91.29
XS GIS Cut Line= 6
     610975.5234     4339158.371     610942.4761    4339053.5927
     610876.8922    4339017.8168     610793.8515    4338986.8413
     610770.6977    4338979.2528     610601.4944    4338914.0279
#Sta/Elev= 30
       0  494.48   15.26     490   21.36  489.07   45.78  480.11    76.3  476.49
    82.4  476.07  106.81  472.73  112.85   472.4  163.66  467.01  175.61  464.16
  190.69  461.25  291.48  461.13  294.52  461.84  300.64   463.6  306.79  464.09
  349.82  465.13  380.55  463.26  383.63   463.3  392.85  464.75     399  466.35
  417.44  469.59  420.51  470.65  432.81  473.41  435.88  474.63  442.03   478.4
  454.32  484.11  460.47  488.07  466.61     491  475.83  494.27  478.91  495.84
#Mann= 3 , 0 , 0
       0      .1       0  190.69    .041       0  294.52      .1       0
Bank Sta=190.69,294.52
XS Rating Curve= 0 ,0
Exp/Cntr=0.3,0.1

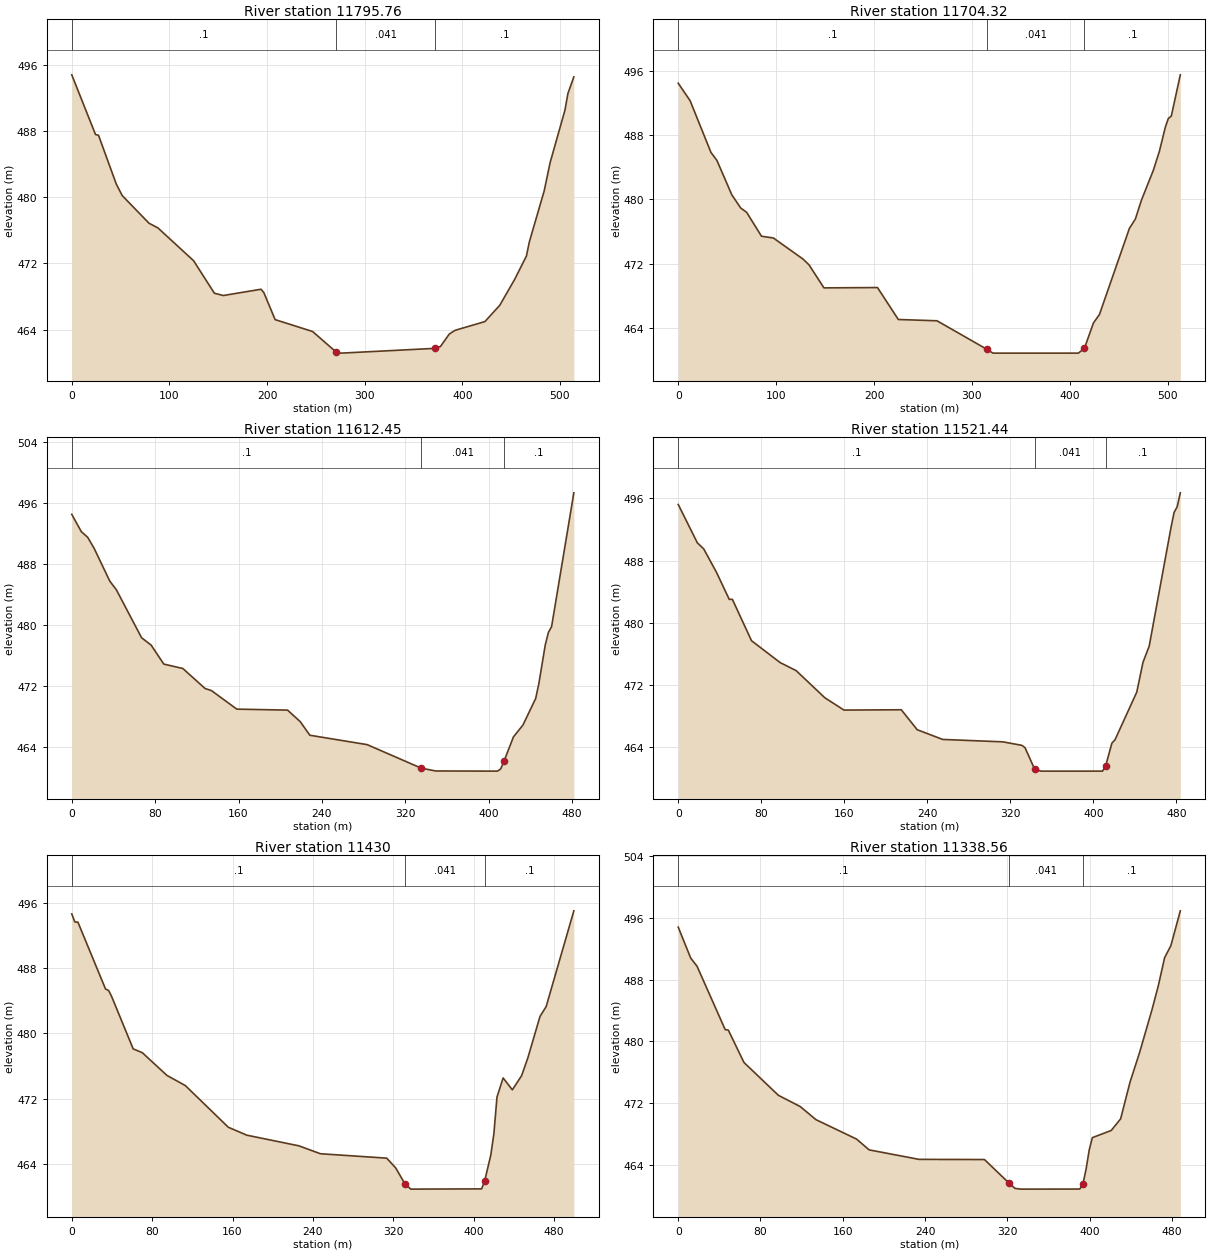
Type RM Length L Ch R = 1 ,11795.76,77.14,91.44,121.63
XS GIS Cut Line= 6
      610999.336    4339163.6627     610977.1461    4338988.5447
     610951.6399    4338957.1115     610888.1379    4338934.6451
     610885.3209    4338923.3665     610682.1925     4338845.236
#Sta/Elev= 30
       0  494.86   24.35  487.62   27.39  487.54   45.65  481.61   51.74  480.22
   79.13  476.88   88.26  476.31  124.78  472.34  146.08   468.4  155.21  468.12
  193.87  468.88  196.76  468.47  208.32   465.2   246.7  463.76  270.46  461.31
  276.21  461.14  372.34  461.72  377.66  461.94  386.77  463.46  392.84  463.91
  423.21  464.96  438.39  466.93  453.57  470.05  465.72   472.9  468.76  474.63
  483.94   480.8  490.02  484.23   505.2  490.58  508.24   492.6  514.31  494.61
#Mann= 3 , 0 , 0
       0      .1       0  270.46    .041       0  372.34      .1       0
Bank Sta=270.46,372.34
XS Rating Curve= 0 ,0
Exp/Cntr=0.3,0.1

Type RM Length L Ch R = 1 ,11704.32,42.32,91.87,123.31
XS GIS Cut Line= 6
     611019.1798    4339170.2773     611000.6022    4338976.7817
     610968.6781    4338888.1591     610928.5207    4338848.1065
     610892.4482    4338821.0188     610810.5157    4338730.1421
#Sta/Elev= 30
       0  494.44   12.15  492.26   33.41  485.84   39.48  484.85   54.67  480.58
   63.78  478.93   69.86  478.39   85.04  475.42   97.19   475.2  127.57  472.57
  133.64  471.85  148.83     469   203.5  469.04  224.77  465.07  264.27  464.91
  315.45  461.35  321.42  460.89  408.76  460.89  414.88  461.51  424.06  464.64
  430.18  465.69  460.77  476.39  466.88  477.56     473  479.88  485.24  483.62
  491.36  485.95  497.47  488.97  500.53  490.05  503.59  490.36  512.77  495.48
#Mann= 3 , 0 , 0
       0      .1       0  315.45    .041       0  414.88      .1       0
Bank Sta=315.45,414.88
XS Rating Curve= 0 ,0
Exp/Cntr=0.3,0.1

Type RM Length L Ch R = 1 ,11612.45,77.4,91.01,96.04
XS GIS Cut Line= 4
     611029.7631    4339174.2461     611012.1063    4338958.7263
     610991.8751    4338878.7563     610987.7869    4338695.7462
#Sta/Elev= 30
       0   494.5    9.14  492.24   15.23   491.5   21.32  490.09   36.55  485.74
   42.64  484.66      67  478.34   76.14  477.38   88.32  474.89   106.6  474.31
  127.92  471.69  134.01  471.42  158.37  468.99   207.1  468.86   219.3  467.34
  228.46  465.57  283.46  464.34  335.34  461.26  349.25  460.89  408.56  460.87
  411.62  461.16  414.67  462.14  423.82  465.35  432.97  466.91  445.18  470.39
  448.23  472.34  454.33  477.37  457.38  479.04  460.43  479.79  481.79  497.32
#Mann= 3 , 0 , 0
       0      .1       0  335.34    .041       0  414.67      .1       0
Bank Sta=335.34,414.67
XS Rating Curve= 0 ,0
Exp/Cntr=0.3,0.1

Type RM Length L Ch R = 1 ,11521.44,79.69,91.44,108.05
XS GIS Cut Line= 5
     611045.6381    4339182.1836     611052.3032     4338921.244
     611077.1665    4338823.7415      611083.216    4338785.9321
     611090.9746    4338702.3608
#Sta/Elev= 30
       0  495.22   18.43  490.28   24.57   489.5   36.85  486.49   49.13  483.01
    52.2     483   70.63  477.68   98.27  474.86  113.62  473.83  141.26  470.34
  159.69  468.75  214.96  468.79  230.32  466.22  254.88  464.97  312.86  464.66
  331.16  464.21   334.2  463.91  343.35  461.19  349.45  460.89  408.93  460.89
  411.93  461.56  417.92  464.49  420.92  464.92   441.9  471.06   447.9   474.9
  453.89  476.98  474.88  492.24  477.87  494.19  480.87  494.94  483.87  496.72
#Mann= 3 , 0 , 0
       0      .1       0  343.35    .041       0  411.93      .1       0
Bank Sta=343.35,411.93
XS Rating Curve= 0 ,0
Exp/Cntr=0.3,0.1

Type RM Length L Ch R = 1 ,11430   ,68.79,91.44,100.59
XS GIS Cut Line= 6
     611080.0341     4339191.444     611113.7213    4338946.3315
      611149.362    4338873.6934     611159.4181    4338845.3759
     611175.6276    4338811.9439      611232.527    4338724.8504
#Sta/Elev= 30
       0  494.65    3.05  493.67    6.11  493.64    33.6  485.44   36.65  485.26
   39.71  484.51   61.09   478.1   70.25  477.62   94.69  474.84  113.02  473.59
  155.78  468.48  174.11  467.51  226.04   466.2  247.42  465.23  313.34  464.69
  322.33  463.49  331.33  461.57  337.34  460.89  407.77  460.92  410.83  461.88
  416.95  465.08  420.01  467.69  423.07  472.17  429.19  474.53  438.37  473.07
  447.55   474.8  453.67  476.94  465.91  482.08  472.03  483.29  499.56  495.03
#Mann= 3 , 0 , 0
       0      .1       0  331.33    .041       0  410.83      .1       0
Bank Sta=331.33,410.83
XS Rating Curve= 0 ,0
Exp/Cntr=0.3,0.1

Type RM Length L Ch R = 1 ,11338.56,87,91.44,92.74
XS GIS Cut Line= 6
     611101.2008    4339199.3815     611140.4401    4338999.2659
     611209.9825    4338911.4207     611235.1251    4338887.2452
     611254.9378    4338868.1945     611329.1001    4338787.0276
#Sta/Elev= 30
       0  494.79   12.17  490.77   18.26  489.74   45.66  481.53    48.7  481.47
   63.92  477.28    97.4  473.03   118.7  471.57  133.92  469.88  173.49  467.36
  185.66  465.97  234.21  464.74   297.8  464.72  321.78  461.66  327.59  460.98
  333.41  460.89  390.55   460.9   393.6  461.57  396.66  463.48  399.71  465.97
  402.76  467.55  421.09  468.48  430.25  469.99  439.41  474.75  448.58  478.52
  460.79  484.13   466.9  487.21  473.01  490.84  479.12   492.4  488.28   496.9
#Mann= 3 , 0 , 0
       0      .1       0  321.78    .041       0   393.6      .1       0
Bank Sta=321.78,393.6
XS Rating Curve= 0 ,0
Exp/Cntr=0.3,0.1