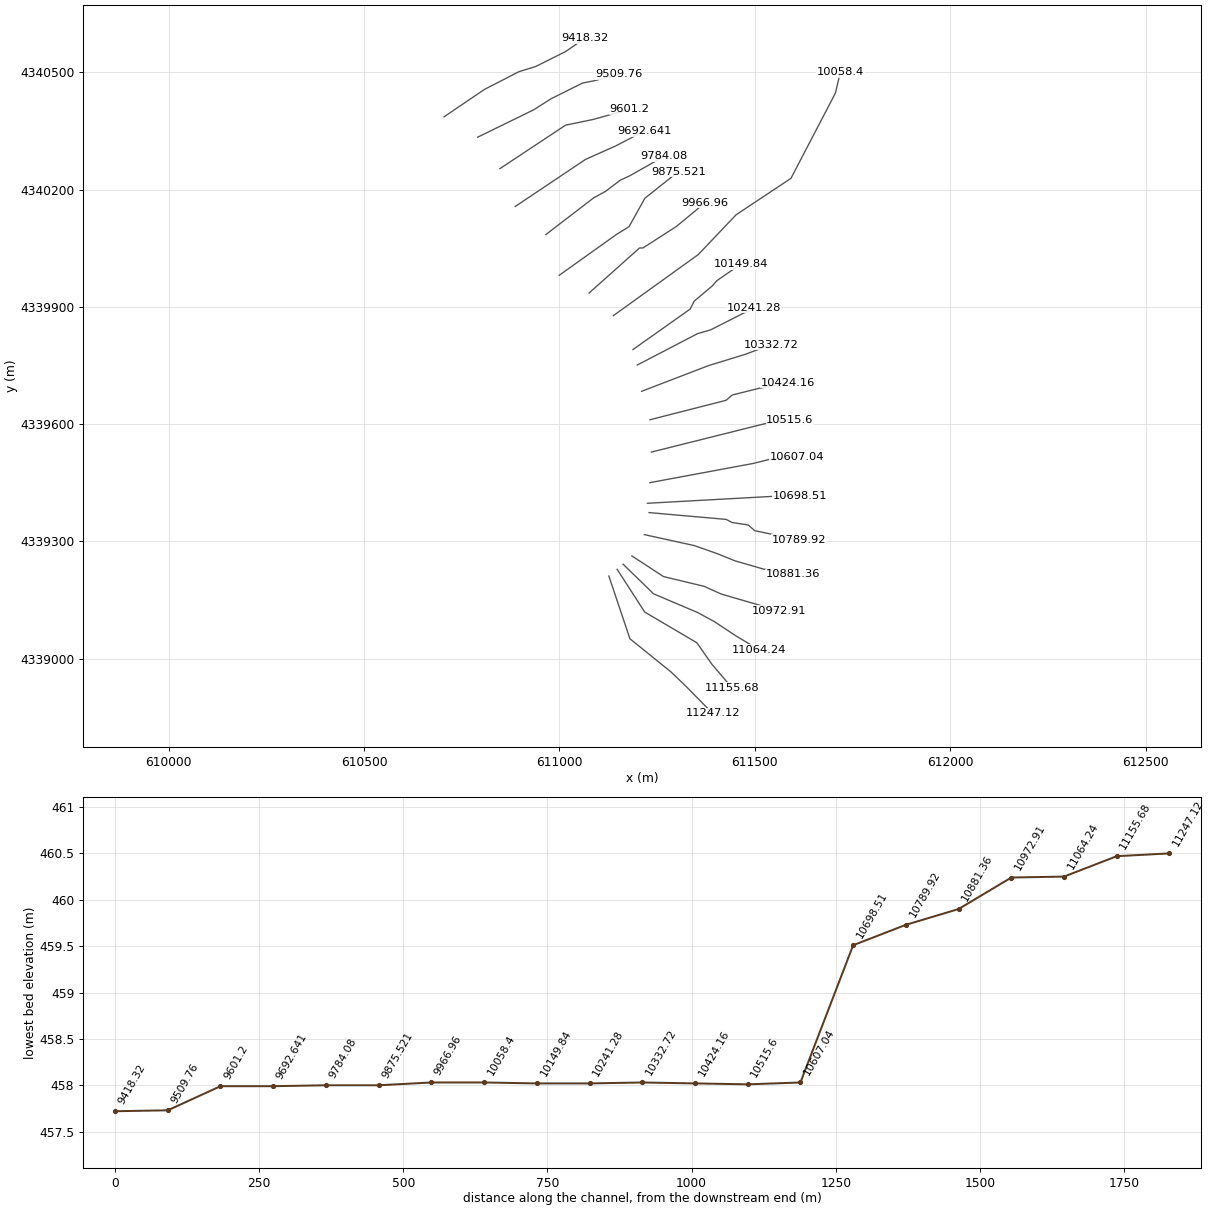
HEC-RAS study CheatRiver.prj: CheatRiver

--- CheatRiver.g01 (geometry) --- (continued)

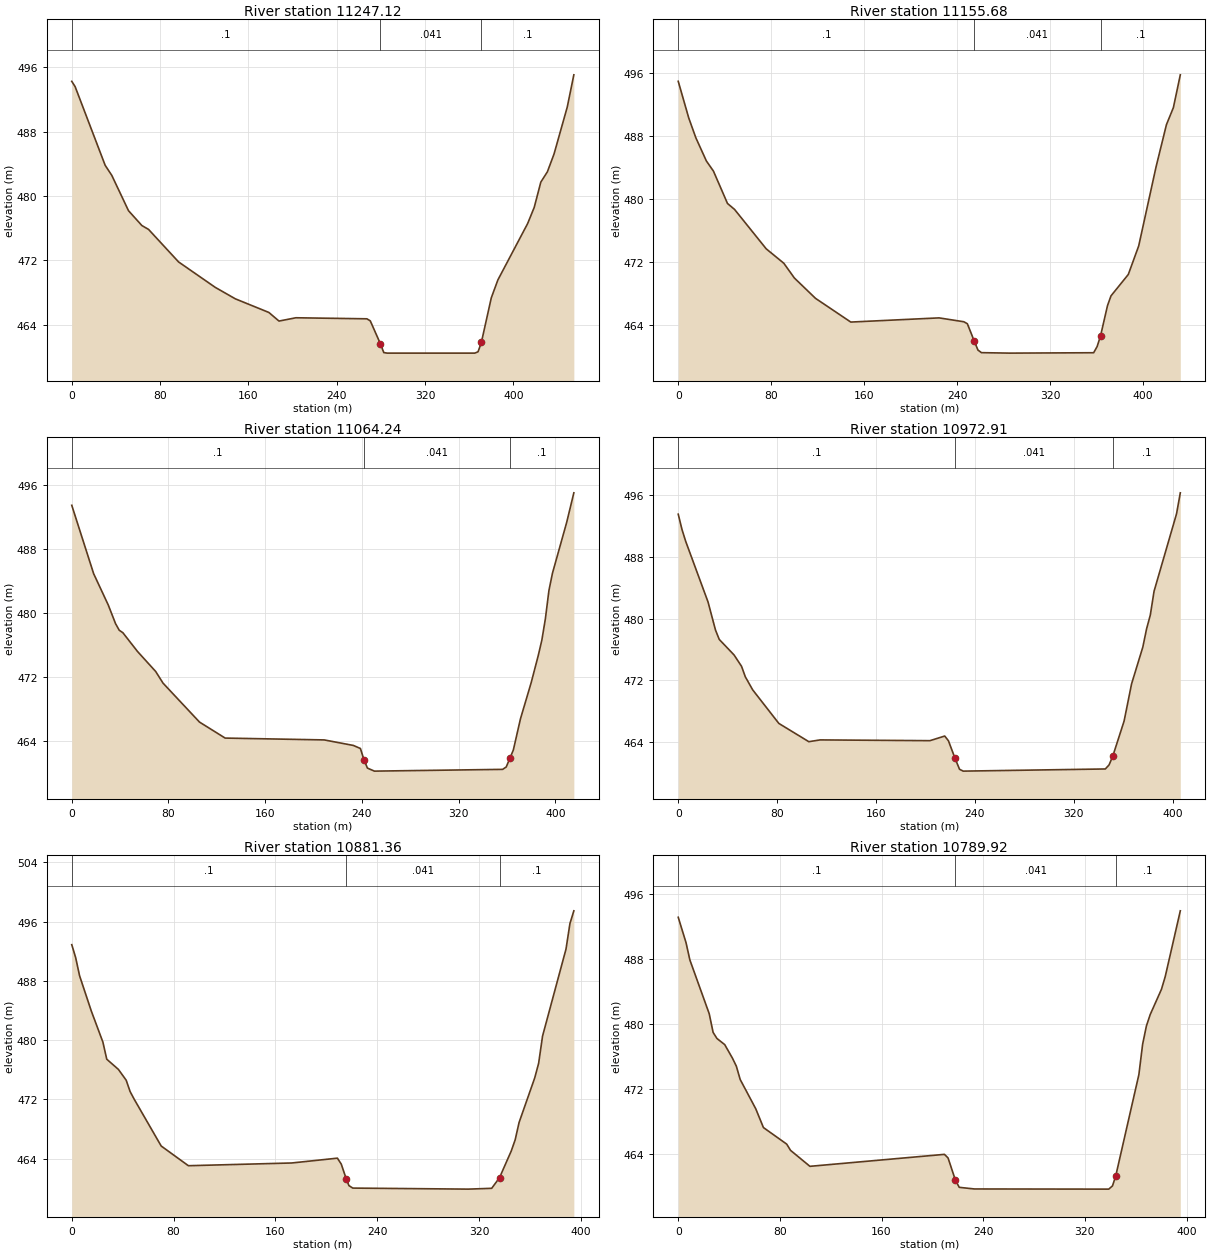
Type RM Length L Ch R = 1 ,11247.12,93.1,91.44,85.56
XS GIS Cut Line= 5
     611126.3362    4339211.2878     611180.2144     4339050.767
     611285.0209    4338966.1217     611326.8195    4338925.9308
     611391.8064    4338859.7882
#Sta/Elev= 30
       0  494.24    3.02  493.59   30.24  483.82   36.28  482.56    51.4  478.18
    63.5  476.34   69.54  475.86   96.76  471.82  130.01  468.66  148.16  467.24
  178.51  465.55  187.69  464.48     203  464.89   267.3  464.76  270.36  464.51
  279.55  461.66  282.61  460.57  285.67   460.5  365.02   460.5  368.01  460.67
     371  461.83  379.97  467.36  385.96  469.59  412.88  476.58  418.86  478.59
  424.84  481.73  430.82  483.02  436.81  485.22  448.77  491.04  454.75  495.05
#Mann= 3 , 0 , 0
       0      .1       0  279.55    .041       0     371      .1       0
Bank Sta=279.55,371
XS Rating Curve= 0 ,0
Exp/Cntr=0.3,0.1

Type RM Length L Ch R = 1 ,11155.68,66.64,91.44,103.34
XS GIS Cut Line= 5
     611147.5029    4339228.4858      611218.095    4339119.0934
     611351.6322    4339040.4244      611389.549    4338986.1344
     611441.8128    4338924.8758
#Sta/Elev= 30
       0  494.95    9.08  490.28   15.14  487.79   24.22  484.84   30.28  483.56
   42.39  479.45   48.44   478.7   75.69   473.7   90.83  471.87   99.91     470
  118.08  467.42  148.43  464.41   224.4  464.94  245.67  464.45  248.71   464.2
  254.79  461.95  257.83  460.86  260.87  460.53  285.18  460.47  357.36  460.52
  360.35   461.3  363.33  462.68  369.29   466.5  372.28  467.73  387.19  470.45
  396.13  474.07  411.05  484.09  419.99  489.45  425.96  491.61  431.92  495.77
#Mann= 3 , 0 , 0
       0      .1       0  254.79    .041       0  363.33      .1       0
Bank Sta=254.79,363.33
XS Rating Curve= 0 ,0
Exp/Cntr=0.3,0.1

Type RM Length L Ch R = 1 ,11064.24,66.9,91.33,98.89
XS GIS Cut Line= 6
     611162.8268    4339241.4945     611240.7246    4339165.7238
     611352.4632    4339118.3563     611395.8431    4339094.9189
     611452.7935    4339057.3102     611510.8692    4339022.5072
#Sta/Elev= 30
       0  493.47   18.11  484.92   30.19  481.01   36.22  478.68   39.24  477.86
   42.26  477.55   54.34  475.21   69.43   472.7   75.47  471.25  105.65  466.38
  126.88  464.38   208.8  464.15  232.93  463.46  238.74  463.08  241.64   461.7
  244.54  460.63  250.34  460.25  356.42  460.47  359.36  460.77  362.31  461.83
  365.25  462.89  371.14  466.79  379.97  471.29  385.86   474.7   388.8   476.6
  391.74  479.28  394.69  482.83  397.63     485  409.41  491.36  415.29  495.03
#Mann= 3 , 0 , 0
       0      .1       0  241.64    .041       0  362.31      .1       0
Bank Sta=241.64,362.31
XS Rating Curve= 0 ,0
Exp/Cntr=0.3,0.1

Type RM Length L Ch R = 1 ,10972.91,91.45,91.55,94.24
XS GIS Cut Line= 5
     611185.3164    4339262.6612     611266.0561    4339209.9178
       611370.23    4339184.8661      611413.927     4339165.163
     611562.3969    4339121.9908
#Sta/Elev= 30
       0  493.57    3.01   491.6    6.03  490.05   24.11  482.18   30.14  478.54
   33.15  477.33   45.21   475.3   51.23  473.83   54.25  472.48   60.28  470.77
   81.37  466.43  105.62  464.06  114.81  464.29  203.58  464.19  215.57  464.79
  218.56  464.18  223.91   461.9  227.55  460.48  230.55  460.24   345.5  460.52
  348.53  461.05  351.53  462.19  360.66  466.73  366.72  471.56  375.82  476.33
  378.85  478.69  381.88  480.49  384.91  483.58  403.11  493.63  406.14  496.34
#Mann= 3 , 0 , 0
       0      .1       0  223.91    .041       0  351.53      .1       0
Bank Sta=223.91,351.53
XS Rating Curve= 0 ,0
Exp/Cntr=0.3,0.1

Type RM Length L Ch R = 1 ,10881.36,91.65,91.44,93.67
XS GIS Cut Line= 6
     611216.9732    4339317.2996     611345.2268    4339289.1121
     611403.9644    4339268.4746     611448.6686    4339250.3032
     611521.4249    4339229.2652     611597.0574     4339215.918
#Sta/Elev= 30
       0   492.9    3.05  491.16    6.11  488.72   15.27  483.98   24.43  479.76
   27.48  477.44   36.65  476.06   42.75   474.6   45.81  473.08   48.86  472.09
   70.24  465.72   91.61  463.06  172.82  463.43  208.65  464.08  211.67  463.28
  215.71  461.23   217.7  460.38  220.72  460.04  311.51   459.9  329.85  460.01
     336  461.45  345.21  465.05  348.29  466.56  351.36   468.9  363.65  474.92
  366.72  476.89  369.79  480.56  388.22  492.31  391.29  495.74  394.37  497.47
#Mann= 3 , 0 , 0
       0      .1       0  215.71    .041       0     336      .1       0
Bank Sta=215.71,336
XS Rating Curve= 0 ,0
Exp/Cntr=0.3,0.1

Type RM Length L Ch R = 1 ,10789.92,57.32,91.41,104.26
XS GIS Cut Line= 6
     611229.2129    4339373.6421     611426.5863    4339356.1841
     611441.6709    4339348.2679     611482.9427    4339341.8966
      611499.575    4339327.3958     611613.1033    4339303.3685
#Sta/Elev= 30
       0  493.12     6.1  490.02    9.15  487.88   24.39  481.27   27.44  478.98
   30.48  478.23   36.58  477.48   42.68  475.81   45.73  474.83   48.77  473.19
   60.97  469.61   67.06  467.29   85.35  465.26    88.4  464.49  103.64  462.53
   209.5     464  212.34  463.56  218.16  460.82  221.15  459.95  233.08  459.75
   338.8  459.73  341.76  460.13  344.32  461.36  362.51  473.79  365.48  477.54
  368.44  479.77   371.4  481.16   380.3  484.28  383.26  485.84  395.12  493.91
#Mann= 3 , 0 , 0
       0      .1       0  218.16    .041       0  344.32      .1       0
Bank Sta=218.16,344.32
XS Rating Curve= 0 ,0
Exp/Cntr=0.3,0.1

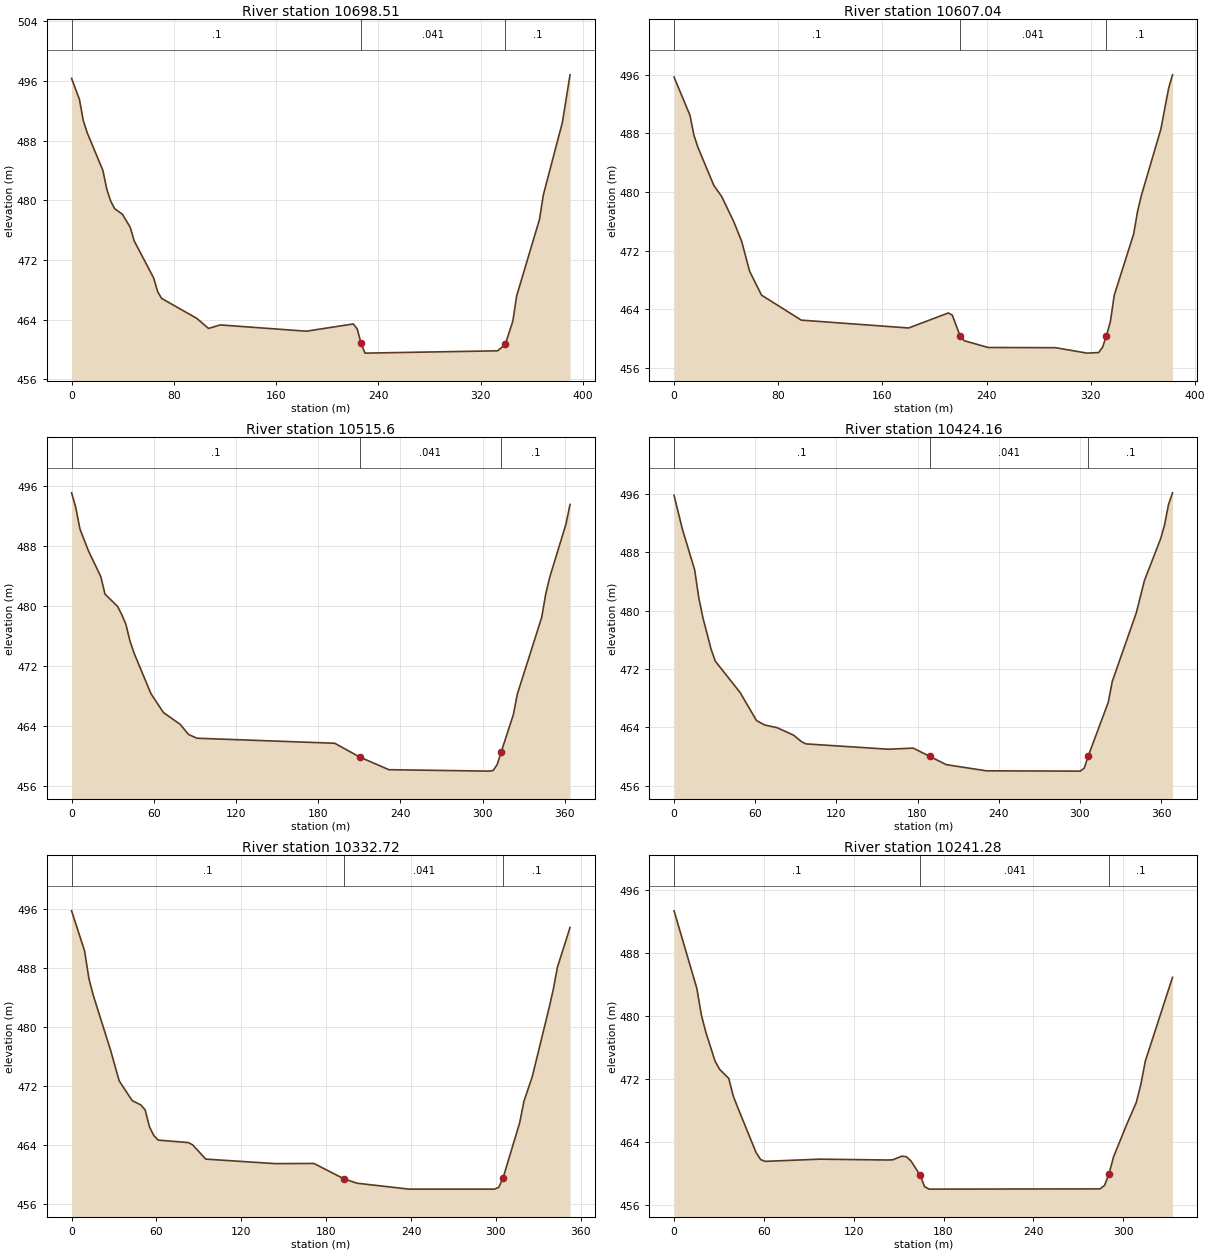
Type RM Length L Ch R = 1 ,10698.51,78.12,91.47,97.45
XS GIS Cut Line= 3
       611225.01    4339397.4896     611545.8502    4339415.1642
     611614.4262    4339415.8167
#Sta/Elev= 30
       0  496.34    6.12  493.53    9.18  490.66   12.24  489.05   24.48  484.01
   27.54  481.49    30.6  479.89   33.66  478.88   39.78  478.12    45.9  476.37
   48.96  474.56   64.27  469.56   67.33  467.75   70.39  466.85   97.93  464.17
  107.11  462.82  116.29  463.29  183.62  462.45  220.34  463.42   223.4  462.77
  226.46  460.82  229.52  459.51  333.25  459.82  339.22  460.67  345.18  463.81
  348.16  467.19  366.05  477.46  369.03  480.73  383.94  490.45  389.91  496.82
#Mann= 3 , 0 , 0
       0      .1       0  226.46    .041       0  339.22      .1       0
Bank Sta=226.46,339.22
XS Rating Curve= 0 ,0
Exp/Cntr=0.3,0.1

Type RM Length L Ch R = 1 ,10607.04,87.34,91.44,94.68
XS GIS Cut Line= 4
     611231.3264    4339450.2599     611495.3707    4339499.3209
     611542.4355    4339511.0871     611607.8116    4339516.3585
#Sta/Elev= 30
       0  495.68   12.21  490.47   15.26  487.75   18.31  486.11   30.52  480.91
   36.62  479.37   45.78  475.98   51.88  473.29   57.99   469.2   67.14  465.94
   97.66  462.53  180.06  461.46  210.58  463.51  213.63  463.21  219.73   460.3
  222.79  459.72   241.1   458.8  292.82  458.77  317.08  458.03  326.02  458.11
     329  458.85  331.98  460.43  334.96  462.33  337.95  465.94  352.85   474.3
  355.83  477.37  358.81  479.57  373.72  488.58  379.68  494.15  382.66  495.99
#Mann= 3 , 0 , 0
       0      .1       0  219.73    .041       0  331.98      .1       0
Bank Sta=219.73,331.98
XS Rating Curve= 0 ,0
Exp/Cntr=0.3,0.1

Type RM Length L Ch R = 1 ,10515.6 ,81.95,91.44,92.37
XS GIS Cut Line= 3
     611235.2876    4339528.5543     611525.1294    4339601.0148
     611589.2907    4339611.6087
#Sta/Elev= 30
       0  495.05    3.05   493.1     6.1  490.23   12.19  487.38   21.34  483.89
   24.39  481.57   33.53  479.94   36.58  478.86   39.63  477.56   42.68  475.28
   45.73  473.66   57.92  468.32   67.07   465.8   79.26  464.24   85.36  462.89
   91.46  462.39  192.06  461.72  210.35  459.88  231.59   458.2  304.67  458.01
  307.63  458.09  310.59  458.87  313.54  460.55  322.41  465.52  325.37  468.29
   343.1  478.47  346.06  481.59  349.01  483.84  360.84  490.91  363.79   493.5
#Mann= 3 , 0 , 0
       0      .1       0  210.35    .041       0  313.54      .1       0
Bank Sta=210.35,313.54
XS Rating Curve= 0 ,0
Exp/Cntr=0.3,0.1

Type RM Length L Ch R = 1 ,10424.16,95.34,91.44,98.33
XS GIS Cut Line= 5
     611231.4873    4339611.2225     611426.3824    4339660.9958
     611442.1807    4339674.5318     611512.3732      4339692.08
      611585.322     4339705.536
#Sta/Elev= 30
       0  495.78     6.1  491.19   15.24  485.57   18.29  481.76   21.33  479.02
   27.43  474.68   30.48  473.08   48.76   468.8   60.95  464.95   67.05  464.33
   76.19  463.97   88.38  462.94   94.48  462.02   97.53  461.75  158.48  461.02
  176.77  461.17  188.96  460.05  201.15  458.91     231  458.06  300.24  458.02
  303.21  458.43  306.18  460.08  321.01  467.45  323.98  470.32  341.78  479.73
  347.72  484.12  359.59  489.78  362.55  491.68  365.52  494.51  368.49  496.13
#Mann= 3 , 0 , 0
       0      .1       0  188.96    .041       0  306.18      .1       0
Bank Sta=188.96,306.18
XS Rating Curve= 0 ,0
Exp/Cntr=0.3,0.1

Type RM Length L Ch R = 1 ,10332.72,83.57,91.44,100.26
XS GIS Cut Line= 4
      611210.268    4339684.0926     611381.6497    4339749.8724
      611475.008    4339778.5022     611541.6656     4339803.432
#Sta/Elev= 30
       0  495.77    9.18  490.34   12.24   486.6    15.3  484.33   27.54  476.89
   33.65  472.71   42.83  470.04   48.95  469.45   52.01  468.78   55.07  466.48
   58.13   465.3   61.19  464.68   82.61  464.34   85.67  464.02   94.85   462.1
   143.8  461.49  171.33  461.51  192.73  459.41  201.88  458.83   238.5  458.03
  299.01  458.03  301.98  458.27  304.94  459.48   316.8  467.04  319.77  469.92
   325.7  473.29  337.56  482.59  340.53  485.09  343.49  488.13  352.39  493.51
#Mann= 3 , 0 , 0
       0      .1       0  192.73    .041       0  304.94      .1       0
Bank Sta=192.73,304.94
XS Rating Curve= 0 ,0
Exp/Cntr=0.3,0.1

Type RM Length L Ch R = 1 ,10241.28,58.96,91.44,106.72
XS GIS Cut Line= 4
     611199.2533    4339751.3712     611353.1368     4339831.476
     611387.0821    4339841.3756     611497.7127    4339897.6284
#Sta/Elev= 30
       0   493.4   15.22  483.54   18.26  480.13   21.31  477.92   27.39  474.29
   30.44  473.25   36.52   472.1   39.57  469.84   42.61  468.36   54.78  462.68
   57.83  461.78   60.87  461.55   97.39  461.83  143.05  461.72  146.09  461.75
  152.18  462.21  155.22  462.14  158.27   461.6  164.35  459.79   167.4  458.32
  170.44  458.02  284.52  458.05  287.55  458.49  290.58     460   293.6  462.14
  302.68  466.39  308.74  469.03  311.77   471.3  314.79   474.3  332.95  484.94
#Mann= 3 , 0 , 0
       0      .1       0  164.35    .041       0  290.58      .1       0
Bank Sta=164.35,290.58
XS Rating Curve= 0 ,0
Exp/Cntr=0.3,0.1

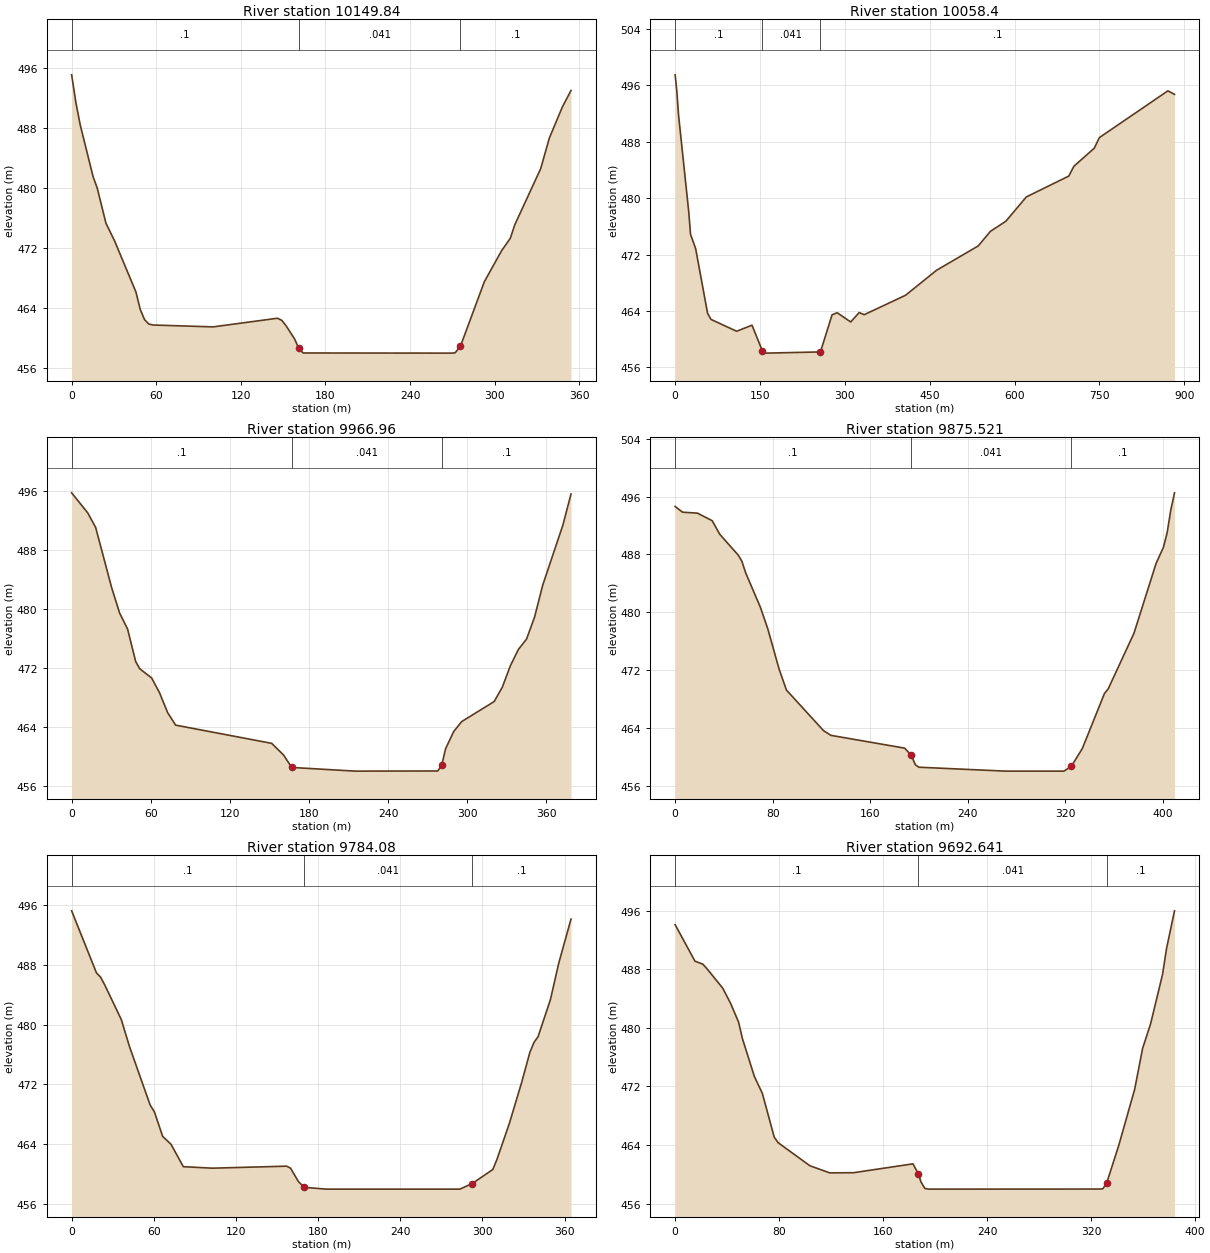
Type RM Length L Ch R = 1 ,10149.84,98.68,91.44,90.6
XS GIS Cut Line= 6
     611187.9137    4339790.8167     611334.3513    4339894.3852
     611344.6413      4339914.66     611391.4712    4339954.1728
     611402.6139    4339967.0135     611463.2165    4340009.0137
#Sta/Elev= 30
       0  495.03    3.04  491.32    6.08  488.38    15.2   481.5   18.24  479.91
   24.32   475.3    30.4  472.97    45.6  466.15   48.64  463.84   51.68  462.48
   54.72  461.89   57.76  461.76  100.32  461.51  145.92  462.66  148.96  462.39
     152  461.68  158.08  459.91  161.12  458.64  164.16  458.04  269.04  458.02
  271.87  458.05  275.65  458.91  292.66  467.52  304.95  471.66  311.09   473.3
  314.17  475.06   332.6  482.55  338.74  486.62  347.96  490.75  354.11  492.95
#Mann= 3 , 0 , 0
       0      .1       0  161.12    .041       0  275.65      .1       0
Bank Sta=161.12,275.65
XS Rating Curve= 0 ,0
Exp/Cntr=0.3,0.1

Type RM Length L Ch R = 1 ,10058.4 ,100.62,91.44,95.17
XS GIS Cut Line= 6
     611137.8522    4339877.6547     611355.2336    4340034.0458
     611452.0478    4340135.8894     611592.3125    4340228.9876
     611706.1045    4340447.1646     611718.8045    4340501.1397
#Sta/Elev= 30
       0  497.48    3.02  495.12    6.04  491.78   24.15  477.98   27.17  474.88
   36.23  472.86   57.36  463.67   63.39  462.81  108.68  461.13  135.85  461.99
  154.08  458.38   160.2  458.03  256.88   458.2  277.41  463.46  286.39  463.76
  310.35  462.45  325.32  463.78   334.3  463.48  407.28  466.23  462.39  469.79
  535.85  473.23  557.28  475.29  584.71  476.73  620.76  480.17  695.88  483.13
  704.89  484.52  740.91  487.08  749.92  488.58  871.09  495.21  882.77  494.71
#Mann= 3 , 0 , 0
       0      .1       0  154.08    .041       0  256.88      .1       0
Bank Sta=154.08,256.88
XS Rating Curve= 0 ,0
Exp/Cntr=0.3,0.1

Type RM Length L Ch R = 1 ,9966.96 ,66.54,91.44,106.97
XS GIS Cut Line= 5
     611075.7037    4339935.5817     611204.6854    4340050.7146
      611213.823    4340050.9598     611299.1319    4340105.9367
     611372.4643    4340166.4411
#Sta/Elev= 30
       0  495.79   12.13  493.09    18.2   491.1   30.33  482.93    36.4  479.47
   42.46  477.29   48.53  472.91   51.56  471.93   60.66  470.67   66.73  468.63
    72.8  465.96   78.86  464.27  151.66   461.8  160.76   460.2  166.83  458.53
  214.87  458.03  277.55  458.05  280.54   458.8  283.52  461.08  289.66   463.4
  295.79  464.76  320.32  467.47  326.46   469.4  332.59  472.32  338.73  474.55
  344.86  475.94  350.99  478.95  357.13  483.26  372.46  491.43  378.59  495.64
#Mann= 3 , 0 , 0
       0      .1       0  166.83    .041       0  280.54      .1       0
Bank Sta=166.83,280.54
XS Rating Curve= 0 ,0
Exp/Cntr=0.3,0.1

Type RM Length L Ch R = 1 ,9875.521,109.46,91.44,70.63
XS GIS Cut Line= 5
     610999.5035    4339981.0902     611145.6832    4340085.3751
     611178.0022     4340105.344     611218.4616    4340178.0294
     611303.6725    4340245.8162
#Sta/Elev= 30
       0  494.63    6.09  493.84   18.26  493.71   30.43  492.66   36.52   490.8
   51.74   487.9   54.78  487.04   57.83  485.46      70  480.65   76.09  477.65
   85.22  472.16    91.3  469.22  121.74   463.6  127.83  462.95  188.33  461.18
  193.54  460.22   197.1  458.87  200.02  458.54  271.03     458  318.89     458
  324.94  458.65  334.01  461.13  352.16  468.75  355.19  469.37  376.36  477.08
  394.51  486.75  400.55  488.99  403.58     491   406.6  494.16  409.63  496.52
#Mann= 3 , 0 , 0
       0      .1       0  193.54    .041       0  324.94      .1       0
Bank Sta=193.54,324.94
XS Rating Curve= 0 ,0
Exp/Cntr=0.3,0.1

Type RM Length L Ch R = 1 ,9784.08 ,94.64,91.44,84.27
XS GIS Cut Line= 6
     610965.0018    4340085.0716      611087.263    4340178.9319
     611117.6017    4340195.6273     611156.0305    4340224.5596
     611179.3382    4340235.2883     611268.2711    4340285.7067
#Sta/Elev= 30
       0   495.2   18.13  486.91   21.16  486.33   24.18   485.3   36.27  480.67
   42.31  477.03    54.4  470.77   57.42  469.22   60.45  468.33   66.49  465.05
   72.53  464.01    81.6     461  102.76   460.8  157.02  461.07  159.91   460.8
  165.68     459  169.91  458.24  185.88     458  283.57     458  292.59  458.75
  307.63  460.62  310.63  461.96  319.65  466.74  328.67  472.24  334.69  476.27
  337.69   477.6   340.7  478.38  349.72  483.33  355.73  488.16  364.76   494.1
#Mann= 3 , 0 , 0
       0      .1       0  169.91    .041       0  292.59      .1       0
Bank Sta=169.91,292.59
XS Rating Curve= 0 ,0
Exp/Cntr=0.3,0.1

Type RM Length L Ch R = 1 ,9692.641,101.75,91.44,80.75
XS GIS Cut Line= 4
     610886.6423    4340156.9715     611066.5408    4340277.4618
     611144.0269    4340312.0789      611217.471    4340350.2651
#Sta/Elev= 30
       0  494.08   15.25   489.1   21.35  488.69    24.4  488.09    36.6  485.42
   42.69  483.33   48.79  480.79   51.84  478.49   60.99  473.35   67.09  471.06
   76.24  465.08   79.29  464.32  103.69  461.18  118.93  460.21  137.23  460.23
  182.98  461.44  187.18  460.05  189.07  458.99  192.12  458.08  195.17  457.99
  325.91     458  328.98  458.03  332.05  458.86  341.24  463.94  353.51  471.61
  359.64  477.21  365.77  480.55  374.97   487.3  378.03  490.83  384.17  495.97
#Mann= 3 , 0 , 0
       0      .1       0  187.18    .041       0  332.05      .1       0
Bank Sta=187.18,332.05
XS Rating Curve= 0 ,0
Exp/Cntr=0.3,0.1

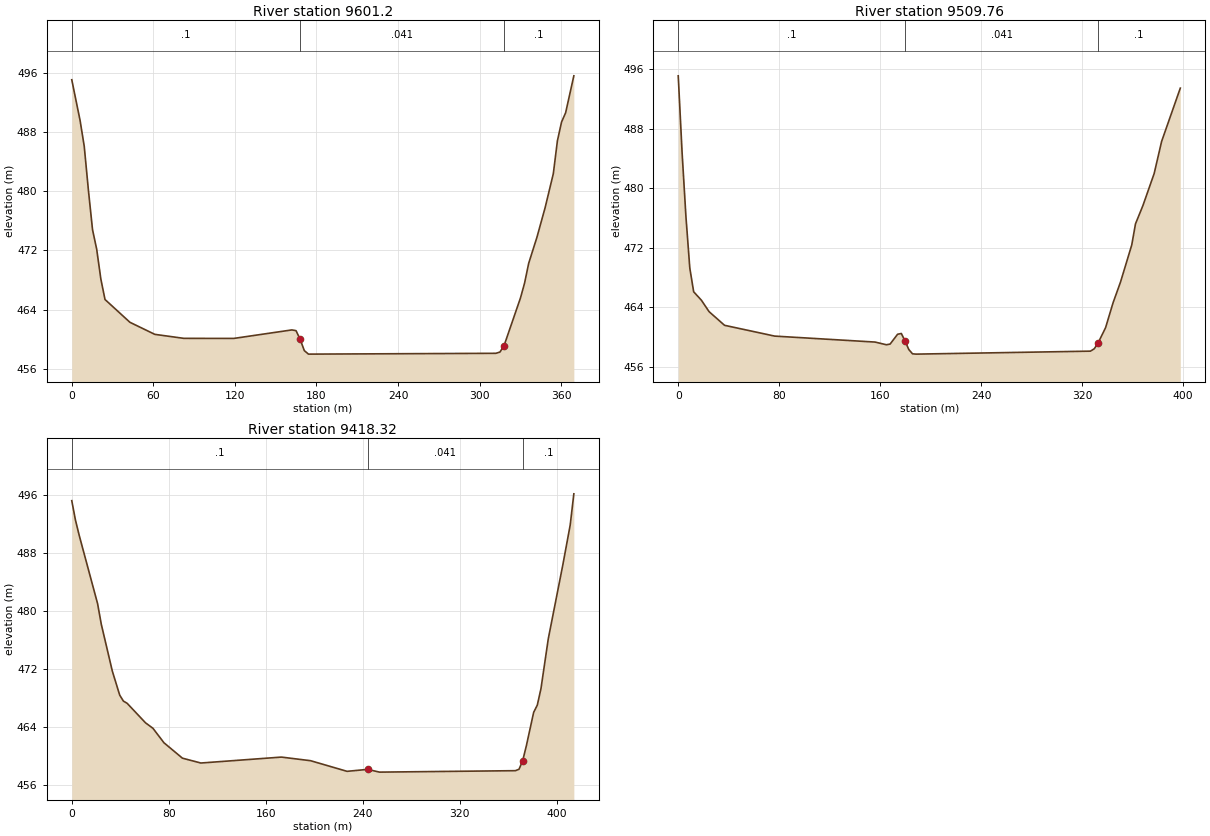
Type RM Length L Ch R = 1 ,9601.2  ,80.82,91.44,94.9
XS GIS Cut Line= 4
     610847.4907    4340253.8739     611015.5992    4340365.1651
     611085.2097    4340379.5168     611178.3126    4340405.2986
#Sta/Elev= 30
       0  495.05    6.11  489.56    9.16  486.08   12.22  480.17   15.27   474.8
   18.33  472.16   21.38  468.15   24.44  465.37   42.77  462.29   61.09  460.66
   82.48  460.12  119.13  460.11   161.9  461.26  164.95  461.16  168.01  459.97
  171.06  458.46  174.12  457.99  311.93   458.1  314.95  458.27  317.97  459.14
  330.04  465.58  333.06  467.59  336.08  470.26  342.12  473.76  348.16  477.77
   354.2  482.37  357.21  486.81  360.23  489.33  363.25  490.59  369.29  495.58
#Mann= 3 , 0 , 0
       0      .1       0  168.01    .041       0  317.97      .1       0
Bank Sta=168.01,317.97
XS Rating Curve= 0 ,0
Exp/Cntr=0.3,0.1

Type RM Length L Ch R = 1 ,9509.76 ,103.76,91.44,105.44
XS GIS Cut Line= 6
     610790.6206    4340334.3333     610933.4869    4340404.1722
     610978.4852    4340432.7099     611058.9429    4340472.9035
     611088.8505    4340478.8113     611151.8542    4340495.2571
#Sta/Elev= 30
       0   495.1    3.06  484.79    6.12  476.15    9.17  469.29   12.23   466.1
   18.35  464.97   24.46  463.43    36.7   461.6   76.45  460.15  155.96  459.35
  164.94  458.99   167.9  459.08  173.82   460.4  176.78   460.5  179.74  459.49
   182.7  458.35  185.67  457.77  188.63  457.73  326.63  458.13  329.68  458.45
  332.73  459.24  338.65  461.29  344.57  464.63  350.49  467.42  359.37  472.39
  362.33  475.22  368.25  477.69  377.13  481.98  383.05   486.3  397.85  493.45
#Mann= 3 , 0 , 0
       0      .1       0  179.74    .041       0  332.73      .1       0
Bank Sta=179.74,332.73
XS Rating Curve= 0 ,0
Exp/Cntr=0.3,0.1

Type RM Length L Ch R = 1 ,9418.32 ,70.68,91.31,107.2
XS GIS Cut Line= 6
     610704.7759     4340386.591     610808.0455    4340456.6441
     610896.4452    4340502.0682     610939.0734    4340515.2364
     611015.2876    4340553.3101     611065.0707    4340587.3323
#Sta/Elev= 30
       0  495.28    3.04   492.6    6.09  490.51   21.31  481.03   24.35  478.19
   33.48  471.69   39.57  468.37   42.61  467.55   45.65  467.25   60.87  464.54
   66.96  463.79   76.09  461.78   91.31  459.65  106.53  458.98  172.98   459.8
  197.07   459.3  227.15  457.83  244.18   458.1  253.92  457.72  366.05  457.92
  369.06  458.12  372.08  459.31  375.09  461.36  381.12  465.99  384.14     467
  387.15  469.27  393.18  476.16  405.24  486.44  411.27  491.91  414.28  496.23
#Mann= 3 , 0 , 0
       0      .1       0  244.18    .041       0  372.08      .1       0
Bank Sta=244.18,372.08
XS Rating Curve= 0 ,0
Exp/Cntr=0.3,0.1