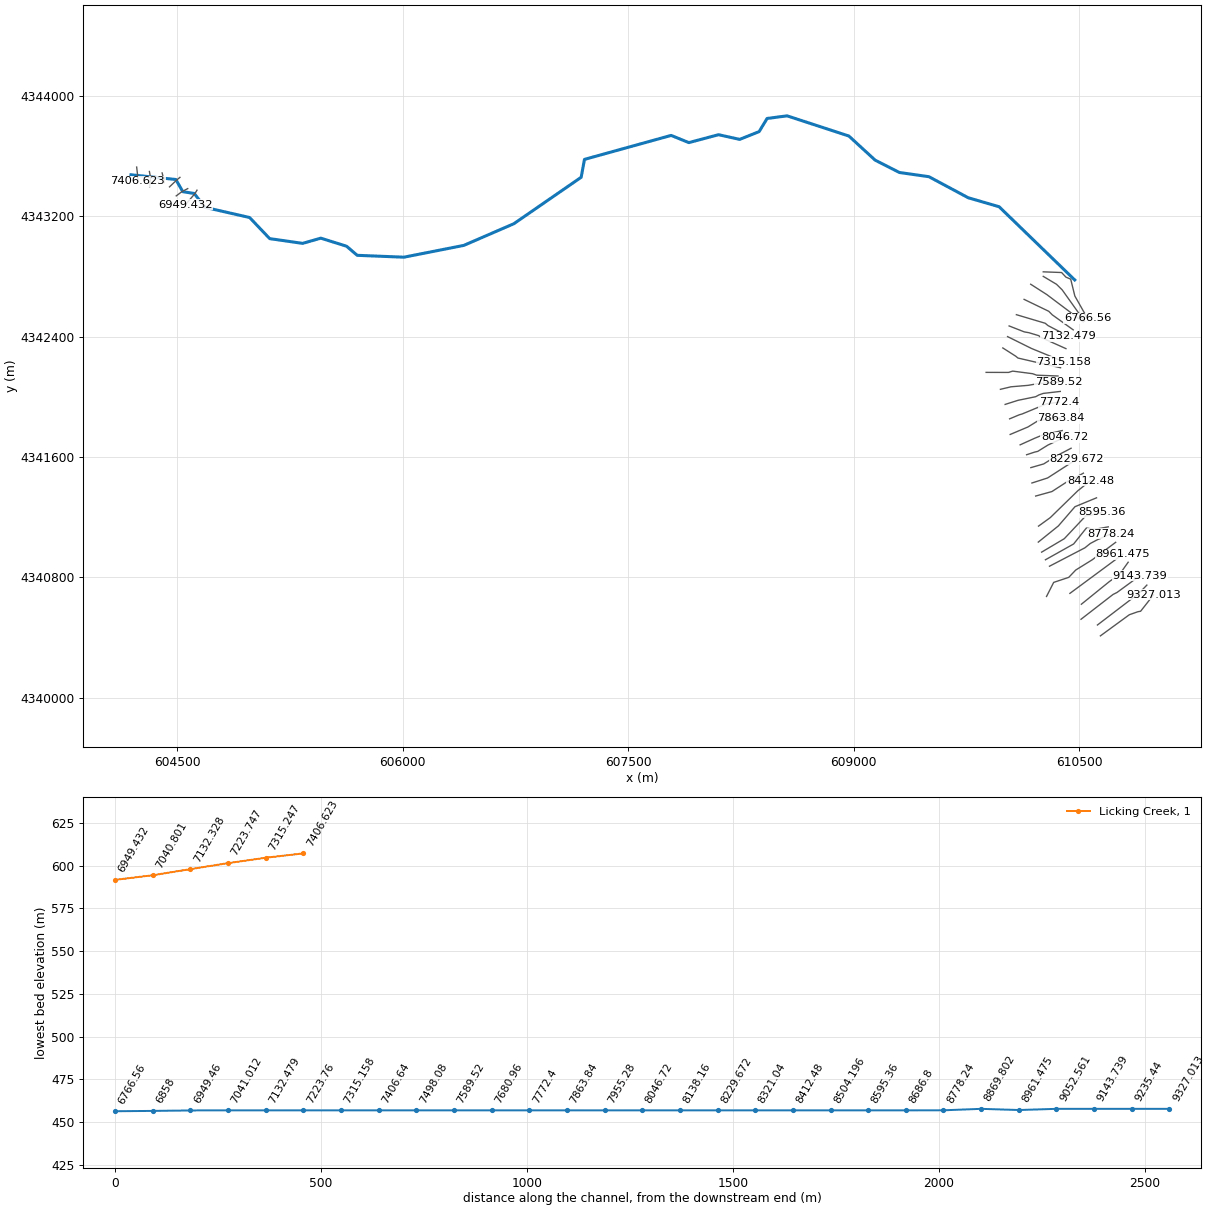
HEC-RAS study CheatRiver.prj: CheatRiver

--- CheatRiver.g01 (geometry) --- (continued)

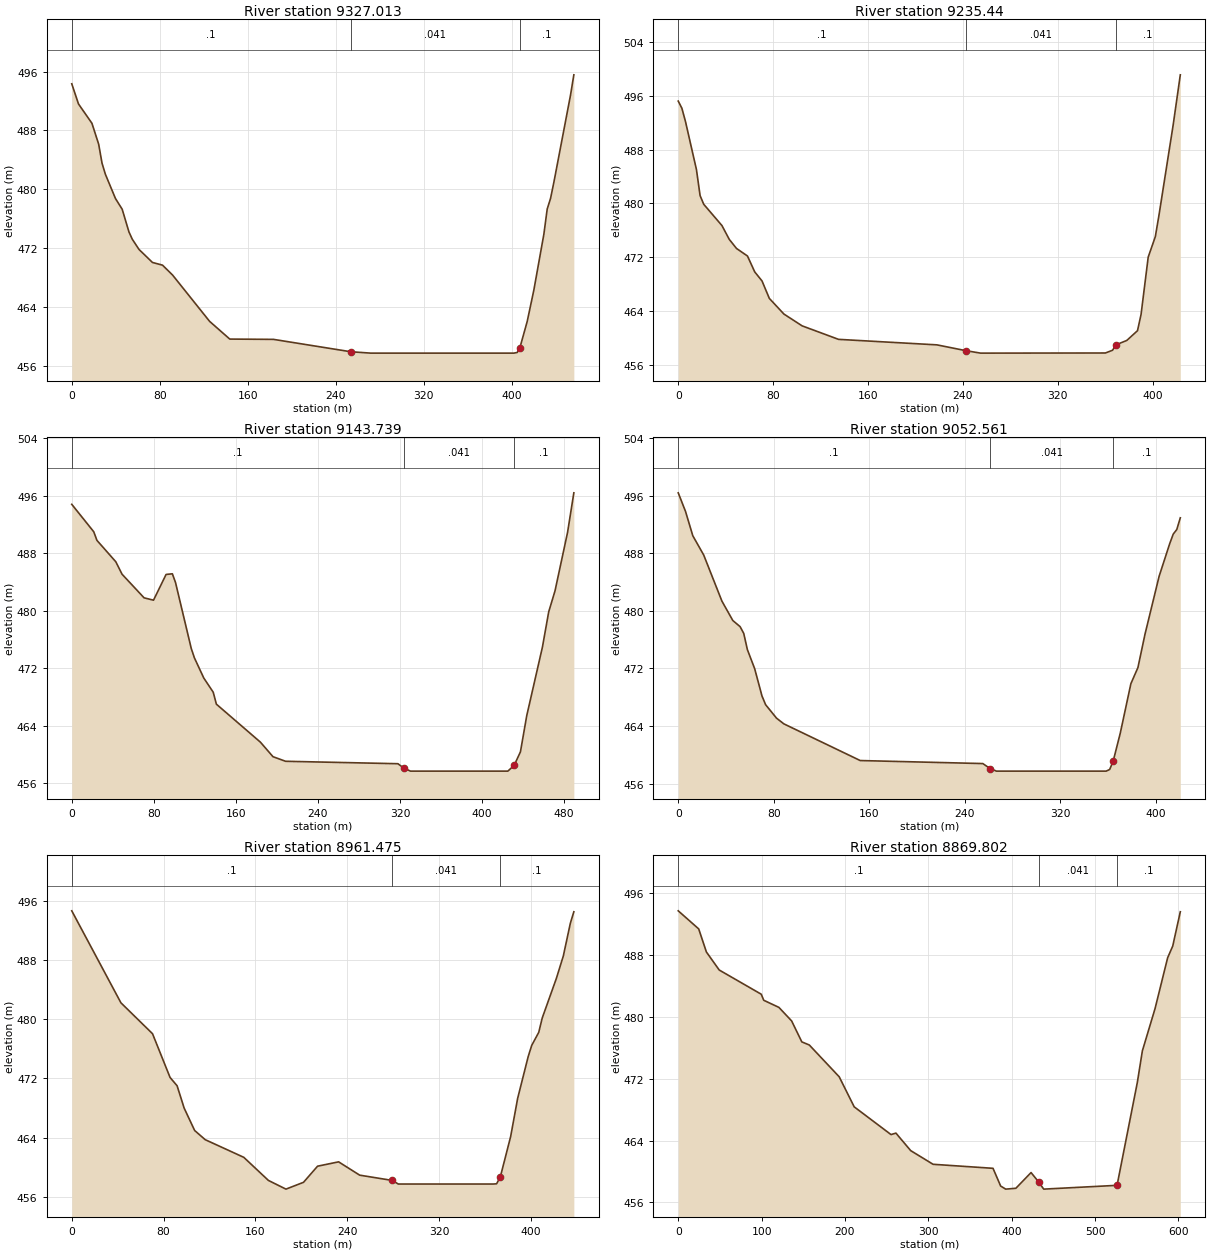
Type RM Length L Ch R = 1 ,9327.013,82.27,91.57,83.48
XS GIS Cut Line= 5
     610639.9958    4340410.2011     610832.4159    4340550.7737
      610889.566     4340570.882      610907.496    4340573.8744
     610993.5273    4340683.3233
#Sta/Elev= 30
       0  494.34    6.11   491.6   18.33  488.97   24.44  486.13    27.5  483.55
   30.55  482.04   39.72  478.74   45.83  477.28   51.94  474.21   54.99  473.21
    61.1  471.82   73.32  470.05   82.49  469.68   91.65  468.33  125.26  462.04
  143.59  459.63  183.31  459.59  253.44  457.91  271.62  457.72   401.8  457.72
  404.83  457.81  407.21  458.44  413.91  462.04  419.96  466.32  429.04   473.9
  432.06  477.31  435.09  478.75  438.12  480.95  453.25   492.8  456.27  495.56
#Mann= 3 , 0 , 0
       0      .1       0  253.44    .041       0  407.21      .1       0
Bank Sta=253.44,407.21
XS Rating Curve= 0 ,0
Exp/Cntr=0.3,0.1

Type RM Length L Ch R = 1 ,9235.44 ,100.35,91.7,88.2
XS GIS Cut Line= 4
      610620.247    4340482.5126     610854.6121    4340661.5362
     610890.3552    4340687.5312     610949.0772    4340747.8818
#Sta/Elev= 30
       0  495.24    3.07  494.18    6.14  492.18   15.36  485.04   18.43  481.17
    21.5  479.88   36.86  476.71   43.01  474.66   49.15   473.3   58.37  472.18
   64.51  469.81   70.66  468.46    76.8  465.87   89.09  463.54  104.45  461.78
  135.17  459.77  218.12  458.95  242.69  458.08  254.98  457.72  360.17  457.74
  366.18  458.15  369.19  458.96  378.21  459.61  387.23  461.06  390.24  463.49
  396.25  472.01  402.27  475.07  405.27  478.18   417.3  491.69  423.32  499.15
#Mann= 3 , 0 , 0
       0      .1       0  242.69    .041       0  369.19      .1       0
Bank Sta=242.69,369.19
XS Rating Curve= 0 ,0
Exp/Cntr=0.3,0.1

Type RM Length L Ch R = 1 ,9143.739,86.66,91.18,105.58
XS GIS Cut Line= 4
     610511.0112    4340520.6648     610724.2452    4340685.7644
     610750.9214    4340699.1901     610904.0979    4340811.3819
#Sta/Elev= 30
       0  494.82   21.45     491   24.52  489.81    42.9  486.84   49.03   485.1
   70.48  481.82   79.68  481.49   91.94  485.07   98.06  485.16  101.13  483.95
  116.45  474.79  119.52  473.48  128.71  470.66   137.9  468.69  140.97  467.03
  183.87  461.75  196.13  459.73  208.39  459.09  317.92  458.75  323.51  458.16
  330.17  457.72   425.1  457.72  431.23  458.52  437.35   460.4  443.48  465.42
  458.79  474.97  464.91  479.87  471.04  482.78  483.29  490.92  489.41  496.42
#Mann= 3 , 0 , 0
       0      .1       0  323.51    .041       0  431.23      .1       0
Bank Sta=323.51,431.23
XS Rating Curve= 0 ,0
Exp/Cntr=0.3,0.1

Type RM Length L Ch R = 1 ,9052.561,93.98,91.09,81.43
XS GIS Cut Line= 5
     610513.3924    4340620.6775     610700.6972    4340772.2833
     610731.0797    4340793.5627     610780.0782    4340837.3644
     610824.7228    4340900.0175
#Sta/Elev= 30
       0  496.38     6.1   493.8    12.2  490.42   21.35  487.74    36.6  481.34
   45.75  478.64   51.85  477.79    54.9  476.85   57.96  474.59   64.06  471.95
   70.16  468.17   73.21  466.95   82.36  465.08   88.46  464.29  152.51  459.19
  255.24  458.77  261.28  458.08  266.65  457.72  358.58  457.72  361.54  457.95
   364.5  459.13  370.42     463  379.29  469.86  385.21  472.11  391.13  476.74
  402.97  484.79  411.84  489.32   414.8  490.65  417.76  491.28  420.72  492.91
#Mann= 3 , 0 , 0
       0      .1       0  261.28    .041       0   364.5      .1       0
Bank Sta=261.28,364.5
XS Rating Curve= 0 ,0
Exp/Cntr=0.3,0.1

Type RM Length L Ch R = 1 ,8961.475,95.85,91.67,91.94
XS GIS Cut Line= 2
     610437.1923    4340692.9089     610789.0039    4340952.9342
#Sta/Elev= 30
       0  494.67   42.83  482.23   70.36  478.05   85.66  472.13   91.78  471.01
    97.9     468  107.07  464.96  116.25  463.72   149.9  461.33  171.32  458.21
  186.62  457.03  201.91  457.95  214.15  460.13   232.5  460.72  250.86  458.92
  279.09  458.21  284.51  457.72  367.11  457.72  370.17  457.75  373.44   458.7
  382.41  464.14  388.53  469.32   397.7  474.96  400.76  476.47  406.88  478.23
  409.94  480.18  422.18   485.5   428.3  488.56  434.42  492.99  437.47  494.54
#Mann= 3 , 0 , 0
       0      .1       0  279.09    .041       0  373.44      .1       0
Bank Sta=279.09,373.44
XS Rating Curve= 0 ,0
Exp/Cntr=0.3,0.1

Type RM Length L Ch R = 1 ,8869.802,92.81,91.56,82.09
XS GIS Cut Line= 6
      610281.617    4340672.2714     610329.2421    4340765.9341
     610429.2548    4340799.2717     610476.1162    4340848.2245
     610585.6332     4340916.287     610741.3788    4341032.3094
#Sta/Elev= 30
       0  493.69   24.58  491.35   33.79  488.37   49.16  486.04    99.6  482.91
  102.55  482.13  120.76  481.21  136.02  479.46  148.24  476.75  157.21  476.35
  193.09  472.24  211.04  468.36  255.23  464.77  261.13  464.96  278.81   462.7
  305.69  460.93  377.59  460.41  386.73  458.12  392.81  457.72  404.99  457.83
  423.21  459.86  432.31  458.65  438.38  457.72  526.38  458.21  550.66  471.49
  556.73  475.59   571.9  481.04  587.07  487.63  593.14  489.13  602.24  493.57
#Mann= 3 , 0 , 0
       0      .1       0  432.31    .041       0  526.38      .1       0
Bank Sta=432.31,526.38
XS Rating Curve= 0 ,0
Exp/Cntr=0.3,0.1

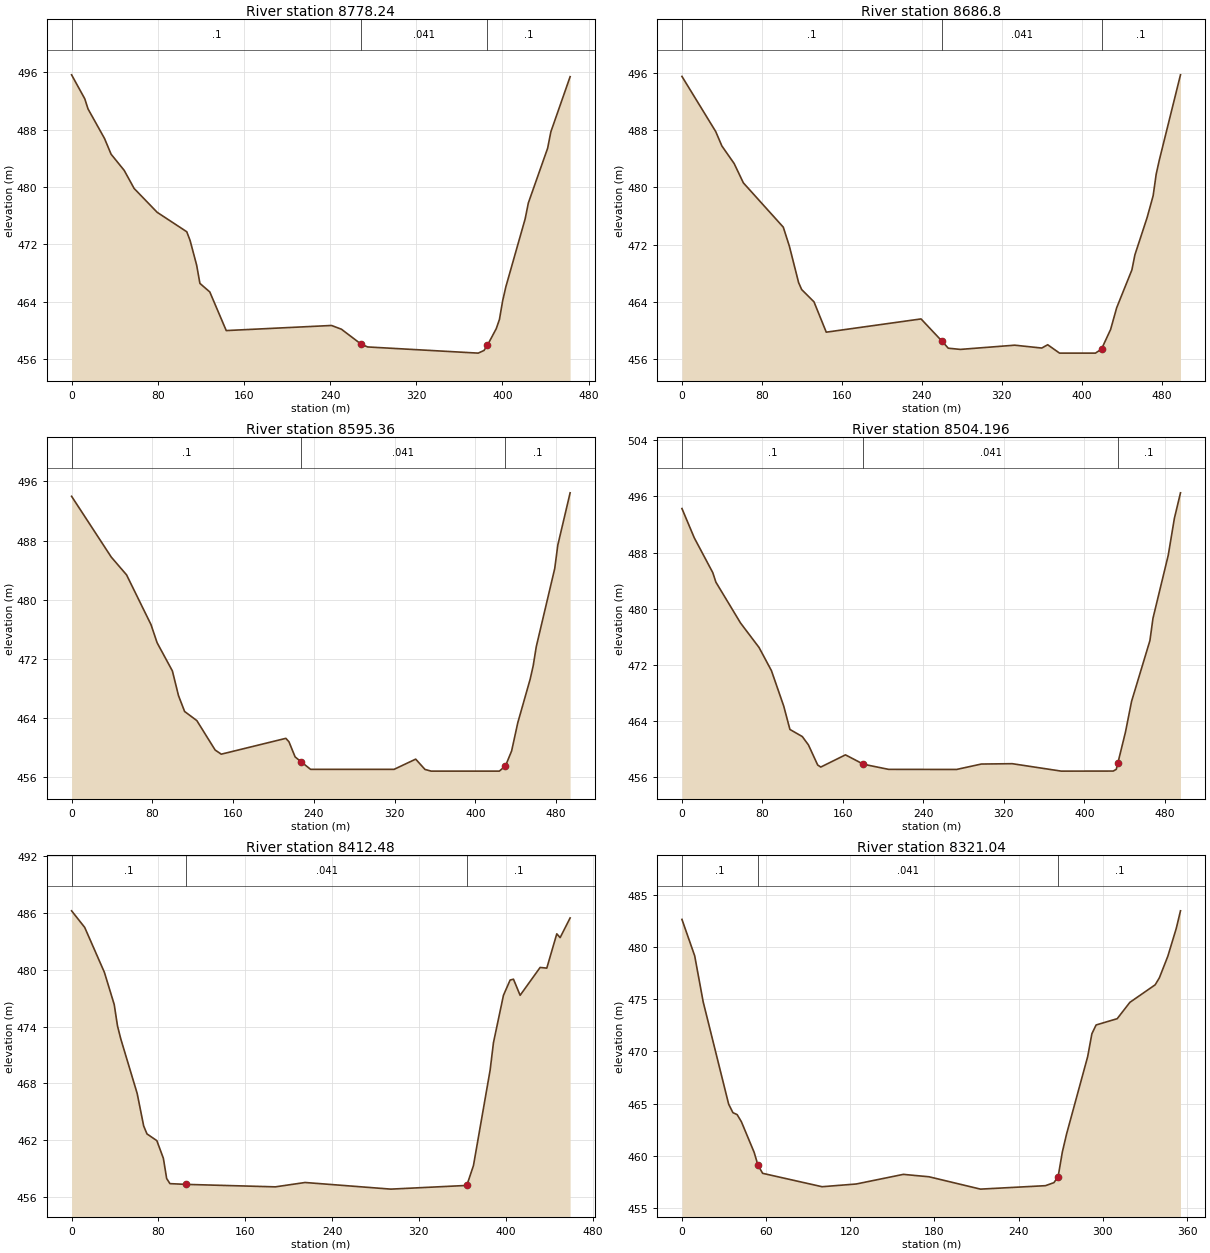
Type RM Length L Ch R = 1 ,8778.24 ,70.75,91.44,68.79
XS GIS Cut Line= 6
     610301.3946    4340873.5205     610537.1778    4340996.1168
     610572.6458    4341024.6037      610621.621    4341050.6217
     610641.5815    4341058.6908     610709.6288    4341089.1949
#Sta/Elev= 30
       0  495.62   12.22  492.29   15.27  490.87   30.55  486.76   36.66  484.57
   48.87  482.31   58.04   479.8   79.42  476.48  106.91  473.77  109.97  472.57
  116.08  469.13  119.13  466.58  128.29  465.39  143.57  460.01  241.31  460.72
  250.48   460.2  268.78  458.12  274.85  457.73  377.46  456.87  382.85  457.24
  386.09  457.99   394.2  460.27  397.18  461.56  400.16  464.15  403.14  466.11
  421.04  475.56  424.02  477.78  441.92   485.4   444.9  487.68   462.8  495.36
#Mann= 3 , 0 , 0
       0      .1       0  268.78    .041       0  386.09      .1       0
Bank Sta=268.78,386.09
XS Rating Curve= 0 ,0
Exp/Cntr=0.3,0.1

Type RM Length L Ch R = 1 ,8686.8  ,69.97,91.44,98.68
XS GIS Cut Line= 5
     610274.4071    4340916.3831     610462.0359     4341021.583
     610546.9552    4341127.8788     610599.6255    4341118.3244
     610692.3206    4341135.3869
#Sta/Elev= 30
       0  495.52    33.8  487.81   39.95   485.8   52.24  483.34   61.46  480.64
  101.41  474.45  107.55  471.77  116.77  466.69  119.85  465.72  132.14  464.01
  144.43  459.77   239.3  461.62  260.46  458.48  266.51  457.53   278.6  457.36
  333.02  457.95  360.08  457.55  366.03  458.01  377.92  456.84  413.81  456.84
  419.89   457.4  429.01  460.15  435.09  463.19   450.3  468.47  453.34  470.59
   465.5  475.77  471.58  478.84  474.62  481.86  477.66  483.77  498.94  495.74
#Mann= 3 , 0 , 0
       0      .1       0  260.46    .041       0  419.89      .1       0
Bank Sta=260.46,419.89
XS Rating Curve= 0 ,0
Exp/Cntr=0.3,0.1

Type RM Length L Ch R = 1 ,8595.36 ,88.22,91.16,94.79
XS GIS Cut Line= 5
      610249.007    4340967.1832      610399.958    4341056.7065
     610542.5985    4341208.4207     610579.1791    4341213.4857
     610649.9872      4341231.96
#Sta/Elev= 30
       0  493.98   39.34  485.76   54.47  483.36   78.67  476.64   84.72  474.19
   99.85  470.38  105.91  467.04  111.96   464.9  124.06  463.67  142.22  459.69
  148.27  459.13  212.25  461.27  215.31  460.81  221.44  458.76  227.56  458.08
  236.75  457.08  319.43  457.08  340.87  458.46  350.05  457.07  356.18  456.84
  423.72  456.84  429.82  457.55  435.92  459.58  442.01  463.39  454.21  469.24
  457.26  471.07  460.31  473.66   478.6  484.22  481.65  487.39  493.85  494.45
#Mann= 3 , 0 , 0
       0      .1       0  227.56    .041       0  429.82      .1       0
Bank Sta=227.56,429.82
XS Rating Curve= 0 ,0
Exp/Cntr=0.3,0.1

Type RM Length L Ch R = 1 ,8504.196,77.32,91.72,99.29
XS GIS Cut Line= 4
      610226.782    4341033.8583      610360.535    4341141.6379
     610470.9386    4341269.4439     610614.2683    4341328.5331
#Sta/Elev= 30
       0  494.27   12.27  490.09   30.67  485.13   33.74  483.78   58.28  477.95
   76.68  474.46   88.95  471.17  101.22   466.1  107.36  462.78  119.63  461.77
  125.76  460.58  134.97  457.71  138.03  457.42  162.57  459.16  180.49  457.82
  205.55  457.09  273.11  457.08  297.67  457.85  328.38   457.9  377.14  456.84
  428.82  456.85  431.86   457.1  433.44     458  440.98   462.4  447.06  466.79
   465.3  475.45  468.34  478.63  483.54  487.63  489.62  492.87  495.69  496.51
#Mann= 3 , 0 , 0
       0      .1       0  180.49    .041       0  433.44      .1       0
Bank Sta=180.49,433.44
XS Rating Curve= 0 ,0
Exp/Cntr=0.3,0.1

Type RM Length L Ch R = 1 ,8412.48 ,167.23,91.44,85
XS GIS Cut Line= 4
     610228.3695     4341140.221     610306.6744    4341196.8897
     610489.4026    4341375.0497     610573.2578    4341442.3041
#Sta/Elev= 30
       0  486.23   12.08  484.48   30.21  479.74   39.27  476.34   42.29  474.08
   45.31  472.71   60.41  466.95   66.45   463.5   69.47  462.67   78.54  461.96
   84.58  460.09    87.6  457.96   90.62  457.42  105.77  457.34   187.8  457.08
  215.15  457.54  294.14  456.84  364.15  457.23  370.29  459.33  385.65  469.41
  388.72  472.31  397.93  477.31  404.08  478.92  407.15  479.01  413.29  477.31
  431.72  480.25  437.86  480.18  447.07   483.8  450.15   483.4  459.36  485.48
#Mann= 3 , 0 , 0
       0      .1       0  105.77    .041       0  364.15      .1       0
Bank Sta=105.77,364.15
XS Rating Curve= 0 ,0
Exp/Cntr=0.3,0.1

Type RM Length L Ch R = 1 ,8321.04 ,95.7,91.37,96.48
XS GIS Cut Line= 5
     610209.4884    4341340.2963     610317.4111    4341370.1989
     610432.8504    4341444.7718     610442.3222    4341446.7913
     610526.9557    4341492.5751
#Sta/Elev= 30
       0  482.62    9.08  479.14   15.13  474.74   33.29  464.96   36.32  464.15
   39.35  463.96   42.37  463.28   51.45  460.36   54.14  459.14   57.51  458.35
   99.88  457.07   124.2  457.33   157.8  458.25  176.12  458.02  212.77  456.84
   259.1  457.17  265.12  457.46  268.13  458.04  271.13  460.39  274.14  462.11
  289.17   469.5  292.18  471.69  295.19  472.53  310.22  473.13  319.24  474.69
  337.29  476.37  340.29  477.04  346.31   479.1  352.32  481.76  355.33  483.44
#Mann= 3 , 0 , 0
       0      .1       0   54.14    .041       0  268.13      .1       0
Bank Sta=54.14,268.13
XS Rating Curve= 0 ,0
Exp/Cntr=0.3,0.1

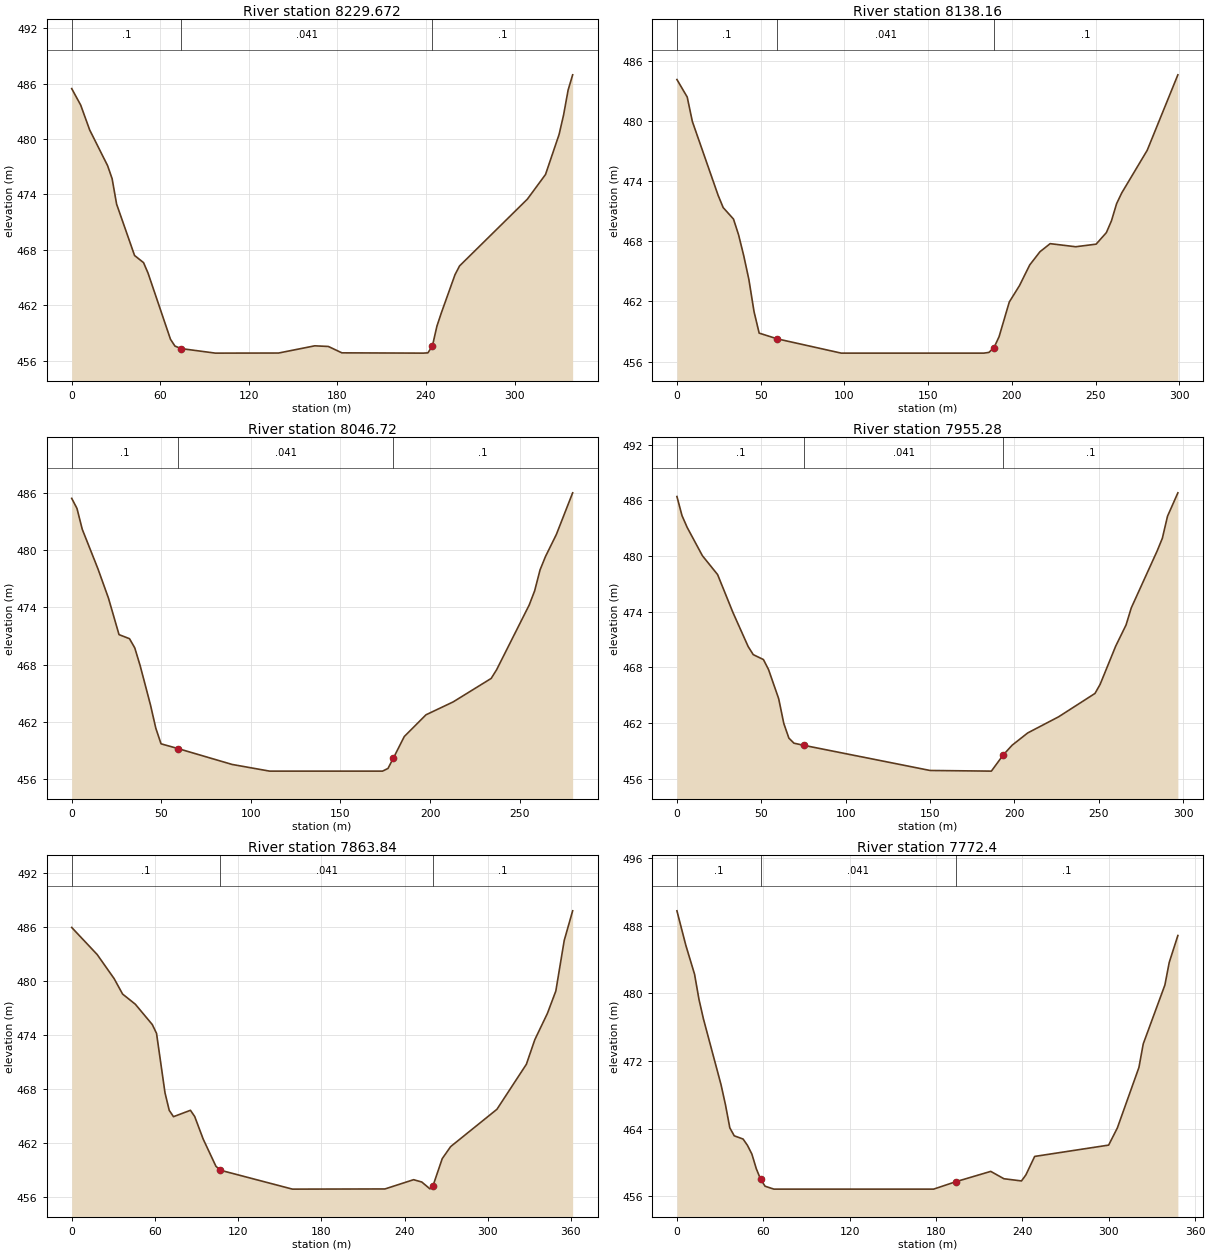
Type RM Length L Ch R = 1 ,8229.672,98.21,91.51,91.03
XS GIS Cut Line= 3
     610184.5514    4341427.0798     610288.7919    4341460.5711
     610481.9764    4341585.1794
#Sta/Elev= 30
       0  485.45    6.08  483.67   12.17  480.98   24.33  477.11   27.37  475.71
   30.41  472.96   42.58   467.4   48.66  466.63    51.7   465.5   66.91  458.34
   69.95   457.6   74.19  457.33   97.32  456.84  140.14  456.85  164.66  457.63
  173.86  457.56  183.05  456.87  238.22  456.84  241.29  456.87  244.35  457.61
  247.42  459.76  250.49  461.23  259.68  465.33  262.75  466.27  308.72   473.5
  320.98  476.16  330.18  480.49  333.24  482.61  336.31   485.3  339.37  486.94
#Mann= 3 , 0 , 0
       0      .1       0   74.19    .041       0  244.35      .1       0
Bank Sta=74.19,244.35
XS Rating Curve= 0 ,0
Exp/Cntr=0.3,0.1

Type RM Length L Ch R = 1 ,8138.16 ,92.94,91.44,89.81
XS GIS Cut Line= 4
     610177.3283    4341529.2974      610262.875    4341553.9237
     610350.4544    4341608.8464     610445.1111    4341658.2928
#Sta/Elev= 30
       0  484.18    6.14  482.43    9.21  479.99   24.56  472.63   27.63  471.38
   33.77  470.24   36.84  468.65   39.91  466.57   42.98  464.19   46.05  460.99
   49.11  458.84   60.06  458.26   98.14  456.84  183.28  456.84  186.32  456.91
  189.36  457.39   192.4  458.48   198.5  461.95   204.6  463.59   210.7  465.65
  216.81  466.97  222.91  467.78  238.17  467.47  250.37  467.73  256.47  468.88
  259.52  470.06  262.58  471.77  265.63  472.84  280.88  477.11  299.19  484.65
#Mann= 3 , 0 , 0
       0      .1       0   60.06    .041       0  189.36      .1       0
Bank Sta=60.06,189.36
XS Rating Curve= 0 ,0
Exp/Cntr=0.3,0.1

Type RM Length L Ch R = 1 ,8046.72 ,83.8,91.44,68.24
XS GIS Cut Line= 5
     610149.1501    4341615.0226     610202.0669    4341632.4851
     610223.2939    4341637.4962      610291.973    4341680.0117
     610401.8075    4341731.4061
#Sta/Elev= 30
       0  485.41    2.93  484.36    5.87  482.18   14.66  478.02   20.53  474.95
    26.4  471.14   32.26  470.71   35.19  469.75   38.13  467.93   41.06  465.85
   43.99  463.75   46.93  461.34   49.86   459.7   59.19  459.21    89.5  457.54
  110.44  456.84  173.47  456.84   176.5  457.12  179.53  458.21  185.59  460.46
  197.72  462.74  212.88  464.09   234.1  466.55  237.13  467.46  255.32  474.24
  258.35  475.72  261.38  477.92  264.41  479.32  270.48  481.63  279.57  485.99
#Mann= 3 , 0 , 0
       0      .1       0   59.19    .041       0  179.53      .1       0
Bank Sta=59.19,179.53
XS Rating Curve= 0 ,0
Exp/Cntr=0.3,0.1

Type RM Length L Ch R = 1 ,7955.28 ,87.57,91.44,98.07
XS GIS Cut Line= 4
     610106.0876    4341680.9423     610202.2505    4341724.4432
     610257.0833    4341747.0982     610385.9325    4341775.8562
#Sta/Elev= 30
       0  486.41    3.02  484.35    6.03   483.1   15.08  480.04   24.12     478
   33.17  473.93   42.22  470.25   45.23  469.38   51.26  468.85   54.28  467.78
   60.31  464.63   63.33  461.97   66.34  460.39   69.36  459.84   75.46   459.6
  150.04   456.9  186.36  456.83  193.32  458.56  198.65  459.62  207.86  460.94
  226.28  462.69  247.77   465.2  250.84  466.19  260.05   470.3  266.19  472.58
  269.26  474.41  284.61  480.55  287.68  481.91  290.75  484.29  296.89  486.81
#Mann= 3 , 0 , 0
       0      .1       0   75.46    .041       0  193.32      .1       0
Bank Sta=75.46,193.32
XS Rating Curve= 0 ,0
Exp/Cntr=0.3,0.1

Type RM Length L Ch R = 1 ,7863.84 ,97.07,91.44,98.07
XS GIS Cut Line= 5
     610039.8314    4341749.9435     610158.1848    4341799.8272
     610223.5005    4341840.2446     610284.0989    4341852.9921
     610377.9949    4341858.4064
#Sta/Elev= 30
       0  485.95   18.35  482.94   30.58  480.26    36.7  478.54   45.87  477.41
    58.1  475.15   61.16  474.17   67.28  467.55   70.33   465.6   73.39   464.9
   85.62  465.61   88.68  464.92    94.8  462.41  103.97  459.39  107.03  458.95
  159.16  456.84  225.89  456.86  246.53  457.89  252.43  457.63  258.32  456.87
  260.53  457.22  267.17  460.23  273.24  461.57  306.61  465.72  327.85  470.73
  333.92  473.46  343.02  476.39  349.09  478.88  355.15  484.51  361.22   487.8
#Mann= 3 , 0 , 0
       0      .1       0  107.03    .041       0  260.53      .1       0
Bank Sta=107.03,260.53
XS Rating Curve= 0 ,0
Exp/Cntr=0.3,0.1

Type RM Length L Ch R = 1 ,7772.4  ,94.55,91.44,73.85
XS GIS Cut Line= 5
     610036.0862    4341853.8279      610101.073    4341881.0379
     610119.7174    4341886.3477     610283.2073    4341954.1969
     610363.7074    4341964.7691
#Sta/Elev= 30
       0  489.78    6.13  485.73   12.25  482.27   15.32   479.3   18.38  477.01
   30.63  469.21    33.7  466.84   36.76  464.09   39.82  463.15   45.95  462.77
   49.01  462.02   52.07  460.99   55.14  459.26    58.2  457.98   61.26  457.18
   67.39  456.84  178.34  456.84   193.6  457.71  218.02  458.94  227.17  458.07
  239.38  457.81  242.43  458.52  248.54  460.71  299.93  462.05  305.94  464.06
  320.98  471.24  323.98  474.03  339.02     481  342.03  483.67  348.04  486.86
#Mann= 3 , 0 , 0
       0      .1       0    58.2    .041       0   193.6      .1       0
Bank Sta=58.2,193.6
XS Rating Curve= 0 ,0
Exp/Cntr=0.3,0.1

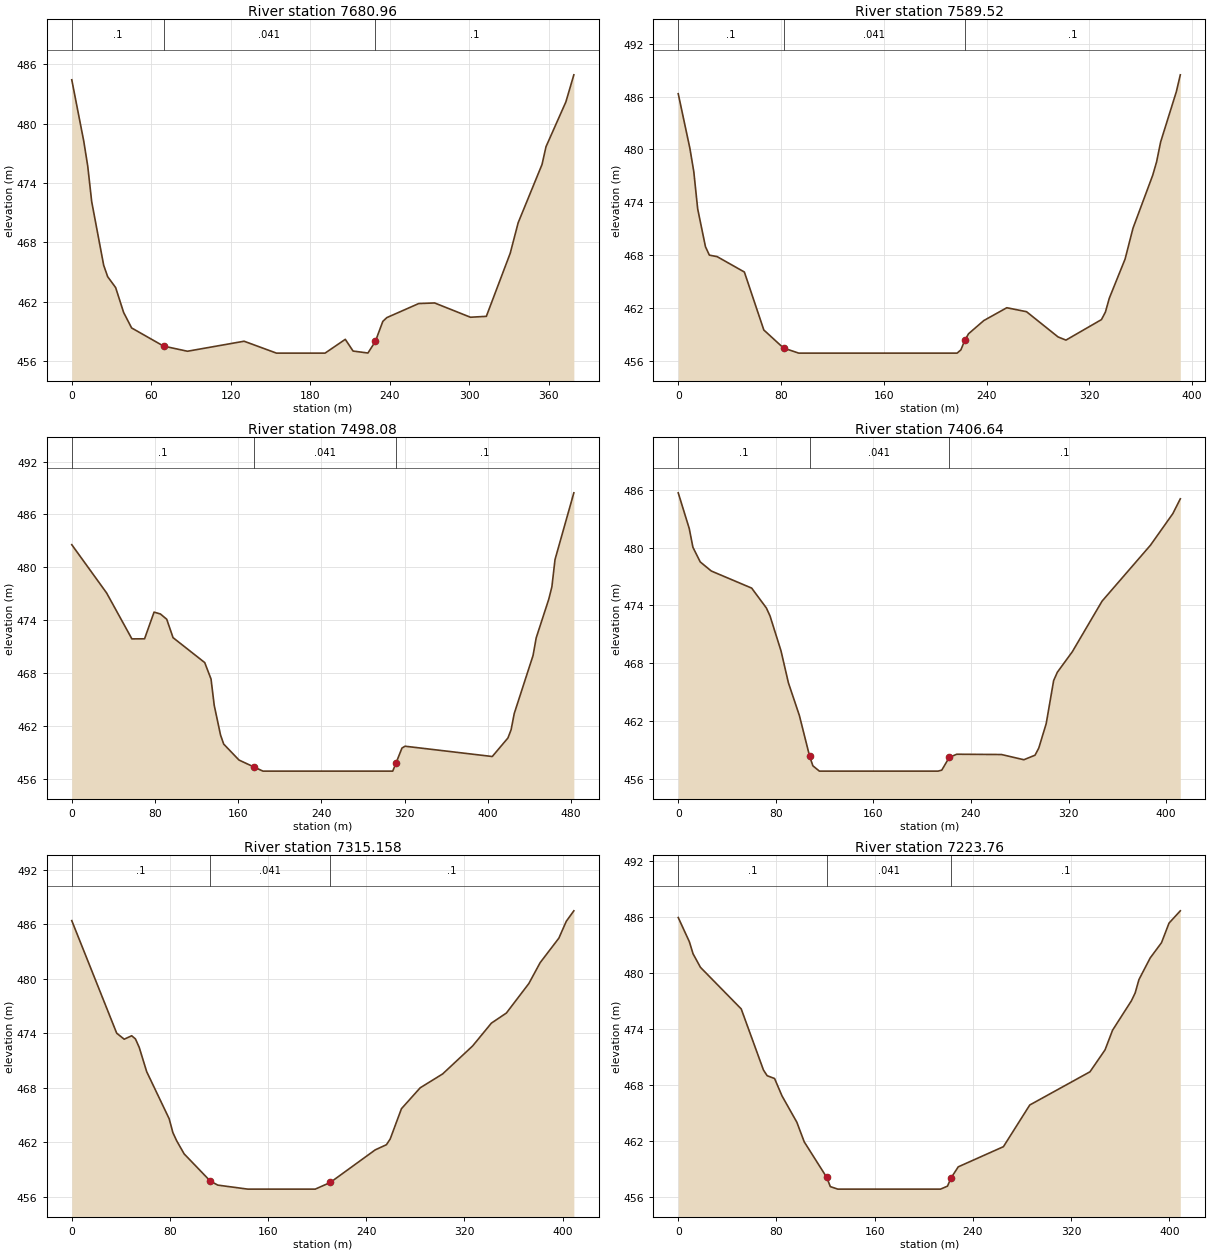
Type RM Length L Ch R = 1 ,7680.96 ,100.34,91.44,83.68
XS GIS Cut Line= 6
     610006.3024    4341949.8184     610092.4399    4341977.1565
     610209.2305    4342001.0529     610231.4335    4342013.1116
     610259.8762    4342023.0335     610373.2324    4342036.2067
#Sta/Elev= 30
       0  484.41    9.04  478.23   12.05  475.71   15.06  472.11    24.1   465.7
   27.11  464.55   33.14  463.45   39.16  460.94   45.19  459.38   69.29  457.55
   87.36  457.03  130.11  458.04  154.56  456.84  191.24  456.84  206.53  458.23
  212.39  457.05  223.62  456.85  229.23  458.02  234.85  460.04  237.86  460.42
  261.96  461.84  273.98   461.9  301.01  460.46  313.02  460.55  331.04  466.91
  337.05  469.99  355.07  475.87  358.07  477.66  373.08  482.18  379.09  484.91
#Mann= 3 , 0 , 0
       0      .1       0   69.29    .041       0  229.23      .1       0
Bank Sta=69.29,229.23
XS Rating Curve= 0 ,0
Exp/Cntr=0.3,0.1

Type RM Length L Ch R = 1 ,7589.52 ,101.98,91.44,69.77
XS GIS Cut Line= 5
     609975.0084    4342050.2462     610045.7229    4342067.0893
     610160.0091    4342076.7559     610224.3228    4342088.1873
     610362.1199    4342098.1194
#Sta/Elev= 30
       0  486.33    9.09  480.11   12.12  477.46   15.14  473.24    21.2  468.94
   24.23  467.98   30.29  467.81   51.49  466.06   66.63  459.47   81.97  457.42
   93.82  456.84  217.08  456.84  220.05  457.21  223.02  458.28  225.99  459.04
  237.86  460.54  255.78     462  271.13  461.55  295.69  458.68  301.83  458.32
  329.46  460.65  332.53   461.5   335.6  463.09  347.88  467.54  354.02  471.04
  369.37  477.06  372.44  478.61  375.51  480.83  387.79  486.57  390.86  488.48
#Mann= 3 , 0 , 0
       0      .1       0   81.97    .041       0  223.02      .1       0
Bank Sta=81.97,223.02
XS Rating Curve= 0 ,0
Exp/Cntr=0.3,0.1

Type RM Length L Ch R = 1 ,7498.08 ,116.5,91.44,85.51
XS GIS Cut Line= 6
      609879.784    4342162.9082     610028.9028    4342162.5794
     610056.6841    4342171.3107      610188.554    4342154.1669
     610216.2282    4342144.3231     610357.8866    4342138.8653
#Sta/Elev= 30
       0  482.56   33.48  477.08   57.82  471.86   69.99  471.87   79.12   474.9
   85.21  474.69    91.3  474.09   97.38     472  127.82  469.17   133.9   467.3
  136.95  464.32  143.03  460.94  146.08  459.91  160.77   458.1  175.33   457.3
  183.85  456.84  308.59  456.84  311.59  457.71  317.46  459.46   320.4  459.67
   404.3   458.5  419.38  460.61   422.4  461.54  425.41  463.38  443.51  469.98
  446.53  471.98  458.59  476.36  461.61  477.78  464.62  480.87  482.72  488.45
#Mann= 3 , 0 , 0
       0      .1       0  175.33    .041       0  311.59      .1       0
Bank Sta=175.33,311.59
XS Rating Curve= 0 ,0
Exp/Cntr=0.3,0.1

Type RM Length L Ch R = 1 ,7406.64 ,92.51,91.48,76.64
XS GIS Cut Line= 5
     609990.8834    4342325.4134     610077.1232    4342270.2651
     610091.5225    4342258.3129     610219.8569    4342228.6422
     610374.8199    4342193.8987
#Sta/Elev= 30
       0  485.67    9.03  481.97   12.04  480.03   18.06  478.51    27.1  477.57
   60.21   475.8   72.26  473.74   75.27  472.91    84.3  469.28   90.32  465.99
   99.35  462.59  107.67   458.4  110.39  457.39  115.73  456.84  212.98  456.84
  216.04  456.94  222.17  458.26  228.29  458.59  265.01  458.56  283.34  458.02
   292.5  458.49  295.55  459.22  301.66  461.76  307.77  466.22  310.83  467.09
  323.04   469.2  347.47  474.45  387.18  480.25   405.5  483.52  411.61  485.05
#Mann= 3 , 0 , 0
       0      .1       0  107.67    .041       0  222.17      .1       0
Bank Sta=107.67,222.17
XS Rating Curve= 0 ,0
Exp/Cntr=0.3,0.1

Type RM Length L Ch R = 1 ,7315.158,82.76,91.4,91.73
XS GIS Cut Line= 3
     610022.5805    4342400.8463     610181.1934    4342322.1694
     610395.9866    4342234.1155
#Sta/Elev= 30
       0  486.39   36.63     474   42.74  473.34   48.84  473.72    51.9  473.37
   54.95  472.45   61.05  469.77   79.37  464.59   82.42  463.06   85.47  462.17
   91.58  460.72  112.95  457.72  119.05  457.28  143.47  456.84  198.44  456.84
  210.65  457.57  247.31  461.16  256.47  461.73  259.53  462.36  268.69  465.69
  283.96  467.99  302.29  469.52  326.72   472.6     342  475.11  354.21  476.22
  372.54  479.47  381.71  481.76  396.98  484.46  403.09  486.33   409.2  487.47
#Mann= 3 , 0 , 0
       0      .1       0  112.95    .041       0  210.65      .1       0
Bank Sta=112.95,210.65
XS Rating Curve= 0 ,0
Exp/Cntr=0.3,0.1

Type RM Length L Ch R = 1 ,7223.76 ,93.55,91.28,97.05
XS GIS Cut Line= 6
     610032.7581     4342471.845     610133.9294    4342432.1639
     610163.9594    4342426.9605     610229.8785    4342407.1551
     610242.9379    4342396.1805     610410.8033     4342320.899
#Sta/Elev= 30
       0  485.96    9.06  483.37   12.08  482.07   18.11  480.62   51.32  476.16
   69.43  469.61   72.45     469   78.49   468.7   84.52  466.84    96.6  464.02
  102.64  461.91  120.87  458.12  123.91  457.11  130.01  456.84  213.67  456.84
  219.35  457.16   222.2  458.03  228.11  459.23   264.9  461.39  286.37  465.86
  335.42  469.42  347.69  471.77  353.82  473.88  369.15  477.03  372.22  477.87
  375.29   479.3  384.48  481.63  393.68  483.26  399.81  485.36  409.01  486.68
#Mann= 3 , 0 , 0
       0      .1       0  120.87    .041       0   222.2      .1       0
Bank Sta=120.87,222.2
XS Rating Curve= 0 ,0
Exp/Cntr=0.3,0.1

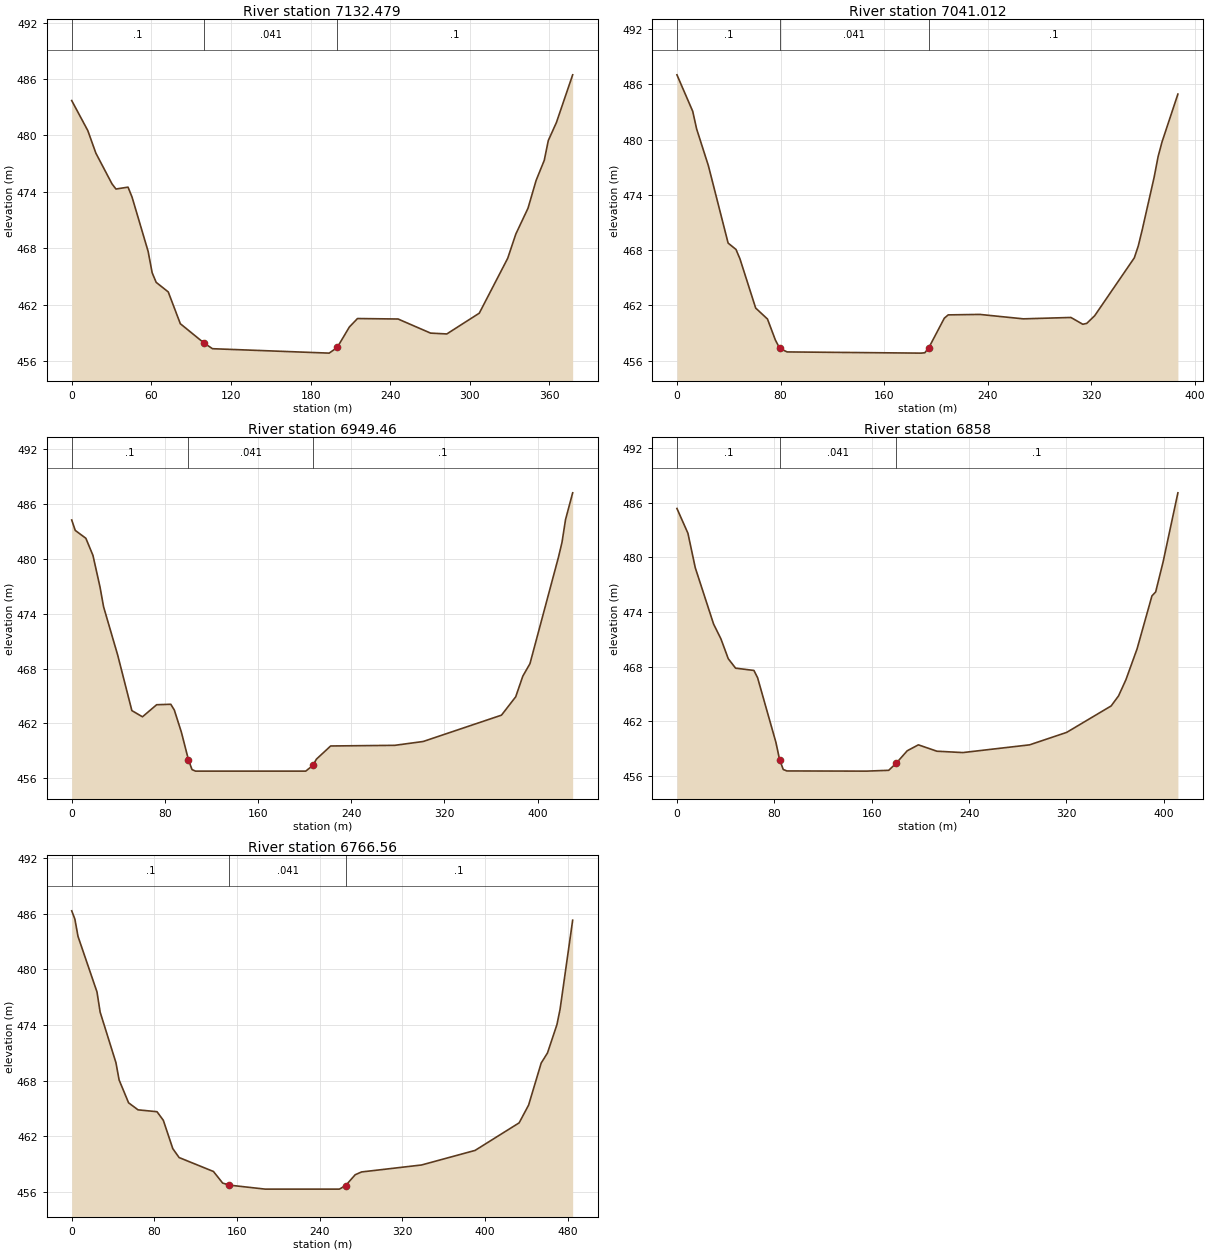
Type RM Length L Ch R = 1 ,7132.479,102.24,91.47,76.9
XS GIS Cut Line= 4
     610081.1255    4342546.7309     610272.8803    4342489.7132
     610291.6654    4342474.0564     610427.3939    4342403.4921
#Sta/Elev= 30
       0   483.7   12.12  480.51   18.19  478.11   30.31  474.85   33.34  474.29
   42.44  474.49   45.47  473.43   57.59  467.65   60.62  465.38   63.65  464.36
   72.75  463.34   81.84  459.96  100.03  457.87  106.09   457.3  193.99  456.83
  200.05  457.43  209.22  459.61  215.34  460.51  245.92  460.46   270.4  458.96
  282.64  458.87  307.11  461.08  328.53  466.92  334.65   469.5  343.83  472.25
  349.95  475.21  356.07  477.34  359.12  479.45  365.24  481.37  377.48  486.44
#Mann= 3 , 0 , 0
       0      .1       0  100.03    .041       0  200.05      .1       0
Bank Sta=100.03,200.05
XS Rating Curve= 0 ,0
Exp/Cntr=0.3,0.1

Type RM Length L Ch R = 1 ,7041.012,101.48,91.55,86.89
XS GIS Cut Line= 4
     610132.4832    4342648.5333     610296.6372    4342569.1681
     610319.9428    4342545.6732     610459.1439    4342445.8255
#Sta/Elev= 30
       0  487.03   12.16  483.08   15.19  481.16   24.31  477.15   39.51  468.77
   45.58  468.08   48.62  467.07   60.78  461.72   69.89  460.53   75.97  458.26
   79.36  457.34   85.09  456.96  188.35  456.83  191.36  456.87  194.37   457.4
   206.4  460.62  209.41  460.98  233.78  461.03  267.43  460.55  304.14   460.7
  313.32  459.96  316.38  460.06  322.49  460.89  353.08  467.17  356.14  468.46
   359.2  470.22  368.38  475.91  371.44  478.15   374.5  479.76  386.73  484.94
#Mann= 3 , 0 , 0
       0      .1       0   79.36    .041       0  194.37      .1       0
Bank Sta=79.36,194.37
XS Rating Curve= 0 ,0
Exp/Cntr=0.3,0.1

Type RM Length L Ch R = 1 ,6949.46 ,96.66,91.46,76.37
XS GIS Cut Line= 3
     610176.3198    4342749.2187     610283.7178    4342680.3476
     610525.5016    4342498.5836
#Sta/Elev= 30
       0  484.24    3.04   483.1   12.15  482.24   18.23  480.37    24.3  476.91
   27.34  474.76   39.49  469.46   51.64   463.4   60.75  462.72    72.9  464.04
   85.06  464.09   88.09  463.46   94.17  461.03  100.24  458.01  103.28  456.95
  106.32  456.78  200.91  456.78  207.02   457.4  210.08  458.09   222.3  459.53
   277.3   459.6  301.74  460.02  368.96   462.9  381.18  464.91  387.29  467.17
   393.4  468.53  417.85  480.16   420.9  481.79  423.96  484.29  430.07  487.21
#Mann= 3 , 0 , 0
       0      .1       0  100.24    .041       0  207.02      .1       0
Bank Sta=100.24,207.02
XS Rating Curve= 0 ,0
Exp/Cntr=0.3,0.1

Type RM Length L Ch R = 1 ,6858    ,84.14,91.44,60.64
XS GIS Cut Line= 4
     610259.8374    4342801.5343     610347.7806    4342749.1053
     610385.7948    4342711.7251     610534.2328    4342503.3461
#Sta/Elev= 30
       0  485.39    9.03  482.66   15.06  478.87   30.11  472.68   36.14  471.05
   42.16  468.87   48.18  467.83   63.24  467.58   66.25  466.78   81.31  459.67
   84.32  457.78   87.33  456.69   90.34  456.53   155.7  456.51  173.97   456.6
  180.07  457.37   189.2  458.75  198.34   459.4  213.57   458.7  234.89  458.55
  289.71   459.4  320.17  460.77  356.72  463.68  362.81  464.79   368.9  466.58
  378.04  469.97  390.22  475.78  393.27  476.21  399.36   479.5  411.54  487.11
#Mann= 3 , 0 , 0
       0      .1       0   84.32    .041       0  180.07      .1       0
Bank Sta=84.32,180.07
XS Rating Curve= 0 ,0
Exp/Cntr=0.3,0.1

Type RM Length L Ch R = 1 ,6766.56 ,85.23,91.44,82.2
XS GIS Cut Line= 6
     610259.7859    4342831.7823     610381.9767    4342827.0912
     610410.4195     4342796.664     610442.5354    4342782.8481
     610469.9509    4342670.9867      610553.984    4342522.5019
#Sta/Elev= 30
       0   486.3    3.06  485.41    6.11  483.54   24.46  477.56   27.51  475.39
    42.8  469.94   45.86  468.08   55.03  465.62    64.2  464.86   82.54  464.66
   88.65  463.73   97.82  460.68  103.94  459.72  137.16  458.22  146.08  456.97
  152.64  456.75  187.24  456.32  258.99  456.32  265.11  456.71   274.3  457.87
  280.43  458.17  338.48  458.92  390.28  460.49  432.93  463.46  442.07  465.37
  454.26   469.9  460.35  470.99  469.49  474.04  472.54   475.7  484.72  485.29
#Mann= 3 , 0 , 0
       0      .1       0  152.64    .041       0  265.11      .1       0
Bank Sta=152.64,265.11
XS Rating Curve= 0 ,0
Exp/Cntr=0.3,0.1

River Reach=Licking Creek   ,1
Reach XY= 30
     604191.3463    4343477.3976     604489.6646    4343445.9783
604536.2634433434343364.87622796     604612.3654    4343353.0432
604683.2749650524343260.87768498604980.5290422394343193.02621142
     605114.0825    4343052.7405     605333.0603    4343021.0741
     605454.0728    4343055.7171     605625.3908    4343002.1388
      605696.256    4342941.5929     606006.9851    4342929.1648
     606405.5833    4343007.6251     606738.4272    4343151.8121
     607186.1994    4343460.7477     607207.9313    4343579.6442
     607784.5918    4343739.1883     607902.4657    4343691.3137
     608099.7112    4343743.9508608240.5517806764343712.73925264
     608369.9836    4343764.5883     608422.9007     4343851.957
     608555.9878    4343869.3786608966.7240660914343735.15447016
609141.4012142834343574.81498867     609302.9081    4343492.6112
609499.2369420174343464.55634823     609760.6382    4343324.6004
     609966.2303    4343264.7304     610469.2423     4342777.681

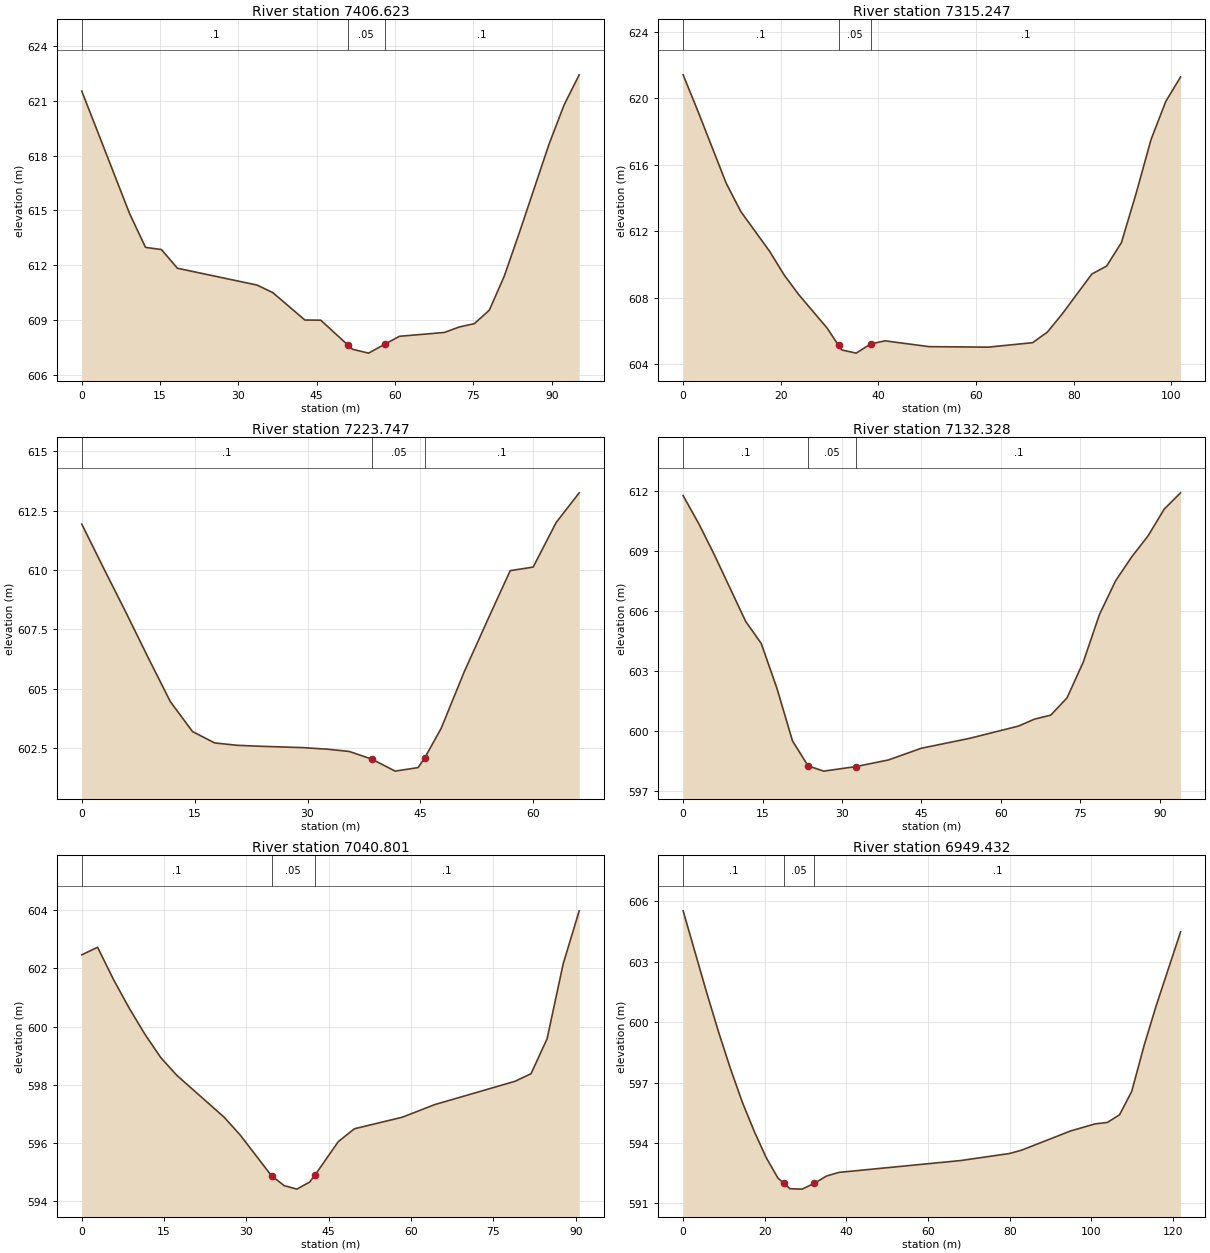
Type RM Length L Ch R = 1 ,7406.623,91.21,91.38,90.96
XS GIS Cut Line= 3
     604229.2391    4343528.7011     604235.9145    4343471.1097
     604236.9756    4343433.8353
#Sta/Elev= 23
       0  621.52    9.15  614.83   12.21  612.98   15.26  612.86   18.31  611.84
   33.57  610.92   36.62   610.5   42.72  609.01   45.77     609    50.9  607.66
   51.87  607.41   54.93   607.2   57.98  607.68   60.85  608.12   69.45  608.33
   72.32  608.63   75.19  608.81   78.06  609.55   80.92  611.41   83.79  613.77
   89.53  618.65    92.4  620.78   95.27  622.41
#Mann= 3 , 0 , 0
       0      .1       0    50.9     .05       0   57.98      .1       0
Bank Sta=50.9,57.98
XS Rating Curve= 0 ,0
Exp/Cntr=0.3,0.1

Type RM Length L Ch R = 1 ,7315.247,90.58,91.5,90.34
XS GIS Cut Line= 3
     604314.0117     4343499.253     604321.9497    4343455.6547
     604315.5992    4343398.4465
#Sta/Elev= 25
       0  621.42    2.95  619.29    8.86  614.87   11.82  613.19   17.73  610.79
   20.68  609.38   23.63  608.21   29.54  606.16   31.83  605.13    32.5  604.86
   35.45  604.67   38.41  605.22   41.36  605.41   50.37  605.06   62.49  605.03
   71.58   605.3   74.61  605.94   77.64  607.03    83.7  609.43   86.73  609.91
   89.76  611.32   92.79   614.3   95.82  617.52   98.85  619.82  101.87  621.29
#Mann= 3 , 0 , 0
       0      .1       0   31.83     .05       0   38.41      .1       0
Bank Sta=31.83,38.41
XS Rating Curve= 0 ,0
Exp/Cntr=0.3,0.1

Type RM Length L Ch R = 1 ,7223.747,97.8,91.42,83.86
XS GIS Cut Line= 3
     604398.7478    4343489.6794     604405.8415    4343461.1289
     604412.4369    4343425.0372
#Sta/Elev= 25
       0  611.93    2.94  610.05    5.88   608.2    8.83   606.3   11.77  604.45
   14.71  603.19   17.65  602.71   20.59  602.61   23.53  602.57   29.42  602.51
   32.32  602.45   32.48  602.45   35.53  602.35   36.38  602.26   38.59  602.02
   41.65  601.52   44.71  601.67    45.6  602.09   47.76  603.32   50.82   605.7
   53.88  607.85   56.94  609.97   59.99  610.12   63.05     612   66.11  613.25
#Mann= 3 , 0 , 0
       0      .1       0   38.59     .05       0    45.6      .1       0
Bank Sta=38.59,45.6
XS Rating Curve= 0 ,0
Exp/Cntr=0.3,0.1

Type RM Length L Ch R = 1 ,7132.328,91.37,91.53,86.22
XS GIS Cut Line= 3
     604517.1038    4343460.1173     604496.5594     4343443.291
     604447.7589     4343396.859
#Sta/Elev= 24
       0  611.76    2.95  610.36     5.9   608.8    11.8  605.48   14.75  604.37
    17.7  602.14   20.65   599.5    23.6  598.25   26.56  597.99   32.68  598.22
    38.8  598.55   44.93  599.13   54.11  599.63    63.3  600.24   66.36  600.59
   69.42  600.79   72.48  601.65   75.54  603.43   78.61  605.82   81.67  607.51
   84.73  608.71   87.79  609.75   90.85  611.09   93.92   611.9
#Mann= 3 , 0 , 0
       0      .1       0    23.6     .05       0   32.68      .1       0
Bank Sta=23.6,32.68
XS Rating Curve= 0 ,0
Exp/Cntr=0.3,0.1

Type RM Length L Ch R = 1 ,7040.801,90.5,91.37,86.3
XS GIS Cut Line= 4
     604568.8483    4343385.3267     604538.2543    4343369.2244
     604530.0776    4343364.9209     604492.4825    4343336.9988
#Sta/Elev= 23
       0  602.46    2.88  602.72    5.76  601.62    8.64  600.63   11.52  599.73
   14.41  598.93   17.29  598.33   25.93  596.89   28.81  596.29   34.57  594.88
   36.88  594.54   39.19  594.42    41.5  594.66   42.49   594.9   46.74  596.05
   49.67  596.49   58.45  596.89    64.3  597.32   78.94  598.12   81.86  598.38
   84.79  599.58   87.72  602.15   90.64  603.97
#Mann= 3 , 0 , 0
       0      .1       0   34.57     .05       0   42.49      .1       0
Bank Sta=34.57,42.49
XS Rating Curve= 0 ,0
Exp/Cntr=0.3,0.1

Type RM Length L Ch R = 1 ,6949.432,94.37,91.43,84.98
XS GIS Cut Line= 3
     604630.6213    4343374.8684     604616.9525    4343352.5668
     604555.0238    4343279.6254
#Sta/Elev= 25
       0  605.53    5.81  601.44    8.72  599.49   11.63  597.67   14.53  596.01
   17.44  594.57   20.34  593.28   23.25  592.25   24.75  591.99   26.16  591.73
   29.15  591.71   32.14     592   35.13  592.36   38.12  592.54   68.02  593.13
   79.98  593.48   82.97  593.65   94.93   594.6  100.91  594.95   103.9  595.02
  106.89   595.4  109.88  596.56  112.87  598.81  115.86  600.81  121.84  604.48
#Mann= 3 , 0 , 0
       0      .1       0   24.75     .05       0   32.14      .1       0
Bank Sta=24.75,32.14
XS Rating Curve= 0 ,0
Exp/Cntr=0.3,0.1