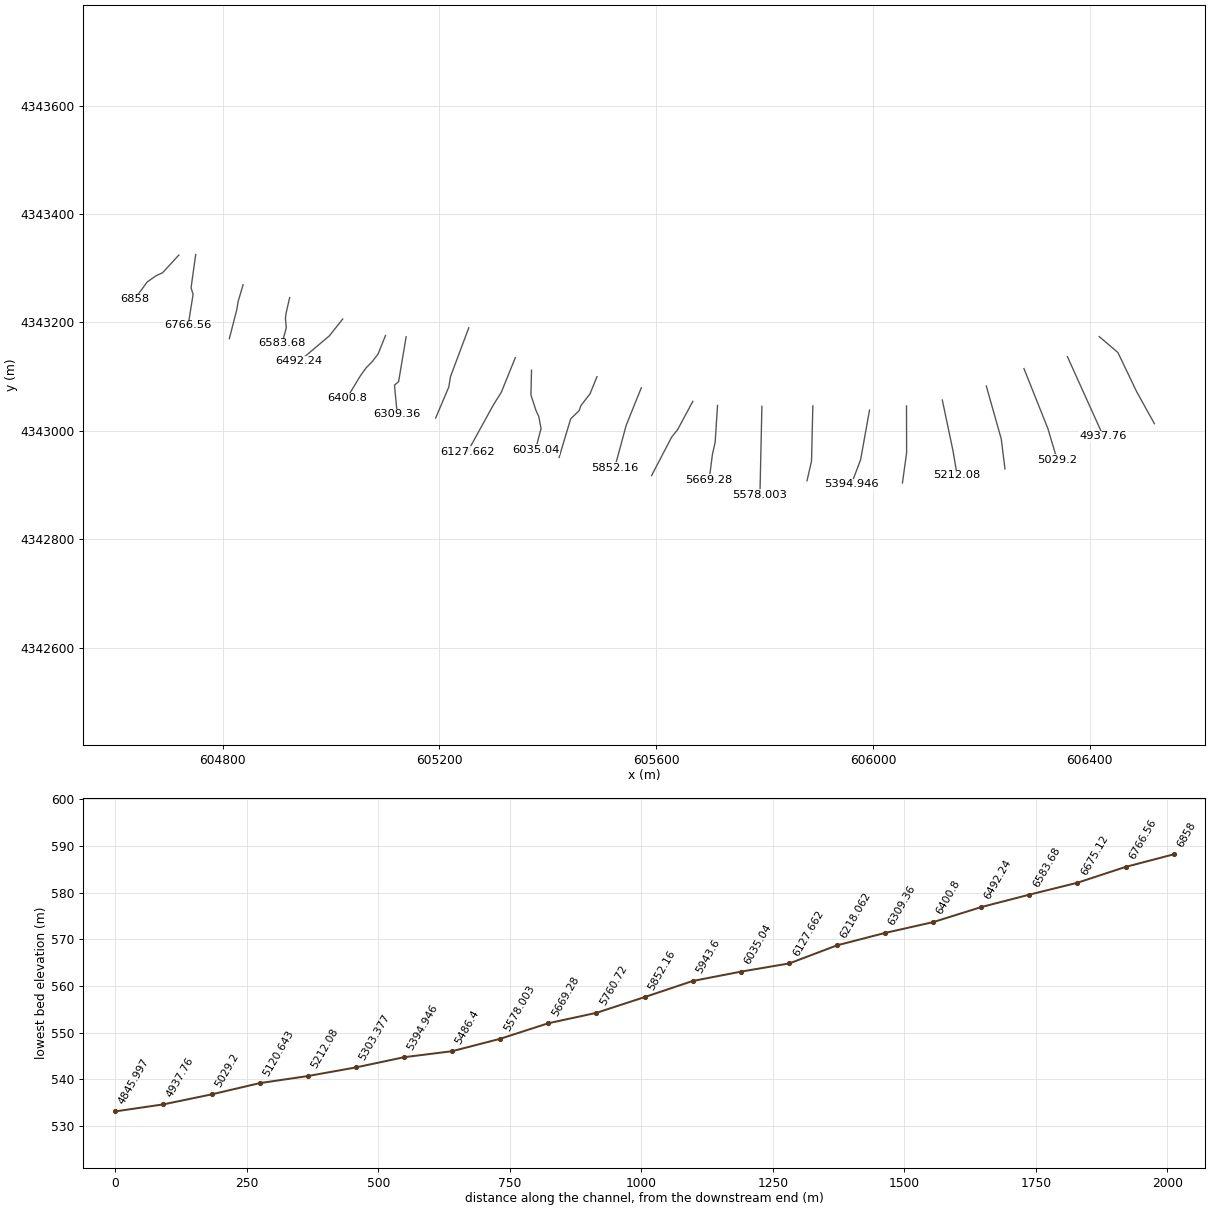
HEC-RAS study CheatRiver.prj: CheatRiver

--- CheatRiver.g01 (geometry) --- (continued)

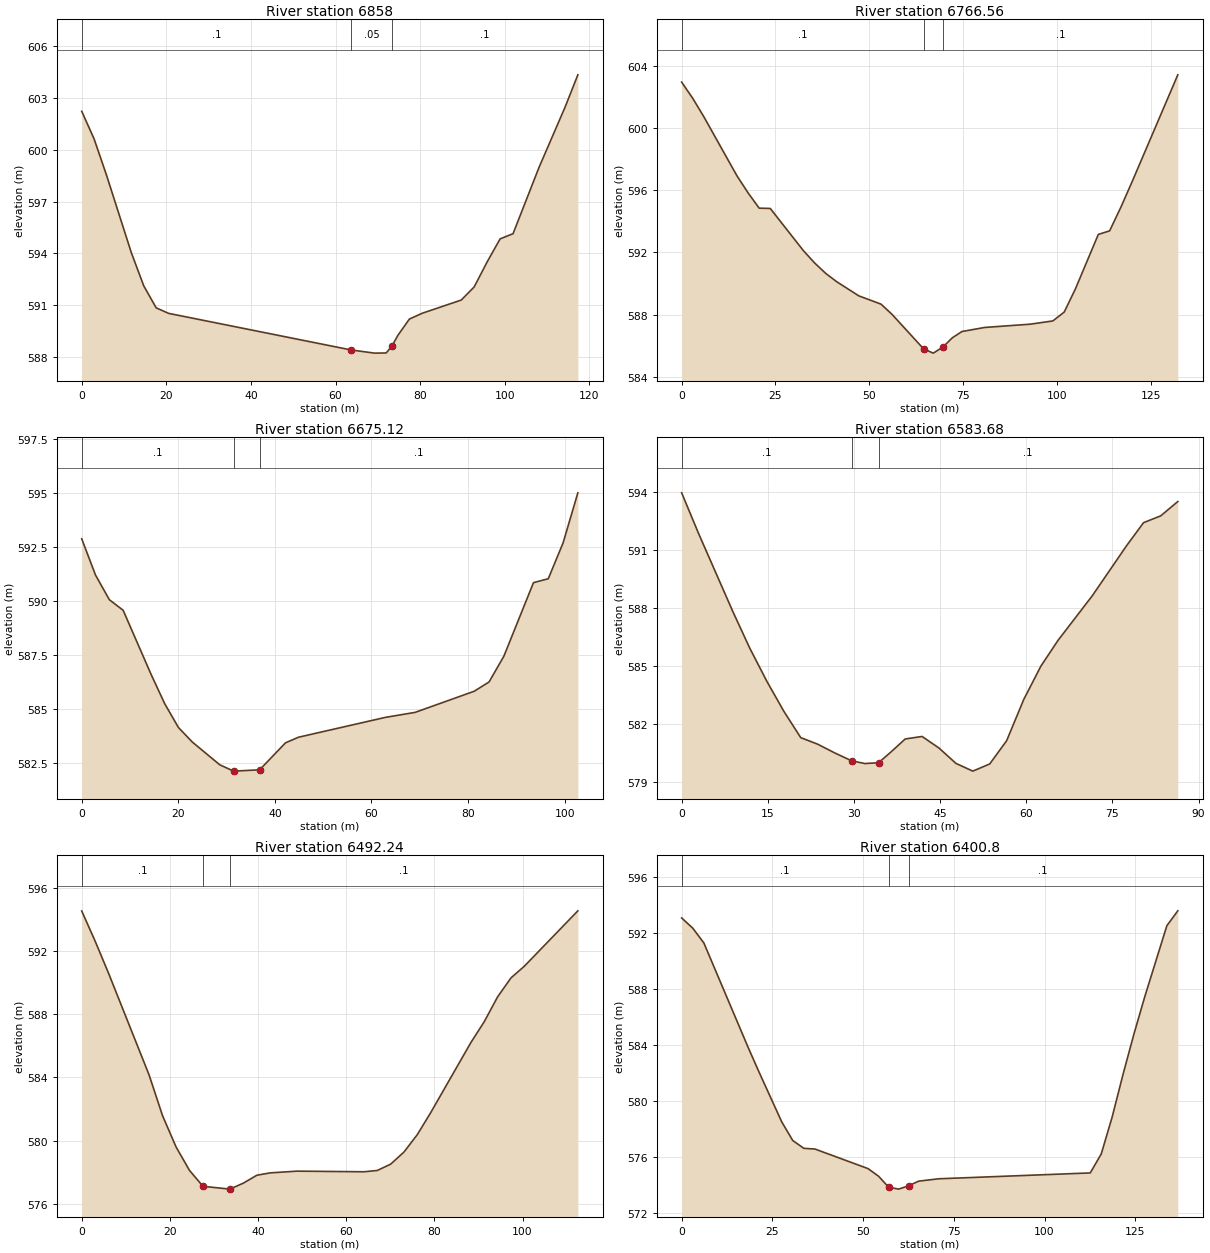
Type RM Length L Ch R = 1 ,6858    ,70.26,91.44,94.31
XS GIS Cut Line= 5
     604719.0143    4343324.2722     604689.2487    4343291.8607
     604676.3931    4343285.6557     604660.6975    4343274.6262
     604637.0448    4343242.5837
#Sta/Elev= 22
       0  602.22    2.93  600.62    5.87  598.52   11.73  594.04   14.67  592.12
    17.6  590.85   20.54  590.53   63.76  588.41   69.24  588.23   71.98  588.24
   73.36  588.65   74.72  589.25   77.46   590.2   80.53  590.54   89.72   591.3
   92.78  592.06   95.85  593.51   98.91  594.84  101.97  595.14   108.1  598.97
  114.23  602.44  117.29  604.33
#Mann= 3 , 0 , 0
       0      .1       0   63.76     .05       0   73.36      .1       0
Bank Sta=63.76,73.36
XS Rating Curve= 0 ,0
Exp/Cntr=0.3,0.1

Type RM Length L Ch R = 1 ,6766.56 ,91.5,91.44,86.51
XS GIS Cut Line= 4
     604750.1544    4343325.2661     604741.5665    4343263.9004
     604745.3281    4343251.7474     604736.2638    4343194.9586
#Sta/Elev= 29
       0  602.95    2.95  601.91     5.9  600.73   14.75  596.92    17.7  595.83
   20.65  594.85   23.61  594.83   32.46  592.11   35.41  591.33   38.36  590.66
   41.31  590.12   47.21  589.21   53.11  588.68   56.06  588.02   64.51  585.79
   67.05  585.53    69.6  585.92   72.14  586.52   74.69  586.92   80.74  587.18
   92.85  587.39    98.9   587.6  101.93  588.17  104.95  589.68  111.01  593.16
  114.03  593.39  117.06  594.93  120.09  596.59  132.19  603.42
#Mann= 3 , 0 , 0
       0      .1       0   64.51     .05       0    69.6      .1       0
Bank Sta=64.51,69.6
XS Rating Curve= 0 ,0
Exp/Cntr=0.3,0.1

Type RM Length L Ch R = 1 ,6675.12 ,90.99,91.44,93.71
XS GIS Cut Line= 4
     604837.5986    4343269.4108     604828.6089    4343239.2472
     604825.9235    4343223.3788     604812.1986    4343169.9272
#Sta/Elev= 22
       0   592.9    2.86  591.22    5.72  590.08    8.58  589.59   14.31  586.65
   17.17  585.27   20.03  584.16   22.89  583.49   28.61  582.43   31.47  582.14
   36.84   582.2    42.2  583.45   44.89  583.71    62.9  584.63   69.03  584.86
   81.29  585.84   84.36  586.27   87.42  587.46   93.56  590.87   96.62  591.05
   99.69  592.71  102.75  595.03
#Mann= 3 , 0 , 0
       0      .1       0   31.47     .05       0   36.84      .1       0
Bank Sta=31.47,36.84
XS Rating Curve= 0 ,0
Exp/Cntr=0.3,0.1

Type RM Length L Ch R = 1 ,6583.68 ,94.03,91.44,87.23
XS GIS Cut Line= 5
     604923.5212     4343245.801      604916.946    4343216.9295
     604915.6967    4343207.7038     604917.3662    4343190.1282
     604909.4263    4343161.3998
#Sta/Elev= 30
       0  593.95    2.96  591.84    8.88  587.84   11.84  585.94   14.81  584.23
   17.77  582.68   20.73  581.31   23.69  580.97   26.65  580.52   29.61  580.11
   31.94  579.97   32.34  579.98   34.27  580.01   36.29  580.53   36.59  580.61
   38.92  581.24   41.86  581.37   44.81  580.77   47.75  579.98   50.69  579.58
   53.63  579.95   56.58  581.15   59.56  583.28   62.54     585   65.52  586.33
   71.48  588.63   77.44  591.21   80.42  592.41    83.4  592.76   86.38   593.5
#Mann= 3 , 0 , 0
       0      .1       0   29.61     .05       0   34.27      .1       0
Bank Sta=29.61,34.27
XS Rating Curve= 0 ,0
Exp/Cntr=0.3,0.1

Type RM Length L Ch R = 1 ,6492.24 ,92.44,91.44,95.52
XS GIS Cut Line= 3
     605021.3787    4343206.1927     604996.6758    4343175.0853
     604940.9855    4343128.1512
#Sta/Elev= 25
       0  594.55    3.06  592.63    6.11  590.59   15.28  584.16   18.33  581.58
   21.39   579.6   24.44  578.11    27.5   577.1   33.61  576.92   36.67   577.3
   39.72   577.8   42.76  577.95   48.83  578.06      64  578.02   67.03   578.1
   70.07   578.5    73.1  579.27   76.14  580.38   79.17  581.77   88.28  586.21
   91.31  587.53   94.35  589.11   97.38  590.31  100.41  591.05  112.55  594.56
#Mann= 3 , 0 , 0
       0      .1       0    27.5     .05       0   33.61      .1       0
Bank Sta=27.5,33.61
XS Rating Curve= 0 ,0
Exp/Cntr=0.3,0.1

Type RM Length L Ch R = 1 ,6400.8  ,61.18,91.44,89.8
XS GIS Cut Line= 6
     605100.3973    4343175.7763     605086.6944    4343141.6984
     605076.0091     4343127.778     605064.4179    4343115.9596
     605054.1506    4343101.6139     605029.1474    4343060.3388
#Sta/Elev= 24
       0   593.1    3.06  592.37    6.12  591.31   18.36  583.81   21.43  582.01
   27.55  578.52   30.61  577.17   33.67  576.61   36.73  576.56   51.35  575.16
   54.28  574.61   57.04  573.83    59.8  573.69   62.56  573.93   65.31  574.26
   70.83  574.43   112.6  574.85  115.62   576.2  118.63  578.84  121.65  581.92
  124.67  584.82  127.68  587.51  133.71  592.54  136.73  593.61
#Mann= 3 , 0 , 0
       0      .1       0   57.04     .05       0   62.56      .1       0
Bank Sta=57.04,62.56
XS Rating Curve= 0 ,0
Exp/Cntr=0.3,0.1

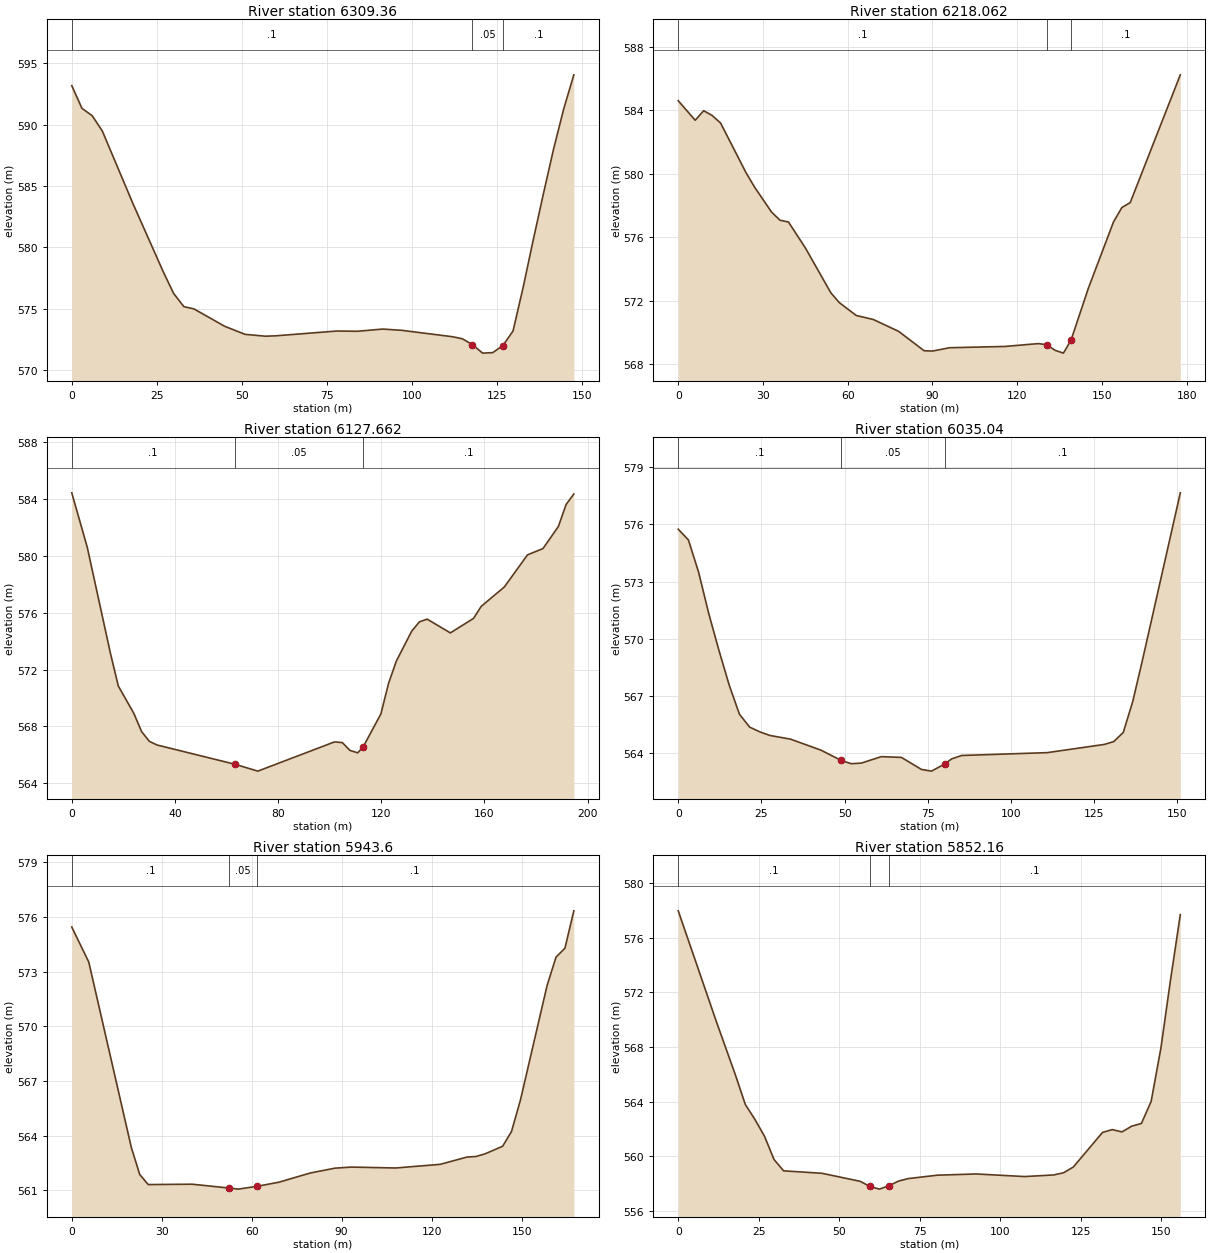
Type RM Length L Ch R = 1 ,6309.36 ,98.8,91.3,89.58
XS GIS Cut Line= 4
     605138.4867    4343173.4815      605124.596     4343090.799
     605116.9783    4343084.2149     605122.0617     4343030.838
#Sta/Elev= 30
       0  593.17    2.99  591.32    5.99  590.72    8.98  589.47   17.97  583.56
   26.95  577.96   29.94  576.23   32.94  575.16   35.93  574.97   44.91  573.56
    50.9   572.9   56.89  572.75   59.89  572.78   77.85  573.17   83.84  573.15
   91.39  573.33   96.89  573.23  111.78  572.71  114.76  572.54  117.74  572.06
  120.72  571.37   123.7  571.41  126.68  571.99  129.66  573.17  132.63  576.72
  135.61  580.61  138.59  584.36  141.57  587.99  144.55  591.27  147.53  594.05
#Mann= 3 , 0 , 0
       0      .1       0  117.74     .05       0  126.68      .1       0
Bank Sta=117.74,126.68
XS Rating Curve= 0 ,0
Exp/Cntr=0.3,0.1

Type RM Length L Ch R = 1 ,6218.062,94.77,90.4,89.97
XS GIS Cut Line= 4
     605254.1319    4343190.1282     605220.3975    4343100.1697
     605217.2061    4343080.8274     605193.0017    4343023.6405
#Sta/Elev= 30
       0  584.61       6  583.38    9.01  583.98   12.01  583.68   15.01   583.2
   24.02  580.07   27.02  579.17   33.03   577.6   36.03  577.08   39.03  576.97
   45.04  575.33   54.04  572.51   57.04  571.89   63.05  571.08   69.05  570.83
   78.06  570.08   87.07  568.86   90.07  568.84   96.08  569.05  115.68  569.13
  127.51  569.31  130.46  569.24  133.42  568.89  136.38  568.71  139.07  569.52
  145.25  572.81  154.12  576.97  157.08  577.88  160.04  578.19  177.78  586.24
#Mann= 3 , 0 , 0
       0      .1       0  130.46     .05       0  139.07      .1       0
Bank Sta=130.46,139.07
XS Rating Curve= 0 ,0
Exp/Cntr=0.3,0.1

Type RM Length L Ch R = 1 ,6127.662,71.28,92.62,96.83
XS GIS Cut Line= 4
     605339.9972    4343134.9949     605314.0216    4343070.9001
     605299.7716    4343048.2715     605252.1362     4342961.772
#Sta/Elev= 30
       0  584.45    6.01  580.61   15.03  573.11   18.04  570.84   24.06  568.91
   27.06  567.63   30.07  566.94   33.08  566.68   63.14  565.33   72.13  564.84
  101.88   566.9  104.88  566.85  107.87   566.3  110.86  566.13  112.95  566.54
  119.84  568.87  122.83  571.03  125.82  572.59  131.81  574.71   134.8  575.36
  137.79  575.55  146.77  574.58  155.75   575.6  158.74  576.45  167.72  577.82
  176.69  580.08  182.68  580.52  188.66  582.08  191.66  583.63  194.65  584.37
#Mann= 3 , 0 , 0
       0      .1       0   63.14     .05       0  112.95      .1       0
Bank Sta=63.14,112.95
XS Rating Curve= 0 ,0
Exp/Cntr=0.3,0.1

Type RM Length L Ch R = 1 ,6035.04 ,101.98,91.44,62.72
XS GIS Cut Line= 6
      605369.876    4343111.9234     605368.7904    4343065.9789
     605378.2216    4343037.3608     605383.2575    4343026.3736
     605387.4436    4343004.0662     605377.2528    4342965.4014
#Sta/Elev= 29
       0  575.75    3.06  575.19    6.13  573.49    9.19  571.31   12.26  569.38
   15.32  567.57   18.38  566.05   21.45  565.37   24.51  565.12   27.57  564.93
    33.7  564.74   42.89  564.16   48.97  563.62   51.98  563.45      55  563.48
   61.02  563.82   67.05  563.78   73.08  563.15   76.09  563.06   80.23  563.45
   82.13   563.7   85.15  563.88  110.87  564.03  128.01  564.46  130.87  564.61
  133.72  565.09  136.58  566.72  139.43  568.84  150.86  577.66
#Mann= 3 , 0 , 0
       0      .1       0   48.97     .05       0   80.23      .1       0
Bank Sta=48.97,80.23
XS Rating Curve= 0 ,0
Exp/Cntr=0.3,0.1

Type RM Length L Ch R = 1 ,5943.6  ,87.77,91.44,101.15
XS GIS Cut Line= 6
     605490.6582    4343099.8565     605477.8941    4343068.3308
      605460.982    4343046.4687     605457.6818    4343037.1304
     605442.1335    4343022.1034     605420.7757    4342950.9998
#Sta/Elev= 25
       0  575.44    5.67  573.52   19.84  563.36   22.67  561.86   25.51  561.31
   40.15  561.33   52.44  561.12   55.51  561.06   61.65  561.21   69.08  561.44
   79.66  561.95   87.77  562.21   93.18  562.27  108.03  562.22  122.88  562.42
  131.79  562.82  134.75  562.85  137.72  562.99  143.66  563.41  146.63  564.22
   149.6  565.94  158.51  572.24  161.48  573.79  164.45  574.28  167.42  576.33
#Mann= 3 , 0 , 0
       0      .1       0   52.44     .05       0   61.65      .1       0
Bank Sta=52.44,61.65
XS Rating Curve= 0 ,0
Exp/Cntr=0.3,0.1

Type RM Length L Ch R = 1 ,5852.16 ,93.03,91.44,85.99
XS GIS Cut Line= 3
     605572.4606    4343079.3455     605544.6434    4343010.3591
     605523.3008    4342931.6567
#Sta/Elev= 30
       0  577.98    11.9  569.83   17.85   565.9   20.83   563.8    23.8  562.71
   26.78  561.48   29.75  559.77   32.73  558.94   44.63  558.76   56.53  558.17
   59.51   557.8   62.48   557.6   65.46  557.85   68.43  558.19   71.41  558.37
   80.42  558.62    92.5  558.71  107.61  558.52  116.67  558.64  119.69   558.8
  122.71  559.22  131.77  561.75  134.79  561.96  137.81  561.79  140.83  562.21
  143.85  562.41  146.87  564.02  149.89  567.91  152.91  572.95  155.93   577.7
#Mann= 3 , 0 , 0
       0      .1       0   59.51     .05       0   65.46      .1       0
Bank Sta=59.51,65.46
XS Rating Curve= 0 ,0
Exp/Cntr=0.3,0.1

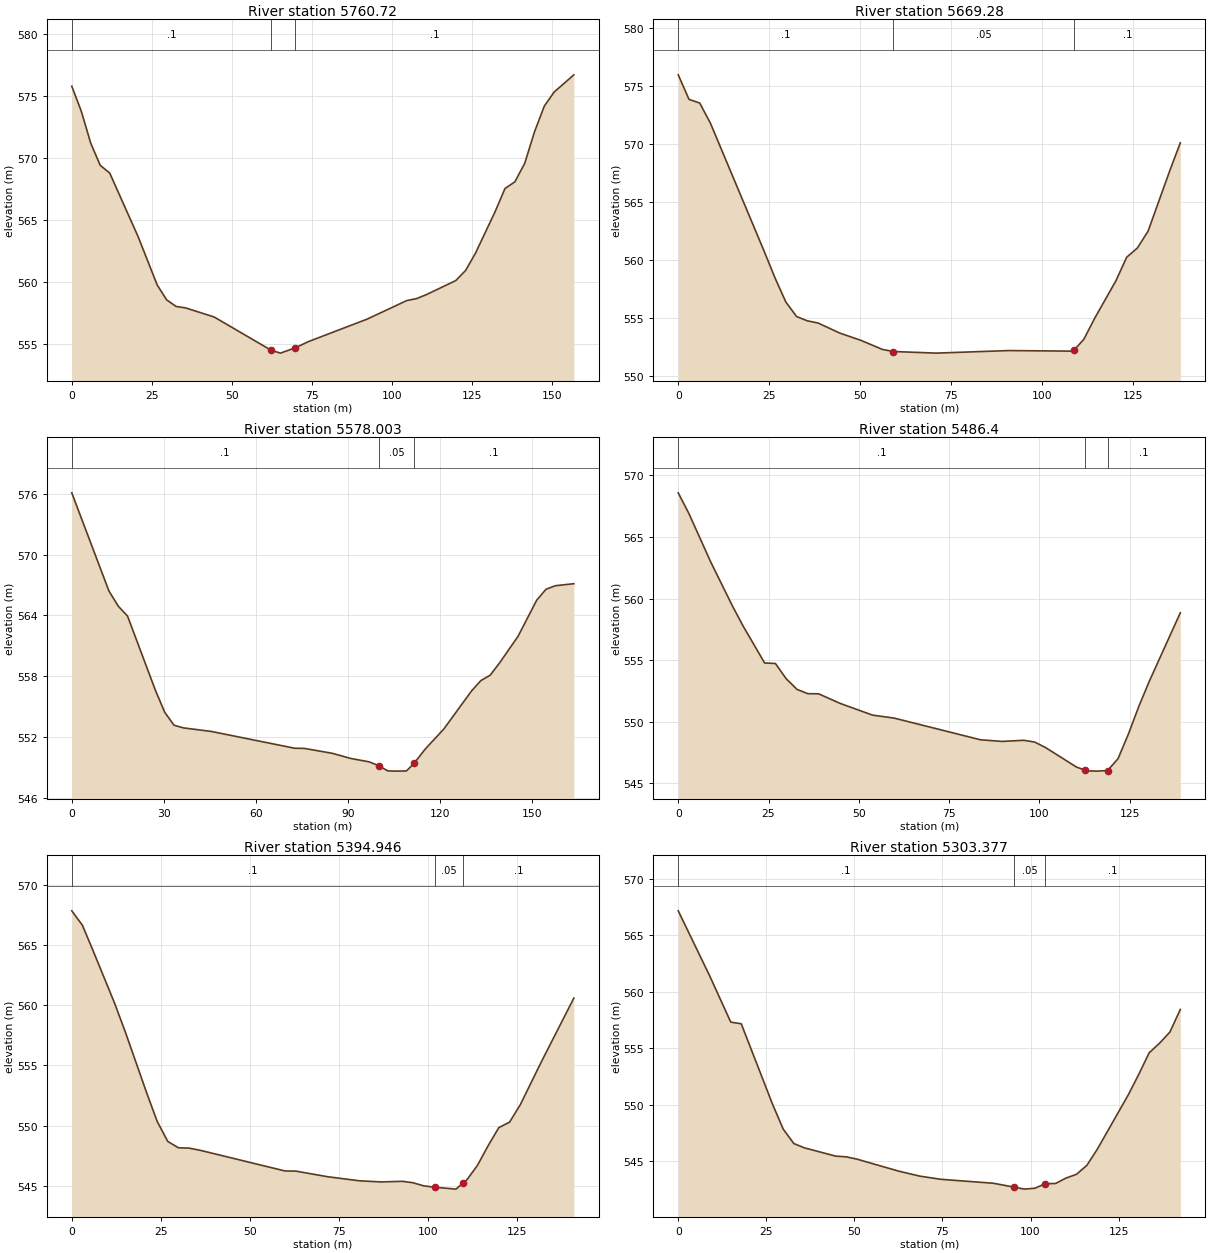
Type RM Length L Ch R = 1 ,5760.72 ,76.55,91.44,89.44
XS GIS Cut Line= 4
     605667.5328    4343054.3764     605639.4452     4343002.141
     605628.4142    4342988.3176      605591.465    4342917.4542
#Sta/Elev= 30
       0  575.78    2.97  573.77    5.93  571.18     8.9  569.39   11.86  568.77
   20.76  563.62   26.69  559.74   29.65  558.53   32.62     558   35.58  557.88
   44.48  557.15   62.26  554.47    65.2  554.23   69.87  554.66   74.05  555.17
   92.36  556.98  104.66  558.47  107.73  558.63   110.8  558.95  120.03  560.09
   123.1  560.91  126.17   562.3  132.32  565.66  135.39  567.52  138.47  568.06
  141.54  569.54  144.62   572.1  147.69  574.18  150.76  575.31  156.91   576.7
#Mann= 3 , 0 , 0
       0      .1       0   62.26     .05       0   69.87      .1       0
Bank Sta=62.26,69.87
XS Rating Curve= 0 ,0
Exp/Cntr=0.3,0.1

Type RM Length L Ch R = 1 ,5669.28 ,87.2,91.28,91.64
XS GIS Cut Line= 4
     605713.1485      4343046.92     605708.7829    4342979.0542
     605703.7743    4342956.8098     605697.7653    4342910.0366
#Sta/Elev= 26
       0  575.95    2.96  573.84    5.91  573.52    8.87  571.77   23.65  560.74
   26.61  558.46   29.57   556.4   32.52  555.15   35.48  554.78   38.44  554.59
   44.35  553.73   50.27  553.09   56.18  552.31   59.14  552.14   70.86     552
   90.81  552.22  108.49  552.17  108.82  552.28  111.44  553.18  114.39  554.97
  120.28  558.23  123.23  560.25  126.18  561.05  129.12   562.5  135.02  567.65
  137.97   570.1
#Mann= 3 , 0 , 0
       0      .1       0   59.14     .05       0  108.82      .1       0
Bank Sta=59.14,108.82
XS Rating Curve= 0 ,0
Exp/Cntr=0.3,0.1

Type RM Length L Ch R = 1 ,5578.003,93.84,91.6,90.9
XS GIS Cut Line= 2
     605795.0498    4343045.1502     605791.4022    4342881.6472
#Sta/Elev= 30
       0  576.08   12.11  566.41   15.14  564.92   18.17  563.94   27.26  556.62
   30.29  554.46   33.31  553.19   36.34  552.93   45.43  552.58   72.69  550.92
   75.71  550.91    84.8  550.43   90.86  549.92   96.91  549.58   99.94  549.21
  102.97  548.69     106  548.67  109.03  548.69  111.56  549.46  115.09  550.83
  121.14   552.8  130.23  556.57  133.26  557.59  136.29  558.12  139.31  559.31
  145.37  561.95  151.43   565.5  154.46  566.58  157.49  566.93  163.54  567.13
#Mann= 3 , 0 , 0
       0      .1       0   99.94     .05       0  111.56      .1       0
Bank Sta=99.94,111.56
XS Rating Curve= 0 ,0
Exp/Cntr=0.3,0.1

Type RM Length L Ch R = 1 ,5486.4  ,93.26,91.45,89.62
XS GIS Cut Line= 3
     605889.0351    4343045.9851      605886.624    4342944.3314
     605878.3206    4342907.9023
#Sta/Elev= 29
       0  568.57    2.99  566.87    8.97  562.98   14.95  559.43   17.94  557.78
   23.93  554.77   26.92  554.73   29.91  553.49    32.9  552.63   35.89  552.28
   38.88  552.27   44.86  551.49   53.83  550.54   59.81   550.3   83.74  548.54
   89.72  548.41    95.7   548.5   98.69  548.36  101.68  547.92   110.3  546.33
  112.54  546.09  113.18  546.02  116.05     546  118.93  546.05   121.8  547.01
  124.68  549.01  127.55  551.24  130.42  553.26  139.05  558.84
#Mann= 3 , 0 , 0
       0      .1       0  112.54     .05       0  118.93      .1       0
Bank Sta=112.54,118.93
XS Rating Curve= 0 ,0
Exp/Cntr=0.3,0.1

Type RM Length L Ch R = 1 ,5394.946,83.23,91.57,92.33
XS GIS Cut Line= 3
     605993.6363    4343038.1693      605977.228    4342946.8009
     605960.2067    4342901.7556
#Sta/Elev= 30
       0  567.86    2.99  566.66    5.99  564.54   11.98  560.21   14.97  557.84
   20.96  552.78   23.96  550.36   26.95  548.68   29.95  548.15   32.94  548.12
   35.93  547.95   59.89  546.22   62.88  546.21   71.87  545.74   80.85   545.4
   86.84  545.31   92.83  545.36   95.84  545.24   98.85  544.98  101.86  544.87
  107.88  544.71  109.95  545.23  110.89  545.46   113.9  546.68  116.91  548.32
  119.92  549.83  122.93  550.28  125.94  551.73  131.96  555.36  140.98   560.6
#Mann= 3 , 0 , 0
       0      .1       0  101.86     .05       0  109.95      .1       0
Bank Sta=101.86,109.95
XS Rating Curve= 0 ,0
Exp/Cntr=0.3,0.1

Type RM Length L Ch R = 1 ,5303.377,83.67,91.3,92.42
XS GIS Cut Line= 3
     606061.8965    4343045.8639     606062.0994    4342959.3738
     606054.3985    4342903.8722
#Sta/Elev= 30
       0  567.18    8.95   561.4   14.91  557.32   17.89  557.17   26.84  549.99
   29.82  547.83   32.81  546.56   35.79  546.18   44.74  545.44   47.72  545.38
    50.7  545.18   62.63  544.11    68.6  543.67   74.56  543.39   89.44  543.04
   95.34   542.7   98.29  542.52  101.24   542.6  104.19     543  107.13  543.02
  110.08   543.5  113.03  543.83  115.98  544.62  118.93  546.04  127.78  550.89
  130.73  552.69  133.68   554.6  136.63  555.45  139.57  556.44  142.52  558.44
#Mann= 3 , 0 , 0
       0      .1       0   95.34     .05       0  104.19      .1       0
Bank Sta=95.34,104.19
XS Rating Curve= 0 ,0
Exp/Cntr=0.3,0.1

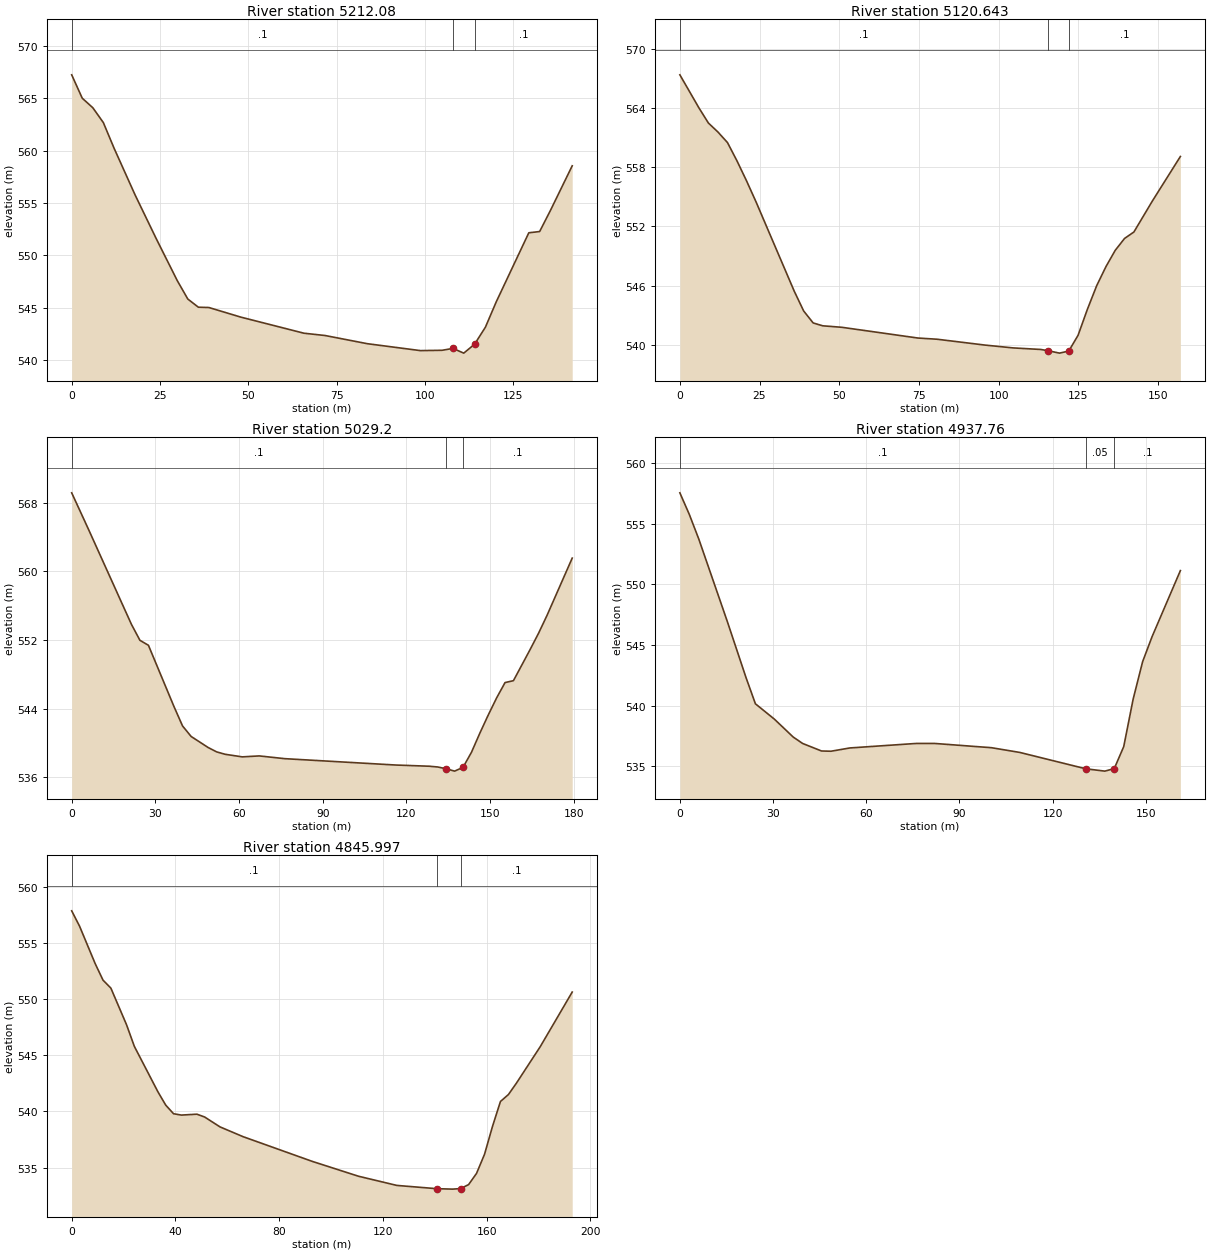
Type RM Length L Ch R = 1 ,5212.08 ,91.02,91.44,91.27
XS GIS Cut Line= 3
     606127.9528    4343056.8017      606147.689     4342963.204
     606155.3576    4342917.7859
#Sta/Elev= 26
       0  567.22    2.99  564.99    5.98  564.08    8.97  562.66   11.96  560.25
   17.94  555.77   23.91  551.61   29.89  547.59   32.88  545.83   35.87  545.05
   38.86  545.02   47.83  544.11   65.76  542.57   71.74  542.35    83.7  541.57
   98.73  540.91  104.87  540.94  107.94  541.12  111.01  540.67  114.08  541.52
  117.15  543.15  120.22  545.57  129.43  552.15   132.5  552.27  135.58   554.3
  141.72  558.54
#Mann= 3 , 0 , 0
       0      .1       0  107.94     .05       0  114.08      .1       0
Bank Sta=107.94,114.08
XS Rating Curve= 0 ,0
Exp/Cntr=0.3,0.1

Type RM Length L Ch R = 1 ,5120.643,86.7,91.44,92.04
XS GIS Cut Line= 3
     606209.1801    4343082.5986     606236.7958    4342984.8255
      606243.576    4342929.8015
#Sta/Elev= 30
       0  567.37    5.98  564.02    8.96  562.48   11.95  561.57   14.94   560.5
   17.93  558.64   20.92  556.62   23.91  554.48   35.86  545.45   38.85  543.42
   41.83  542.21   44.82  541.92    50.8  541.77    74.7  540.68   80.68  540.56
   95.62  539.97  104.52  539.68  113.27  539.52   115.6  539.39  119.11  539.15
  122.02  539.36  124.94  540.96  127.86  543.59  130.78  545.99   133.7  547.93
  136.61  549.58  139.53  550.78  142.45  551.43  148.28  554.59  157.04  559.09
#Mann= 3 , 0 , 0
       0      .1       0   115.6     .05       0  122.02      .1       0
Bank Sta=115.6,122.02
XS Rating Curve= 0 ,0
Exp/Cntr=0.3,0.1

Type RM Length L Ch R = 1 ,5029.2  ,89.19,91.44,91.94
XS GIS Cut Line= 3
     606278.6568    4343114.8122      606322.838     4343004.079
     606339.9957    4342946.3663
#Sta/Elev= 30
       0  569.14    6.11  564.83    21.4  553.84   24.46  551.97   27.51  551.39
   36.68  544.25   39.74     542    42.8  540.78   48.91  539.49   51.97  538.98
   55.03   538.7   61.14   538.4   67.25  538.51   76.42  538.19  116.16  537.45
  128.25  537.31  131.26  537.22  134.27  537.01  137.28  536.74  140.29  537.18
  143.31  538.93  146.32  541.16  149.33  543.27  152.34  545.27  155.35  547.05
  158.36  547.27  164.38  550.92  167.39  552.81   170.4  554.87  179.43  561.54
#Mann= 3 , 0 , 0
       0      .1       0  134.27     .05       0  140.29      .1       0
Bank Sta=134.27,140.29
XS Rating Curve= 0 ,0
Exp/Cntr=0.3,0.1

Type RM Length L Ch R = 1 ,4937.76 ,89.54,91.76,92.06
XS GIS Cut Line= 2
     606358.7928    4343136.9575     606425.1319    4342990.1371
#Sta/Elev= 24
       0  557.54    3.04  555.76    6.08  553.74    15.2  546.99   21.28  542.32
   24.32  540.15    30.4  538.89   36.48  537.41   39.52  536.88    45.6  536.26
   48.64  536.24   54.72  536.51      76  536.88   82.08  536.88  100.32  536.53
  109.43  536.14  130.71  534.79  136.79   534.6  139.83  534.81  142.87  536.62
  145.91  540.54  148.95  543.62  151.99  545.68  161.11  551.13
#Mann= 3 , 0 , 0
       0      .1       0  130.71     .05       0  139.83      .1       0
Bank Sta=130.71,139.83
XS Rating Curve= 0 ,0
Exp/Cntr=0.3,0.1

Type RM Length L Ch R = 1 ,4845.997,95.14,91.09,90.54
XS GIS Cut Line= 4
     606417.5399    4343173.8801     606452.0207    4343144.4718
     606486.5908    4343072.2791     606519.4047    4343013.1454
#Sta/Elev= 30
       0  557.86    3.02   556.5    9.06  553.16   12.08  551.69   15.11  550.98
   21.15  547.72   24.17  545.79   33.23  541.76   36.25  540.57   39.28   539.8
    42.3  539.68   48.28  539.76   51.25  539.51   57.18  538.63   66.07  537.76
   92.75  535.56  110.54  534.24  125.36  533.42  140.73  533.13  146.88  533.09
  149.95  533.14  153.03  533.49   156.1  534.49  159.18  536.19  162.25  538.67
  165.32  540.89   168.4  541.51  171.47  542.52  180.69  545.78  192.99  550.63
#Mann= 3 , 0 , 0
       0      .1       0  140.73     .05       0  149.95      .1       0
Bank Sta=140.73,149.95
XS Rating Curve= 0 ,0
Exp/Cntr=0.3,0.1