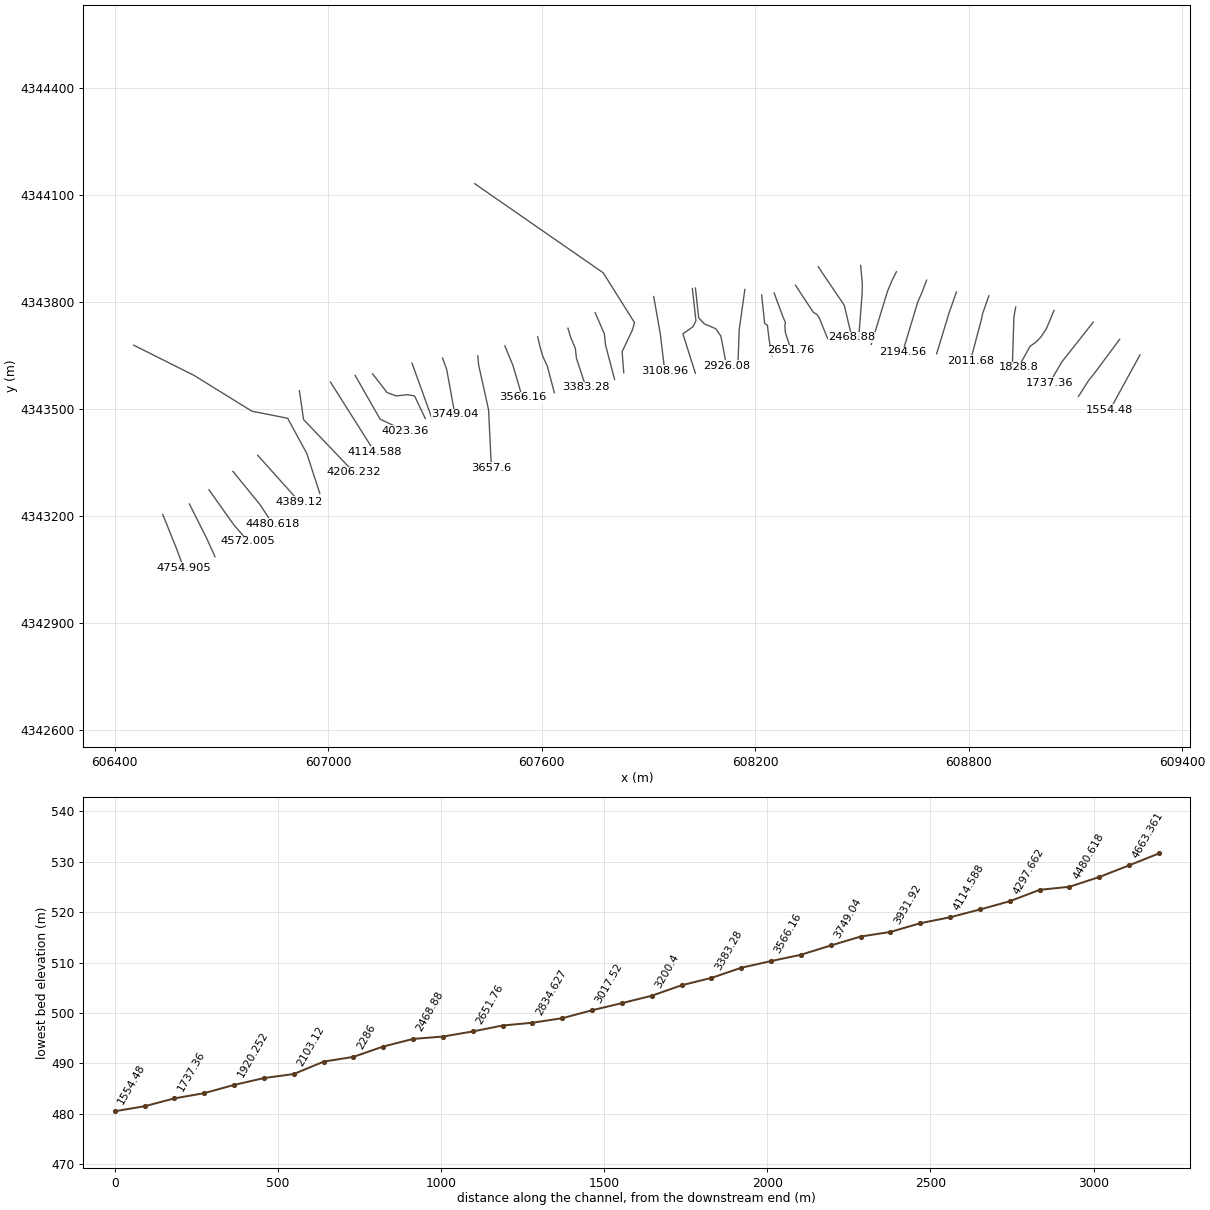
HEC-RAS study CheatRiver.prj: CheatRiver

--- CheatRiver.g01 (geometry) --- (continued)

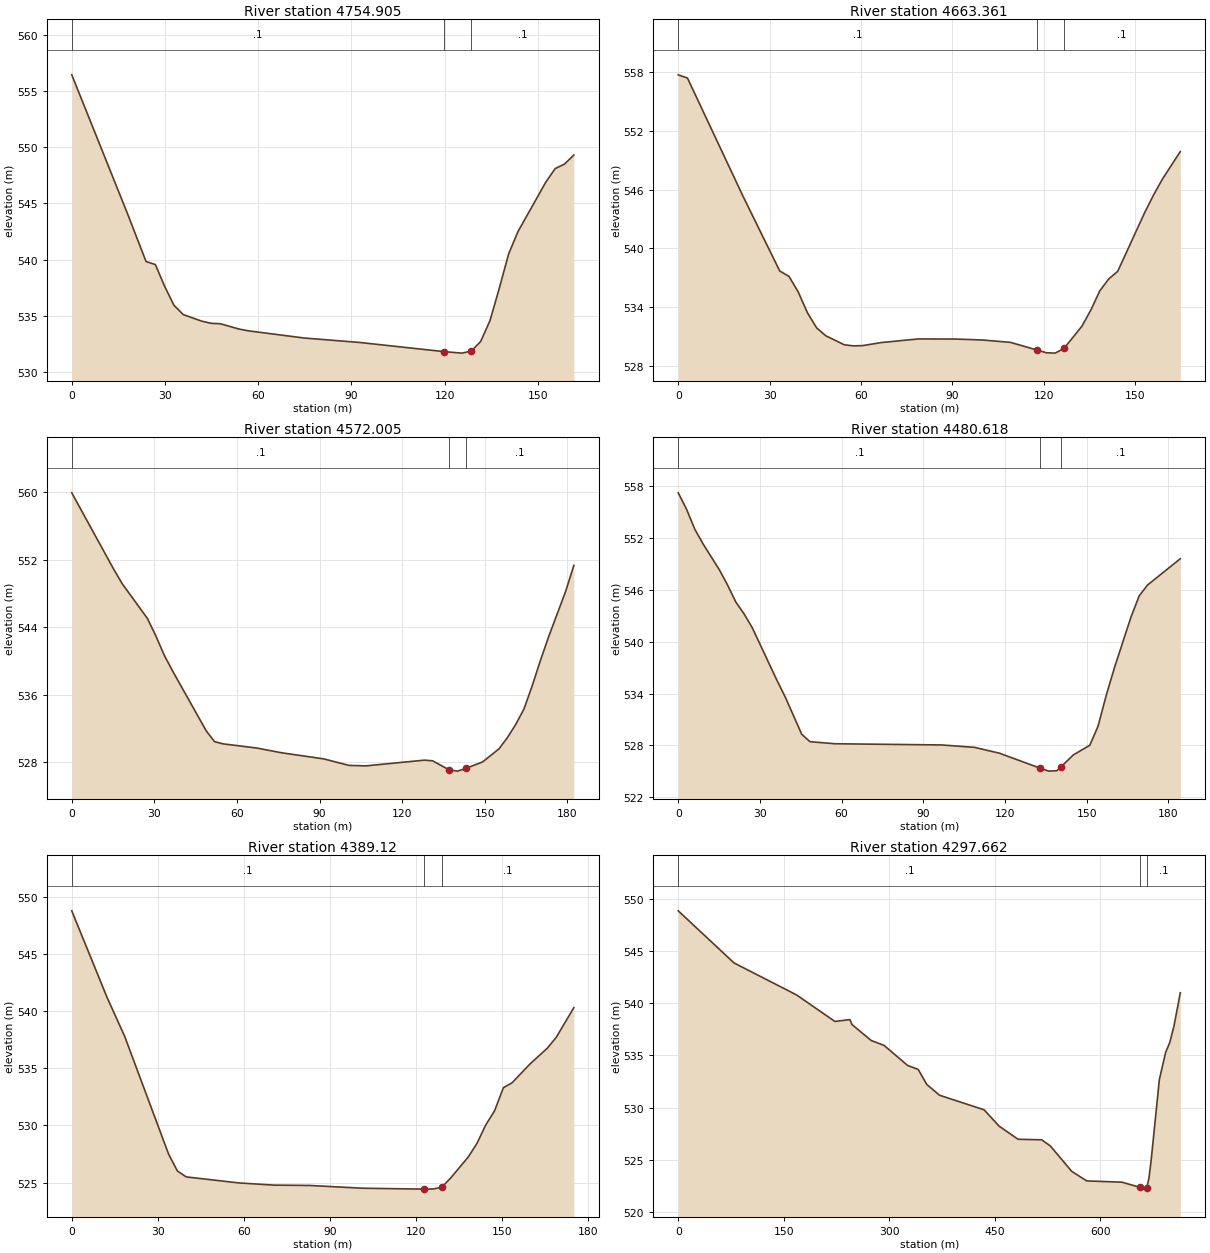
Type RM Length L Ch R = 1 ,4754.905,89.09,91.54,91.81
XS GIS Cut Line= 3
     606534.9063    4343204.1534     606574.0369    4343107.1699
     606593.8189     4343053.759
#Sta/Elev= 26
       0  556.47   17.93  544.09    23.9  539.82   26.89  539.55   29.88  537.61
   32.87  535.92   35.86  535.09   41.83   534.5   44.82  534.31   47.81  534.27
   53.78   533.8   56.77  533.64    74.7     533   92.63   532.6  119.91  531.78
  125.56  531.65  128.56  531.83  131.56  532.69  134.56  534.55  137.55  537.43
  140.55  540.49  143.55  542.48  152.54  546.91  155.54  548.11  158.54  548.51
  161.54  549.32
#Mann= 3 , 0 , 0
       0      .1       0  119.91     .05       0  128.56      .1       0
Bank Sta=119.91,128.56
XS Rating Curve= 0 ,0
Exp/Cntr=0.3,0.1

Type RM Length L Ch R = 1 ,4663.361,83.51,91.36,92.44
XS GIS Cut Line= 3
     606609.6939     4343233.676     606658.7056    4343136.2498
      606681.793    4343085.5091
#Sta/Elev= 30
       0  557.74    3.03  557.41   21.21  545.36   33.32  537.68   36.35  537.13
   39.38  535.54   42.41  533.41   45.44  531.86   48.47  531.05   54.53  530.13
   57.56  530.02   60.59  530.05   66.65  530.36   78.77  530.73   90.88  530.72
   99.97  530.62  109.06  530.38  117.86  529.59   120.8  529.32  123.73  529.28
  126.66  529.77  132.53  532.04  135.47   533.7   138.4  535.66  141.33  536.87
  144.27  537.65  153.07  543.62     156  545.43  158.94  547.08  164.81  549.89
#Mann= 3 , 0 , 0
       0      .1       0  117.86     .05       0  126.66      .1       0
Bank Sta=117.86,126.66
XS Rating Curve= 0 ,0
Exp/Cntr=0.3,0.1

Type RM Length L Ch R = 1 ,4572.005,92.24,91.39,90.88
XS GIS Cut Line= 3
     606664.5951    4343273.3636      606735.339    4343173.9205
     606775.0588    4343128.5039
#Sta/Elev= 30
       0  559.93   15.25  550.87   18.31  549.17   27.46  545.06   30.51  543.01
   33.56  540.72   36.61  538.84   48.82  531.75   51.87  530.46   54.92   530.2
   67.12  529.71   76.27  529.14   91.53  528.42  100.68  527.65  106.78  527.59
  128.07  528.27  131.09  528.19  137.12  527.11  140.14  526.97  143.16   527.3
  149.19  528.05  155.22  529.62  158.24  530.94  161.26   532.5  164.27  534.34
  167.29  537.12  170.31  540.16  173.32  542.98  179.36  548.23  182.37  551.34
#Mann= 3 , 0 , 0
       0      .1       0  137.12     .05       0  143.16      .1       0
Bank Sta=137.12,143.16
XS Rating Curve= 0 ,0
Exp/Cntr=0.3,0.1

Type RM Length L Ch R = 1 ,4480.618,87.14,91.5,92.1
XS GIS Cut Line= 3
     606732.2227     4343324.931     606808.6245    4343231.1985
     606843.3479     4343178.087
#Sta/Elev= 30
       0  557.25    3.02  555.38    6.05  553.06    9.07  551.36   15.12  548.33
   18.14  546.56   21.16   544.6   24.19  543.23   27.21  541.62   36.28  535.52
    39.3  533.61   45.35   529.3   48.37  528.44   57.44   528.2   96.74  528.06
  108.83  527.78   117.9  527.11  133.01  525.36  136.03  525.03  139.06  525.08
  140.44  525.48   145.1  526.91  151.14  528.02  154.16  530.22  157.19  533.82
  160.21  537.02  166.25  542.85  169.27  545.31  172.29  546.56  184.38  549.62
#Mann= 3 , 0 , 0
       0      .1       0  133.01     .05       0  140.44      .1       0
Bank Sta=133.01,140.44
XS Rating Curve= 0 ,0
Exp/Cntr=0.3,0.1

Type RM Length L Ch R = 1 ,4389.12 ,98.49,91.46,89.56
XS GIS Cut Line= 2
     606801.8905    4343370.0112     606918.9038    4343239.7001
#Sta/Elev= 24
       0  548.79   12.29  541.22   18.44  537.81    33.8  527.47   36.87     526
   39.94  525.49   58.38  524.96   70.67  524.77   82.96  524.74   101.4   524.5
   122.9  524.42  125.98  524.43  129.05  524.58  132.12  525.38  138.27  527.22
  141.34  528.42  144.41  530.04  147.48  531.27  150.56   533.3  153.63  533.74
  159.77  535.36  165.92  536.77  168.99  537.71  175.14  540.31
#Mann= 3 , 0 , 0
       0      .1       0   122.9     .05       0  129.05      .1       0
Bank Sta=122.9,129.05
XS Rating Curve= 0 ,0
Exp/Cntr=0.3,0.1

Type RM Length L Ch R = 1 ,4297.662,71.34,91.43,94.37
XS GIS Cut Line= 6
     606453.3072    4343679.0765     606622.6409    4343594.4097
     606785.3599    4343493.8678     606885.9018     4343474.024
     606939.8321    4343374.9489     606976.3013    4343263.0184
#Sta/Elev= 30
       0   548.9   79.39  543.89  167.95  540.83  222.72  538.27  243.97  538.45
  247.01  537.97  274.33  536.44  292.55  535.97  325.95  534.05  341.13  533.66
  353.27  532.22  371.49  531.18  434.85  529.78  455.95  528.22  483.08  526.95
  516.61   526.9  528.81  526.32  559.29  523.87  580.64  522.95  630.54  522.83
  657.08  522.32  663.04  522.16  666.02  522.28     669  523.17  671.98  524.76
   683.9  532.69  692.84   535.3  698.79  536.26  704.75  537.85  713.69  541.03
#Mann= 3 , 0 , 0
       0      .1       0  657.08     .05       0  666.02      .1       0
Bank Sta=657.08,666.02
XS Rating Curve= 0 ,0
Exp/Cntr=0.3,0.1

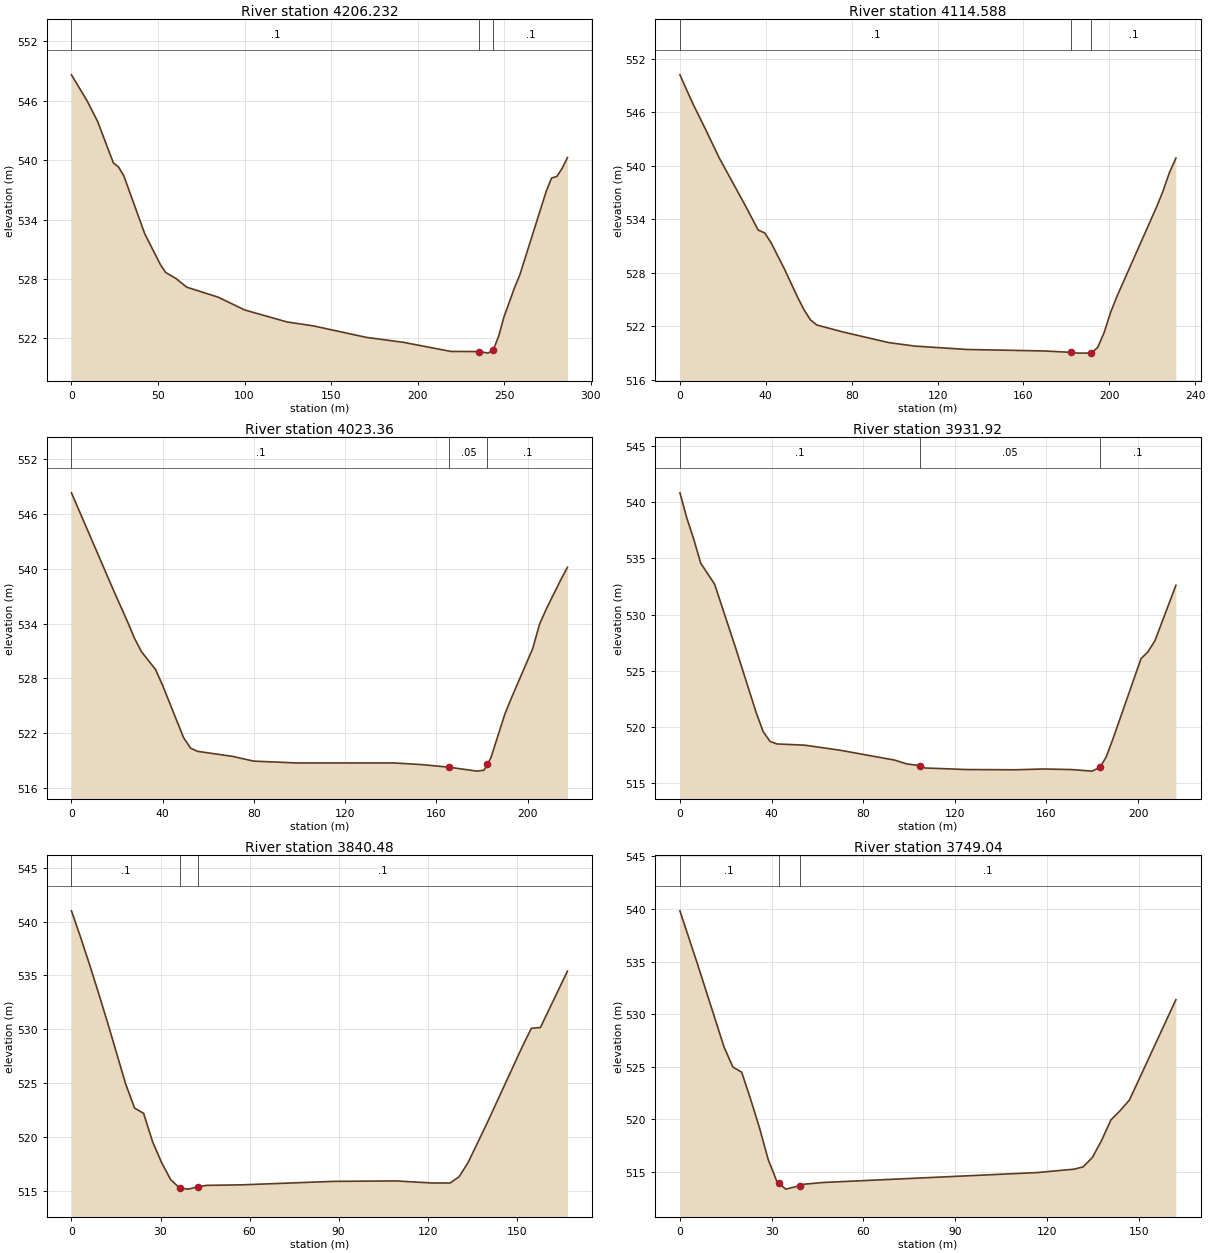
Type RM Length L Ch R = 1 ,4206.232,99.64,91.64,90.92
XS GIS Cut Line= 3
     606918.9087    4343551.1502     606930.6714    4343470.2865
     607072.3673    4343322.2852
#Sta/Elev= 30
       0  548.62    9.08  545.98   15.13  543.91   24.21  539.73   27.24   539.3
   30.26  538.42   42.37  532.56   51.45  529.44   54.48  528.66   60.53  528.04
   66.58  527.18   84.77  526.17  100.06  524.88  124.53  523.67  139.82  523.27
   170.4  522.11  191.81  521.61  219.33  520.69  235.67  520.68  240.74  520.52
   243.8  520.86  246.85  522.23  249.91  524.16  256.03  527.13  259.09  528.42
  274.38  536.88  277.44   538.2  280.49  538.36  283.55  539.18  286.61  540.27
#Mann= 3 , 0 , 0
       0      .1       0  235.67     .05       0   243.8      .1       0
Bank Sta=235.67,243.8
XS Rating Curve= 0 ,0
Exp/Cntr=0.3,0.1

Type RM Length L Ch R = 1 ,4114.588,62.65,91.23,94.73
XS GIS Cut Line= 2
     607006.2213    4343575.6242     607129.9143    4343380.4936
#Sta/Elev= 30
       0   550.2    6.08  546.94   12.16  543.98   18.24  540.91    30.4  535.56
   36.48  532.78   39.52  532.46   42.56  531.32   48.64  528.44   54.72   525.3
   57.76  523.86    60.8  522.71   63.84  522.13      76  521.35   97.28  520.16
  109.44  519.77  133.76  519.39  170.23  519.22  182.39  519.06  185.43  518.98
  191.51  518.99  194.55   519.6  195.41  520.07  197.59  521.28  200.63  523.56
  203.67   525.4  221.91  535.31  224.95  537.11  227.99  539.22  231.03  540.86
#Mann= 3 , 0 , 0
       0      .1       0  182.39     .05       0  191.51      .1       0
Bank Sta=182.39,191.51
XS Rating Curve= 0 ,0
Exp/Cntr=0.3,0.1

Type RM Length L Ch R = 1 ,4023.36 ,72.94,91.44,98.53
XS GIS Cut Line= 3
     607075.6746    4343594.1451     607145.7793    4343471.4937
     607214.7727    4343439.0265
#Sta/Elev= 27
       0  548.34   18.43  537.65   24.57  534.21   27.64  532.38   30.71   530.9
   36.85  528.96   39.92  527.25   49.14  521.49   52.21  520.33   55.28  519.97
   70.64  519.42   79.85   518.9   98.28   518.7  141.27   518.7  153.47  518.52
  165.67  518.23  177.87   517.8  180.92   517.9  182.44  518.53  183.97  519.28
  190.07  524.06  193.12  525.93  202.27  531.24  205.32  533.95  208.37  535.66
  214.47  538.73  217.52  540.17
#Mann= 3 , 0 , 0
       0      .1       0  165.67     .05       0  182.44      .1       0
Bank Sta=165.67,182.44
XS Rating Curve= 0 ,0
Exp/Cntr=0.3,0.1

Type RM Length L Ch R = 1 ,3931.92 ,95.11,91.44,41.2
XS GIS Cut Line= 6
     607124.5256      4343598.74     607165.4085    4343546.1501
     607190.8086     4343536.625      607221.769    4343540.2681
      607242.667     4343536.625     607272.6926    4343473.3273
#Sta/Elev= 28
       0  540.84    3.03  538.59    6.06   536.7    9.08  534.58   15.14  532.71
   24.22   527.1   33.31  521.27   36.33  519.59   39.36  518.71   42.39  518.49
    54.5  518.38   69.63  517.94   93.74  517.05   99.04  516.71  104.88  516.56
     107  516.35  125.22  516.21  146.43  516.19  158.61  516.26   170.8  516.21
  179.94  516.07  183.28   516.4  186.03  517.31  189.07  518.97  201.26  526.08
   204.3  526.69  207.35  527.68  216.49  532.61
#Mann= 3 , 0 , 0
       0      .1       0  104.88     .05       0  183.28      .1       0
Bank Sta=104.88,183.28
XS Rating Curve= 0 ,0
Exp/Cntr=0.3,0.1

Type RM Length L Ch R = 1 ,3840.48 ,91.5,91.44,81.17
XS GIS Cut Line= 2
     607235.4912    4343628.5974     607292.2586    4343471.4858
#Sta/Elev= 27
       0     541    3.04  538.57    6.07  536.03    9.11  533.37   12.15  530.63
   18.22  524.95   21.26  522.68    24.3  522.19   27.34  519.54   30.37  517.61
   33.41  516.04   36.45  515.24   39.49  515.15   42.52  515.37   45.56   515.5
   57.71  515.55   88.08  515.87  109.34  515.91  121.49  515.72  127.57  515.72
   130.6  516.31  133.64  517.65  139.72  521.13  151.87   528.4   154.9  530.09
  157.94  530.16  167.05   535.4
#Mann= 3 , 0 , 0
       0      .1       0   36.45     .05       0   42.52      .1       0
Bank Sta=36.45,42.52
XS Rating Curve= 0 ,0
Exp/Cntr=0.3,0.1

Type RM Length L Ch R = 1 ,3749.04 ,93.2,91.44,91.9
XS GIS Cut Line= 3
     607321.1856    4343643.1209     607333.0169    4343610.5742
     607355.8262    4343485.1192
#Sta/Elev= 23
       0  539.82    5.77  534.74   14.43  526.88   17.32  524.98    20.2  524.49
   23.09  521.94   25.97  519.25   28.86  516.19   31.74  514.08   32.24  513.96
   34.63  513.38   39.24  513.71    40.7  513.85   46.77  514.01   116.6  514.95
  128.75  515.27  131.78  515.49  134.82  516.38  137.85  518.01  140.89  519.95
  143.93  520.84  146.96  521.85  162.14  531.38
#Mann= 3 , 0 , 0
       0      .1       0   32.24     .05       0   39.24      .1       0
Bank Sta=32.24,39.24
XS Rating Curve= 0 ,0
Exp/Cntr=0.3,0.1

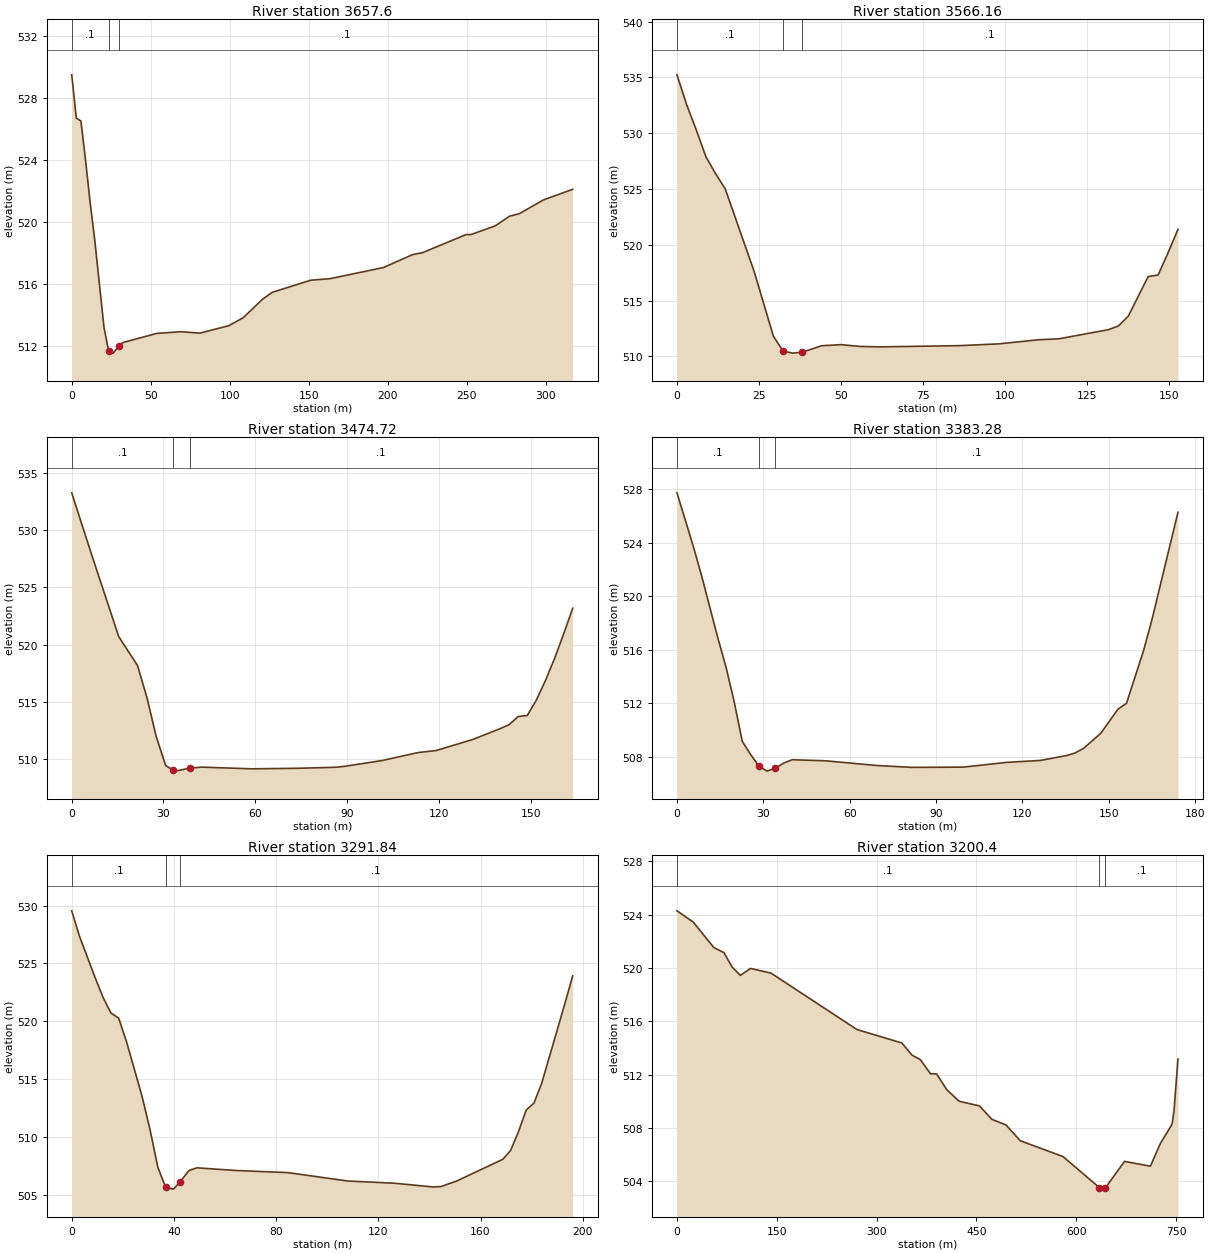
Type RM Length L Ch R = 1 ,3657.6  ,90.82,91.44,94.54
XS GIS Cut Line= 4
      607420.291    4343648.7579     607422.8764    4343622.6095
     607450.6515    4343497.6209     607458.4745    4343335.1704
#Sta/Elev= 30
       0  529.48    2.92  526.69    5.84   526.5    8.76  523.97   11.68  521.23
    14.6  518.81   20.44  513.19   23.36  511.69   26.28  511.54   30.03  512.03
   32.37  512.22   53.71  512.81   68.96  512.92   81.15  512.83   99.44  513.31
  108.59  513.83  120.78  515.02  126.88  515.46  151.26  516.24  163.52  516.34
  197.27  517.06  215.69  517.89  221.82  518.01  249.44  519.18  252.51  519.18
  267.85  519.74  277.06  520.37   283.2  520.53  298.54  521.42  316.95   522.1
#Mann= 3 , 0 , 0
       0      .1       0   23.36     .05       0   30.03      .1       0
Bank Sta=23.36,30.03
XS Rating Curve= 0 ,0
Exp/Cntr=0.3,0.1

Type RM Length L Ch R = 1 ,3566.16 ,92.23,91.44,91.06
XS GIS Cut Line= 3
     607496.4612    4343677.0202     607519.0009    4343622.7201
     607545.4804     4343532.546
#Sta/Elev= 26
       0  535.23    2.94  532.56    5.88   530.3    8.82  527.89   11.76  526.38
    14.7  525.02   23.52  517.62    29.4  511.81   32.34  510.47   35.28  510.29
   38.22  510.37   44.09  510.95   49.97  511.05   55.85  510.89   61.82  510.85
   86.08  510.96    98.2  511.12  110.33  511.49  116.39  511.57  131.55  512.39
  134.58  512.72  137.62   513.6  143.68  517.15  146.71  517.29  149.74  519.27
  152.77  521.38
#Mann= 3 , 0 , 0
       0      .1       0   32.34     .05       0   38.22      .1       0
Bank Sta=32.34,38.22
XS Rating Curve= 0 ,0
Exp/Cntr=0.3,0.1

Type RM Length L Ch R = 1 ,3474.72 ,93.12,91.44,91.98
XS GIS Cut Line= 5
      607588.673    4343702.4479     607597.2724    4343666.6022
     607603.9802    4343645.5486     607615.6145    4343620.5852
     607635.3912     4343545.911
#Sta/Elev= 28
       0  533.24    6.14  528.15   15.36   520.7    21.5  518.18   24.58  515.39
   27.65  511.95   30.72  509.44   33.08  509.07   33.79  508.96   38.59  509.22
   42.39  509.31   58.96  509.16   74.26  509.21    86.5   509.3   89.47  509.39
  101.36  509.88  113.24  510.58  119.18  510.76  131.07  511.72  139.98  512.66
  142.95  513.01  145.92  513.72  148.89  513.81  151.86  515.15  154.84  516.86
  157.81  518.78  160.78  520.92  163.75  523.17
#Mann= 3 , 0 , 0
       0      .1       0   33.08     .05       0   38.59      .1       0
Bank Sta=33.08,38.59
XS Rating Curve= 0 ,0
Exp/Cntr=0.3,0.1

Type RM Length L Ch R = 1 ,3383.28 ,91.16,91.44,88.58
XS GIS Cut Line= 5
     607673.6722    4343726.6269     607681.9441    4343699.5087
     607694.4936    4343670.0659     607697.4847    4343642.9523
       607724.34     4343560.821
#Sta/Elev= 28
       0  527.71    5.67  523.72    8.51  521.56   14.18   516.9   17.01  514.73
   19.85  512.15   22.68  509.18   25.52  508.21   28.35  507.35   31.26  506.95
   34.17  507.17   37.08  507.55   39.99   507.8   51.63  507.72   69.45  507.37
   81.57  507.23   99.55  507.25  114.45   507.6  126.37  507.75  135.31  508.11
  138.29   508.3  141.27  508.65  147.23  509.77  153.19  511.57  156.17  512.01
  162.13  515.96  165.11  518.33  174.05  526.26
#Mann= 3 , 0 , 0
       0      .1       0   28.35     .05       0   34.17      .1       0
Bank Sta=28.35,34.17
XS Rating Curve= 0 ,0
Exp/Cntr=0.3,0.1

Type RM Length L Ch R = 1 ,3291.84 ,96.9,91.44,59.14
XS GIS Cut Line= 4
     607750.2725    4343770.1592     607775.9673    4343711.1574
     607779.3844    4343679.7432     607804.7845    4343582.9055
#Sta/Elev= 30
       0  529.54    3.06  527.33    9.19  523.75   12.26  522.06   15.32  520.72
   18.39  520.26   21.45  518.23   27.58  513.47   30.64  510.64   33.71  507.38
   36.77  505.65   39.84  505.49    42.2  506.07   45.97  507.11   49.03  507.33
   64.35   507.1   84.46  506.92  108.09  506.19  126.29     506  141.46  505.68
  144.49  505.71  150.56  506.18  168.76  508.07   171.8  508.84  174.83  510.44
  177.86  512.32   180.9  512.92  183.93  514.63  193.03  521.54  196.07  523.92
#Mann= 3 , 0 , 0
       0      .1       0   36.77     .05       0    42.2      .1       0
Bank Sta=36.77,42.2
XS Rating Curve= 0 ,0
Exp/Cntr=0.3,0.1

Type RM Length L Ch R = 1 ,3200.4  ,75.21,91.44,107.29
XS GIS Cut Line= 6
     607411.5692    4344132.3006     607772.7262    4343882.2689
     607860.8432    4343742.4055     607854.9075    4343721.7849
     607825.9181    4343660.9136     607830.5456     4343601.915
#Sta/Elev= 30
       0  524.28   24.57  523.43   55.29  521.53   70.65  521.14   82.94  520.06
   95.22  519.44  110.58  519.96   141.3  519.61  270.31  515.38  337.89  514.37
  353.25  513.45  365.54  513.13   380.9  512.06  390.11  512.05  405.47  510.86
   423.9     510  454.57  509.65  472.93  508.65  494.36  508.22  515.79  507.04
  580.08  505.85  634.55  503.53  640.23  503.41  643.07  503.46  672.38  505.49
  711.28  505.13  726.08  506.81  743.83  508.28  746.79  509.28  752.71  513.16
#Mann= 3 , 0 , 0
       0      .1       0  634.55     .05       0  643.07      .1       0
Bank Sta=634.55,643.07
XS Rating Curve= 0 ,0
Exp/Cntr=0.3,0.1

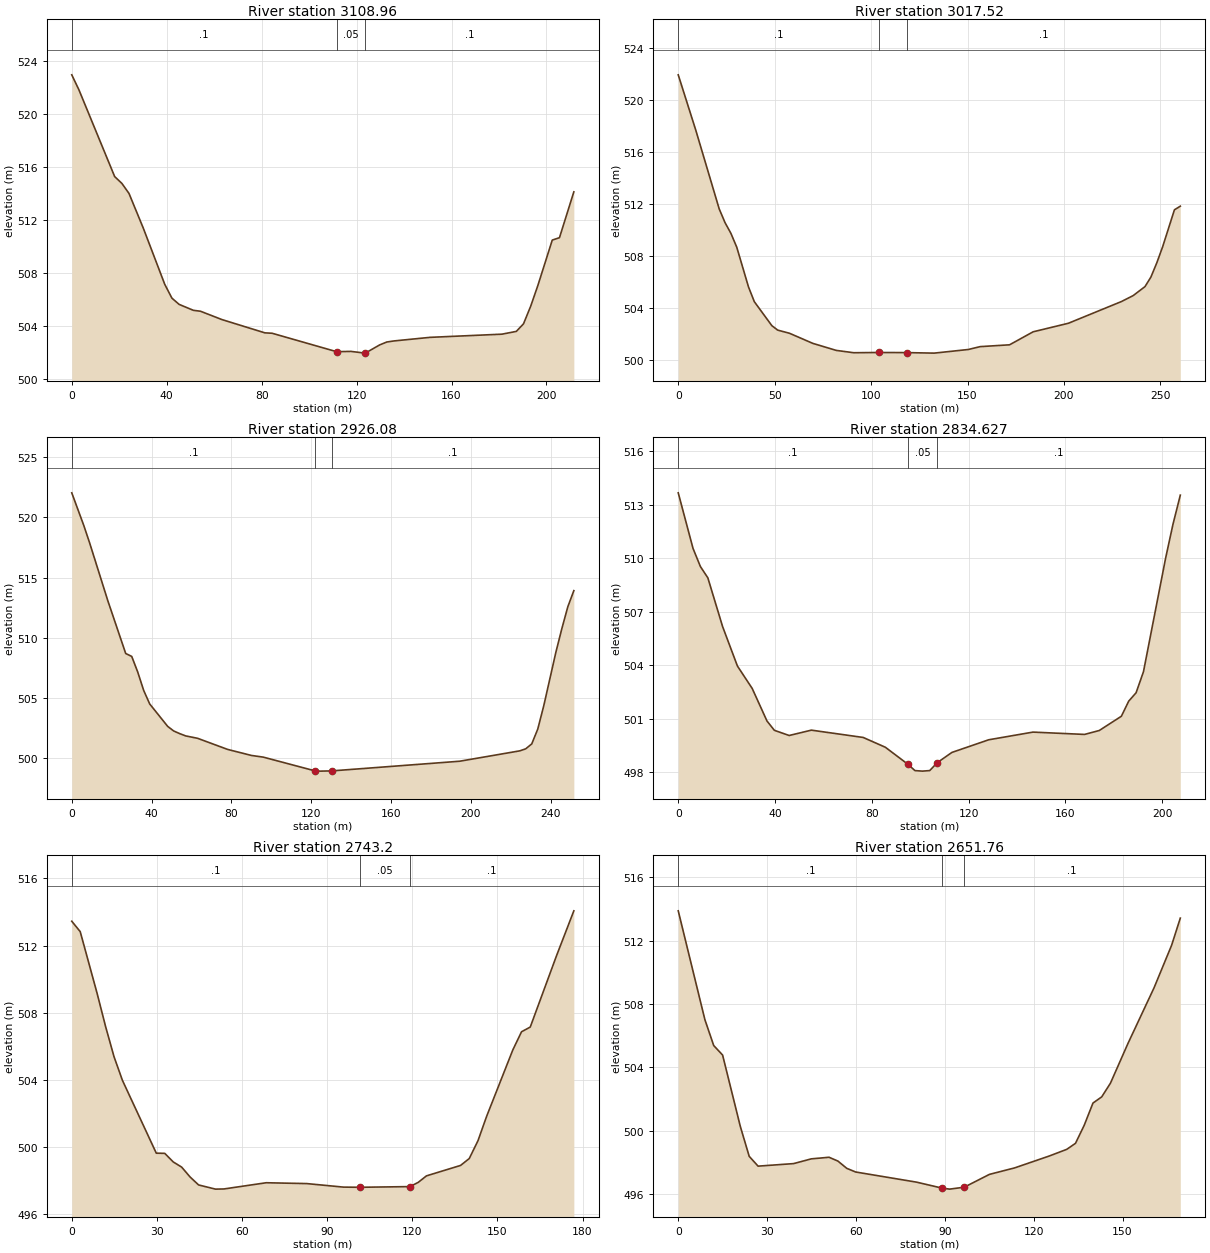
Type RM Length L Ch R = 1 ,3108.96 ,108.13,91.44,68.17
XS GIS Cut Line= 3
     607914.7037    4343815.6511     607933.1239    4343711.7898
     607945.8847    4343606.5148
#Sta/Elev= 30
       0  522.94    3.01  521.81   18.08  515.26    21.1  514.75   24.11  513.99
   30.14  511.37   39.18  507.13   42.19  506.09   45.21  505.62   51.23  505.17
   54.25   505.1   63.29  504.47   81.37  503.47   84.39  503.44  111.54  502.05
   117.6  502.07  123.54  501.94  123.66  501.94  129.72  502.56  132.75  502.78
  135.78  502.86  150.93  503.13  181.23  503.37  187.29  503.58  190.32  504.15
  193.35  505.48  196.38  507.05  202.44  510.47  205.47  510.65  211.53  514.11
#Mann= 3 , 0 , 0
       0      .1       0  111.54     .05       0  123.66      .1       0
Bank Sta=111.54,123.66
XS Rating Curve= 0 ,0
Exp/Cntr=0.3,0.1

Type RM Length L Ch R = 1 ,3017.52 ,20.17,91.44,113.42
XS GIS Cut Line= 5
     608023.4311    4343837.9423     608033.4853    4343747.4546
     608025.2587    4343730.9325     607996.7781    4343710.9134
     608031.8978     4343600.346
#Sta/Elev= 30
       0  521.95     9.1  517.69   21.24  511.63   24.28  510.57   27.31  509.75
   30.35  508.68   36.42  505.63   39.45  504.49   48.56  502.64   51.59   502.3
   57.66  502.06    69.8  501.28   81.94  500.74   91.04  500.56  104.23  500.58
  118.36  500.57  132.71  500.53  150.42  500.81  156.53  501.03  171.79  501.17
     184  502.17  202.32  502.83   229.8   504.5   235.9  504.96  242.01  505.65
  245.06  506.38  248.11  507.47  251.17  508.72  257.27  511.56  260.32  511.84
#Mann= 3 , 0 , 0
       0      .1       0  104.23     .05       0  118.36      .1       0
Bank Sta=104.23,118.36
XS Rating Curve= 0 ,0
Exp/Cntr=0.3,0.1

Type RM Length L Ch R = 1 ,2926.08 ,116.11,91.45,53.88
XS GIS Cut Line= 6
     608032.0262     4343839.379     608041.1692     4343755.778
     608057.5672    4343738.6157     608088.7556    4343725.5232
     608103.4787     4343704.581     608119.3389    4343621.7588
#Sta/Elev= 30
       0  522.02    6.01  519.32    9.01  517.84   18.02   513.1   27.03   508.7
   30.04  508.46   33.04  507.17   36.04  505.64   39.05  504.52   48.06  502.66
   51.06  502.28   54.06  502.06   57.07  501.87   63.07  501.67   78.09  500.75
   90.03  500.25   95.97  500.11  121.93  498.97  124.75  498.95  130.39  498.97
  194.37  499.77  224.48  500.63  227.49   500.8  230.51  501.21  233.52  502.44
  236.53  504.38  242.55  508.78  245.56  510.75  248.58  512.58  251.59  513.91
#Mann= 3 , 0 , 0
       0      .1       0  121.93     .05       0  130.39      .1       0
Bank Sta=121.93,130.39
XS Rating Curve= 0 ,0
Exp/Cntr=0.3,0.1

Type RM Length L Ch R = 1 ,2834.627,78.69,91.43,86.77
XS GIS Cut Line= 3
     608170.9327    4343835.4103     608155.1519    4343723.4333
      608151.633    4343629.1415
#Sta/Elev= 30
       0  513.67    6.11  510.55    9.17  509.53   12.23   508.9   18.34  506.16
   24.45  503.95   30.56  502.69   36.68  500.86   39.73  500.34   45.84  500.05
   55.01  500.35   76.41  499.94   85.58  499.39   94.75  498.45    97.8  498.08
  100.86  498.05  103.91  498.08  106.97  498.52  113.08   499.1   128.3  499.81
  146.57  500.24  167.87  500.11  173.96  500.33  183.09  501.13  186.13  501.98
  189.18  502.45  192.22  503.63  201.35  509.99   204.4   511.9  207.44  513.54
#Mann= 3 , 0 , 0
       0      .1       0   94.75     .05       0  106.97      .1       0
Bank Sta=94.75,106.97
XS Rating Curve= 0 ,0
Exp/Cntr=0.3,0.1

Type RM Length L Ch R = 1 ,2743.2  ,55.62,91.44,65.97
XS GIS Cut Line= 5
     608218.1753    4343820.1566     608226.5631    4343740.1609
     608234.3729    4343734.8498     608239.0574    4343694.1453
      608247.662    4343648.8787
#Sta/Elev= 30
       0  513.45    2.98  512.83    8.94  509.15   11.92  507.18    14.9  505.38
   17.87  503.97   29.79  499.64   32.77  499.63   35.75  499.12   38.73  498.81
   41.71  498.22   44.69  497.75   50.64   497.5   53.62  497.51   68.52  497.88
    82.8  497.83   95.73  497.62  101.59  497.61  119.15  497.65  122.07   497.9
     125  498.29     137  498.91  140.07  499.32  143.14  500.38  146.21  501.84
  155.43  505.79   158.5  506.87  161.57  507.15  170.79  511.38  176.93  514.07
#Mann= 3 , 0 , 0
       0      .1       0  101.59     .05       0  119.15      .1       0
Bank Sta=101.59,119.15
XS Rating Curve= 0 ,0
Exp/Cntr=0.3,0.1

Type RM Length L Ch R = 1 ,2651.76 ,80.21,91.44,103.32
XS GIS Cut Line= 6
     608253.2505    4343825.5979     608277.0937    4343760.9645
     608285.0791    4343742.3319     608283.3958    4343735.1471
     608284.5864    4343715.3033     608301.2552       4343664.9
#Sta/Elev= 30
       0  513.88    8.99  507.02   11.98  505.38   14.98  504.78   20.97  500.27
   23.96  498.39   26.96  497.77   38.94  497.93   44.93  498.23   50.92  498.33
   53.91  498.09   56.91  497.63   59.91   497.4   80.47  496.76   89.16  496.38
   91.62  496.32   96.54  496.44  105.06  497.25  113.58  497.66  125.27  498.41
  131.17  498.83  134.12  499.21  137.07  500.35  140.02  501.75  142.97  502.14
  145.91     503  151.81   505.5  160.66  509.03  166.56   511.7  169.51  513.42
#Mann= 3 , 0 , 0
       0      .1       0   89.16     .05       0   96.54      .1       0
Bank Sta=89.16,96.54
XS Rating Curve= 0 ,0
Exp/Cntr=0.3,0.1

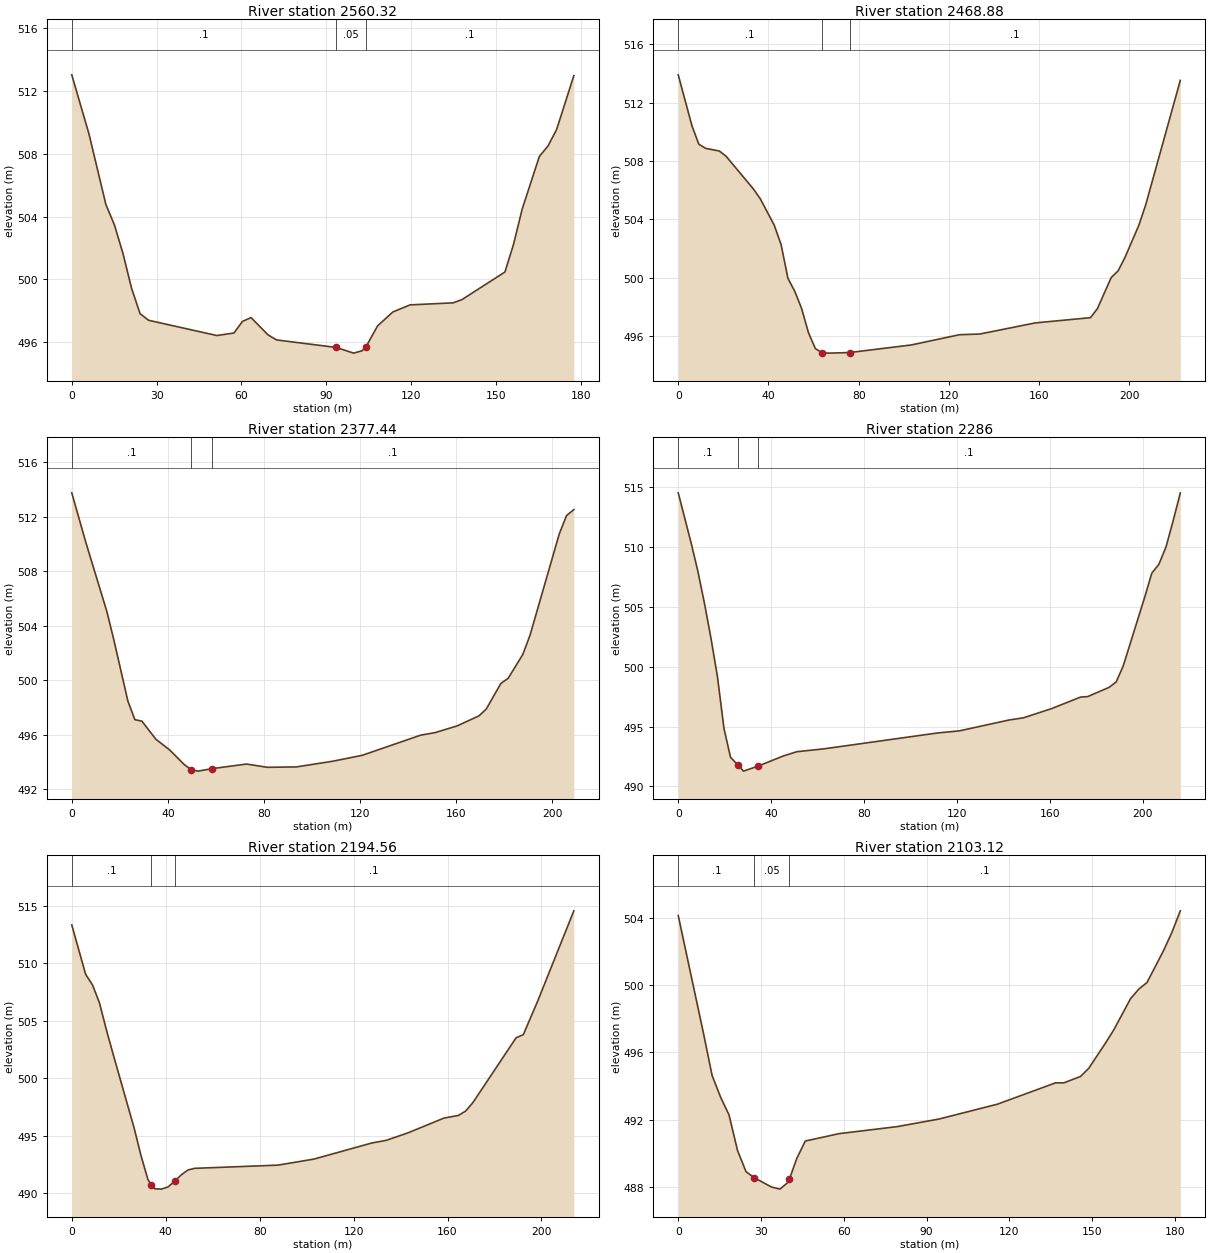
Type RM Length L Ch R = 1 ,2560.32 ,88.3,91.44,83.79
XS GIS Cut Line= 5
     608313.2017    4343847.3717     608363.0299    4343771.7461
     608373.3366    4343765.3331     608379.6249    4343756.4725
     608403.8216    4343697.2203
#Sta/Elev= 30
       0  513.02    6.04  509.29   12.08  504.76   15.09  503.47   18.11  501.65
   21.13  499.45   24.15  497.82   27.17   497.4   51.32  496.43   57.36  496.59
   60.38  497.33    63.4  497.57   69.43  496.47   72.45  496.15    93.6  495.67
   99.67  495.31   102.7  495.46  104.09  495.72  108.14  497.04  113.57  497.93
  119.66  498.38   134.9  498.51  137.95  498.71  153.19  500.47  156.24  502.23
  159.29  504.47  165.38  507.83  168.43  508.49  171.48  509.54  177.57  512.97
#Mann= 3 , 0 , 0
       0      .1       0    93.6     .05       0  104.09      .1       0
Bank Sta=93.6,104.09
XS Rating Curve= 0 ,0
Exp/Cntr=0.3,0.1

Type RM Length L Ch R = 1 ,2468.88 ,95.5,91.44,62.99
XS GIS Cut Line= 3
     608377.0657    4343899.2122     608450.4268    4343791.0012
     608471.5491    4343701.5626
#Sta/Elev= 30
       0  513.91    6.08  510.42    9.12  509.16   12.16  508.87   18.24  508.69
   21.28  508.32   33.44  506.07   36.48  505.39   42.56  503.61   45.61  502.28
   48.65  499.96   51.69  499.07   54.73  497.89   57.77  496.23   60.81  495.15
   63.85  494.86   66.89  494.84   76.01  494.88  103.37   495.4  124.65   496.1
   133.8  496.15   158.3  496.91  182.81  497.27  185.87  497.89     192  500.02
  195.06  500.48  198.13  501.41  204.25   503.6  207.32  505.02  222.63  513.53
#Mann= 3 , 0 , 0
       0      .1       0   63.85     .05       0   76.01      .1       0
Bank Sta=63.85,76.01
XS Rating Curve= 0 ,0
Exp/Cntr=0.3,0.1

Type RM Length L Ch R = 1 ,2377.44 ,94.44,91.44,67.54
XS GIS Cut Line= 4
      608496.426    4343902.9343     608501.0878    4343850.6057
     608500.4245    4343821.7569     608490.4729    4343694.5745
#Sta/Elev= 30
       0  513.77    5.84  510.14   14.59  505.06   17.51  502.97   23.35  498.48
   26.27  497.11   29.19     497   35.02  495.67   40.86  494.87    46.7  493.83
   49.62  493.44   52.54  493.33   58.31  493.51   72.74  493.85   81.39  493.61
   93.54  493.64  108.73  494.06  120.88  494.49  145.18  495.97  151.25  496.16
  160.36  496.65  169.48  497.39  172.51  497.89  178.59  499.77  181.63  500.15
   187.7  501.89  190.74  503.32  202.89  510.75  205.93   512.1  208.96  512.54
#Mann= 3 , 0 , 0
       0      .1       0   49.62     .05       0   58.31      .1       0
Bank Sta=49.62,58.31
XS Rating Curve= 0 ,0
Exp/Cntr=0.3,0.1

Type RM Length L Ch R = 1 ,2286    ,91.84,91.44,90.17
XS GIS Cut Line= 4
     608596.8649    4343885.1265     608584.2672    4343859.9819
     608572.0484    4343830.9398     608526.1917    4343681.3453
#Sta/Elev= 30
       0  514.51    5.62  510.27    8.44  507.97   11.25  505.32   14.06  502.41
   16.87  499.18   19.69  494.84    22.5  492.44   25.55  491.81   28.12  491.28
   34.37   491.7   45.31  492.55   51.04   492.9    62.7  493.14  111.79  494.47
  120.99  494.64  142.47  495.55   148.6  495.73  160.87  496.51  173.15  497.46
  176.21   497.5  185.42  498.27  188.49  498.72  191.55  500.07  200.76  505.79
  203.83   507.8  206.89  508.55  209.96     510  213.03  512.19   216.1   514.5
#Mann= 3 , 0 , 0
       0      .1       0   25.55     .05       0   34.37      .1       0
Bank Sta=25.55,34.37
XS Rating Curve= 0 ,0
Exp/Cntr=0.3,0.1

Type RM Length L Ch R = 1 ,2194.56 ,91.5,91.44,93.05
XS GIS Cut Line= 4
     608681.6851     4343861.492     608669.2487    4343828.3985
     608656.8239    4343800.0507     608614.1658    4343658.8557
#Sta/Elev= 30
       0  513.35    5.89  509.06    8.84  508.12   11.78  506.57   14.73  504.22
   17.68  502.04   26.51  495.69   29.46  493.27   32.41  491.18   33.78  490.72
   35.35  490.36   38.17  490.33   40.98  490.52   43.79  491.01   46.61  491.57
   49.42  491.99   52.24  492.14   87.81  492.42  103.18  492.95  127.76  494.35
  133.91  494.58  143.13  495.23  158.49  496.52  164.64  496.75  167.71  497.13
  170.78  497.86  189.22  503.52  192.29  503.79  198.44  506.73   213.8  514.58
#Mann= 3 , 0 , 0
       0      .1       0   33.78     .05       0   43.79      .1       0
Bank Sta=33.78,43.79
XS Rating Curve= 0 ,0
Exp/Cntr=0.3,0.1

Type RM Length L Ch R = 1 ,2103.12 ,90.52,91.44,96.23
XS GIS Cut Line= 3
     608765.5103    4343828.2365     608745.0706    4343770.3243
     608709.9773     4343654.949
#Sta/Elev= 30
       0  504.14    9.21  497.09   12.28  494.63   15.35  493.34   18.42  492.28
   21.49  490.17   24.57  488.91   27.64  488.54   33.78     488   36.85  487.87
   39.92  488.29   40.27  488.45   42.99   489.7   46.06  490.73   58.34  491.17
    79.5  491.59   94.58  492.04  115.68  492.92  136.78  494.19   139.8  494.19
  145.83  494.57  148.84  495.06  154.87  496.55  157.89  497.34  163.92  499.18
  166.93  499.76  169.95  500.16  175.98  502.07  178.99  503.15  182.01  504.42
#Mann= 3 , 0 , 0
       0      .1       0   27.64     .05       0   40.27      .1       0
Bank Sta=27.64,40.27
XS Rating Curve= 0 ,0
Exp/Cntr=0.3,0.1

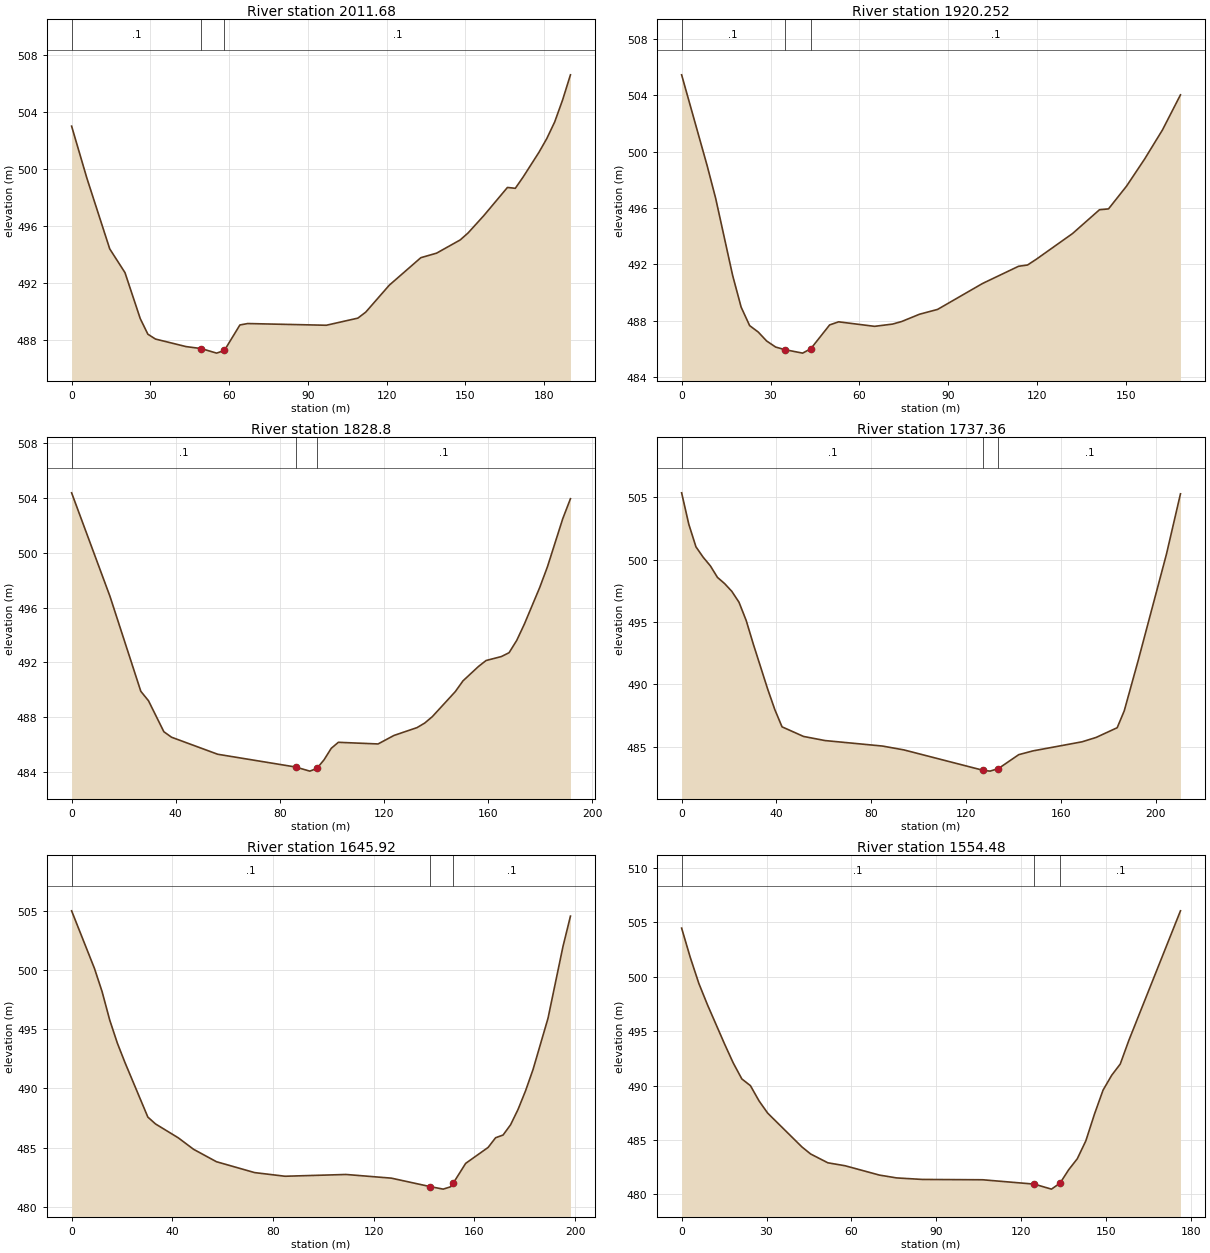
Type RM Length L Ch R = 1 ,2011.68 ,89.14,91.43,93.54
XS GIS Cut Line= 4
      608856.722     4343817.716     608839.3839    4343768.3745
     608835.7529    4343750.9974     608804.8426    4343635.0211
#Sta/Elev= 30
       0  503.03    5.81  499.38   14.53   494.4   20.34  492.73   26.15   489.5
   29.06   488.4   31.96  488.06   43.58  487.53   49.39  487.39   55.26  487.07
   58.22  487.26   64.13  489.05   67.09  489.15   97.06  489.03  109.06  489.53
  112.06  489.95  121.06  491.85  133.06  493.78  139.07   494.1  148.07  495.03
  151.07  495.52  157.07  496.74  166.07  498.72  169.07  498.66  172.07  499.46
  178.07  501.19  181.07  502.16  184.08  503.33  187.08  504.87  190.08  506.64
#Mann= 3 , 0 , 0
       0      .1       0   49.39     .05       0   58.22      .1       0
Bank Sta=49.39,58.22
XS Rating Curve= 0 ,0
Exp/Cntr=0.3,0.1

Type RM Length L Ch R = 1 ,1920.252,94.99,91.45,88.78
XS GIS Cut Line= 3
      608932.115    4343786.3306     608927.1281    4343758.0674
     608922.5824    4343618.4846
#Sta/Elev= 30
       0  505.45    8.61  499.01   11.48   496.7   17.22  491.22   20.09  488.97
   22.96  487.66   25.83  487.21    28.7  486.57   31.74  486.14   34.77  485.96
   40.84  485.71   43.59  486.02   49.95  487.71   52.99  487.93   65.13  487.61
    71.2  487.77   74.24  487.95   80.31  488.47   86.38  488.81  101.56  490.65
  113.71  491.87  116.74  491.96  119.78  492.38  131.92  494.19  141.03  495.88
  144.07  495.94  150.14  497.55  156.21  499.46  162.28  501.54  168.36  504.03
#Mann= 3 , 0 , 0
       0      .1       0   34.77     .05       0   43.59      .1       0
Bank Sta=34.77,43.59
XS Rating Curve= 0 ,0
Exp/Cntr=0.3,0.1

Type RM Length L Ch R = 1 ,1828.8  ,91.95,91.44,94.15
XS GIS Cut Line= 6
     609039.8904    4343776.7538     609018.2675    4343724.9727
     609003.1481    4343702.3953     608990.0671    4343688.3664
     608972.6268    4343676.0247      608939.576    4343616.8293
#Sta/Elev= 30
       0  504.36   14.77   496.8   26.58   489.9   29.53  489.21   35.44  486.95
   38.39  486.55   56.11  485.31   86.03  484.38   91.51  484.08   94.25  484.28
   96.99  484.91   99.73  485.74  102.47  486.18  117.73  486.06  123.83  486.68
  132.68  487.25  135.62  487.58  138.57  488.05  147.42  489.88  150.36  490.66
  156.26   491.7  159.21  492.14   165.1  492.43  168.05  492.71     171  493.61
  173.94   494.8  179.84  497.47  182.79  498.97  188.68  502.48  191.63  503.93
#Mann= 3 , 0 , 0
       0      .1       0   86.03     .05       0   94.25      .1       0
Bank Sta=86.03,94.25
XS Rating Curve= 0 ,0
Exp/Cntr=0.3,0.1

Type RM Length L Ch R = 1 ,1737.36 ,91.2,91.44,91.33
XS GIS Cut Line= 3
     609150.1946    4343743.7926     609061.8921    4343632.2666
     609027.2005    4343573.5028
#Sta/Elev= 30
       0  505.35    3.03  502.83    6.05  501.02    9.08  500.19   12.11   499.5
   15.13  498.57   18.16  498.07   21.19  497.45   24.21  496.58   27.24  495.12
   30.27  493.21   36.32  489.61   39.35  487.96   42.37  486.59   51.45  485.82
   60.53  485.49   84.75  485.05   93.83  484.74  127.12  483.11  130.14  483.04
   133.7  483.25  142.25  484.36  148.19  484.66  168.95  485.39  174.89  485.74
  183.79  486.52  186.76  487.87  192.69  491.94  204.56  500.42  210.49  505.27
#Mann= 3 , 0 , 0
       0      .1       0  127.12     .05       0   133.7      .1       0
Bank Sta=127.12,133.7
XS Rating Curve= 0 ,0
Exp/Cntr=0.3,0.1

Type RM Length L Ch R = 1 ,1645.92 ,85.8,91.44,92.37
XS GIS Cut Line= 4
     609224.3898    4343695.5816     609152.0368    4343598.4551
     609137.2364    4343580.1981     609108.4143    4343535.1096
#Sta/Elev= 30
       0  505.04    9.08  500.16   12.11   498.2   15.14  495.79   18.17  493.84
   21.19   492.2   30.28  487.58   33.31     487   42.39  485.82   48.45  484.85
   57.53   483.8   72.67  482.88   84.78  482.57     109  482.72  126.99  482.41
  142.47  481.69  147.59  481.48  150.56  481.68   151.5  481.96  156.51  483.66
  165.43  485.01   168.4  485.83  171.37  486.06  174.35  486.93  177.32  488.23
  180.29   489.8  183.26   491.6  189.21  495.94  195.16  502.02  198.13  504.59
#Mann= 3 , 0 , 0
       0      .1       0  142.47     .05       0   151.5      .1       0
Bank Sta=142.47,151.5
XS Rating Curve= 0 ,0
Exp/Cntr=0.3,0.1

Type RM Length L Ch R = 1 ,1554.48 ,96.96,91.47,91.67
XS GIS Cut Line= 2
     609281.5371    4343651.8241     609196.7782    4343497.3062
#Sta/Elev= 30
       0  504.48    3.04   501.8    6.08   499.4    9.12  497.44   15.19  493.82
   18.23  492.09   21.27  490.62   24.31     490   27.35   488.6   30.39  487.48
   42.54  484.36   45.58  483.72   51.66  482.91   57.73  482.64   69.89  481.78
   75.96  481.52   85.08  481.38  106.35  481.35  124.58  480.95  130.66  480.49
   133.7  481.04  136.74  482.27  139.78  483.28  142.81  484.93  145.85  487.38
  148.89  489.59  151.93  490.95  154.97  491.99  158.01  494.17  176.24  506.07
#Mann= 3 , 0 , 0
       0      .1       0  124.58     .05       0   133.7      .1       0
Bank Sta=124.58,133.7
XS Rating Curve= 0 ,0
Exp/Cntr=0.3,0.1