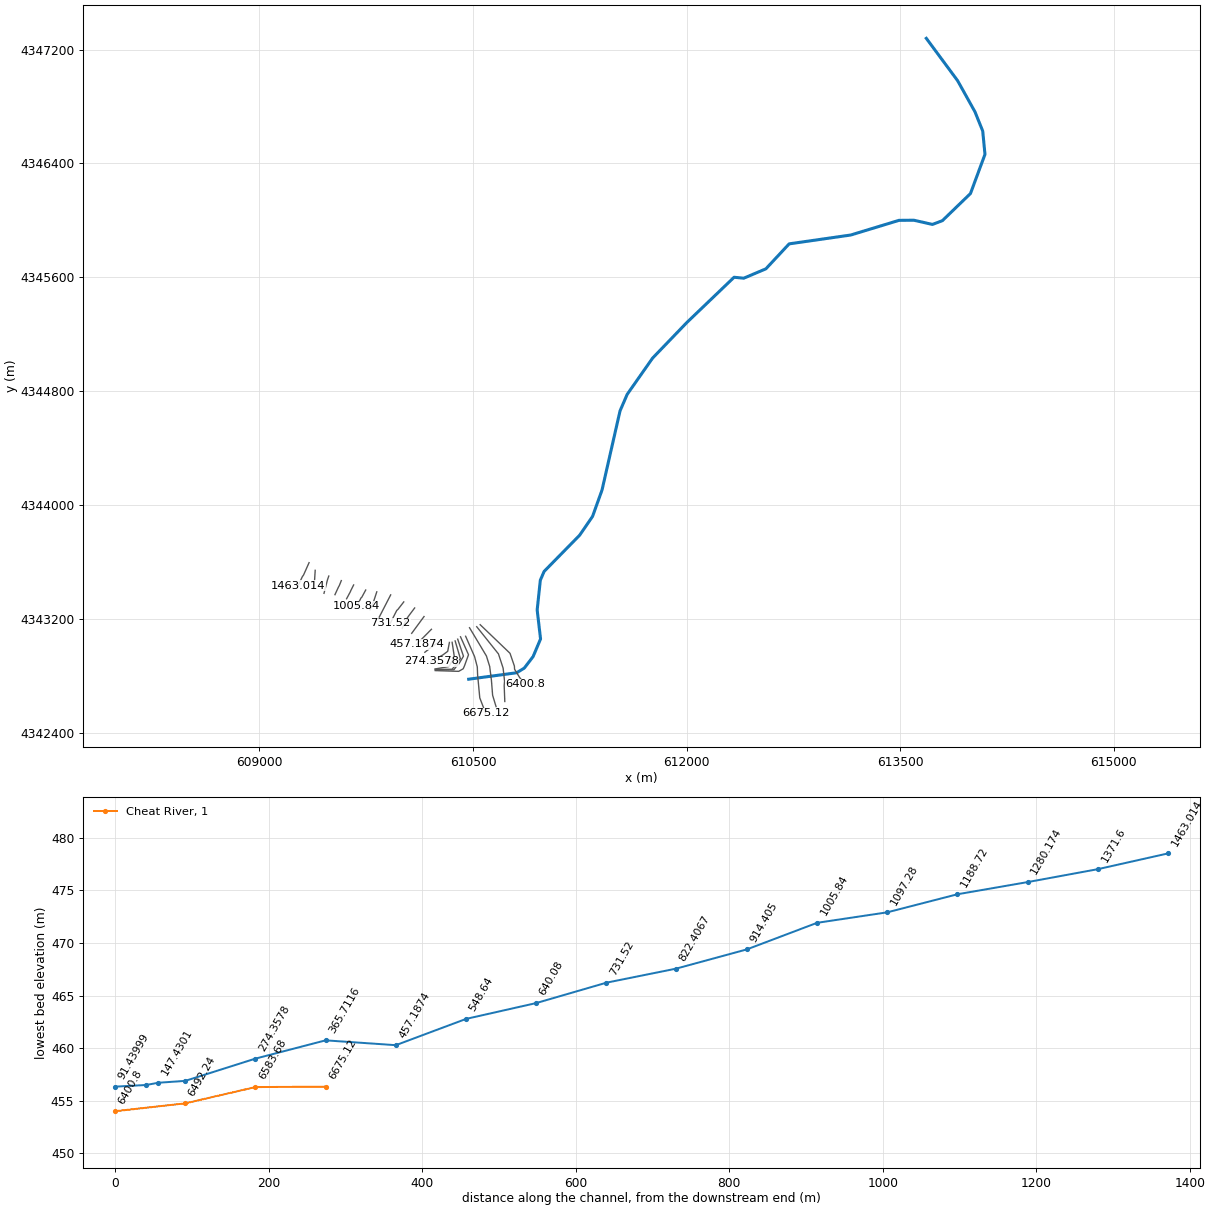
HEC-RAS study CheatRiver.prj: CheatRiver

--- CheatRiver.g01 (geometry) --- (continued)

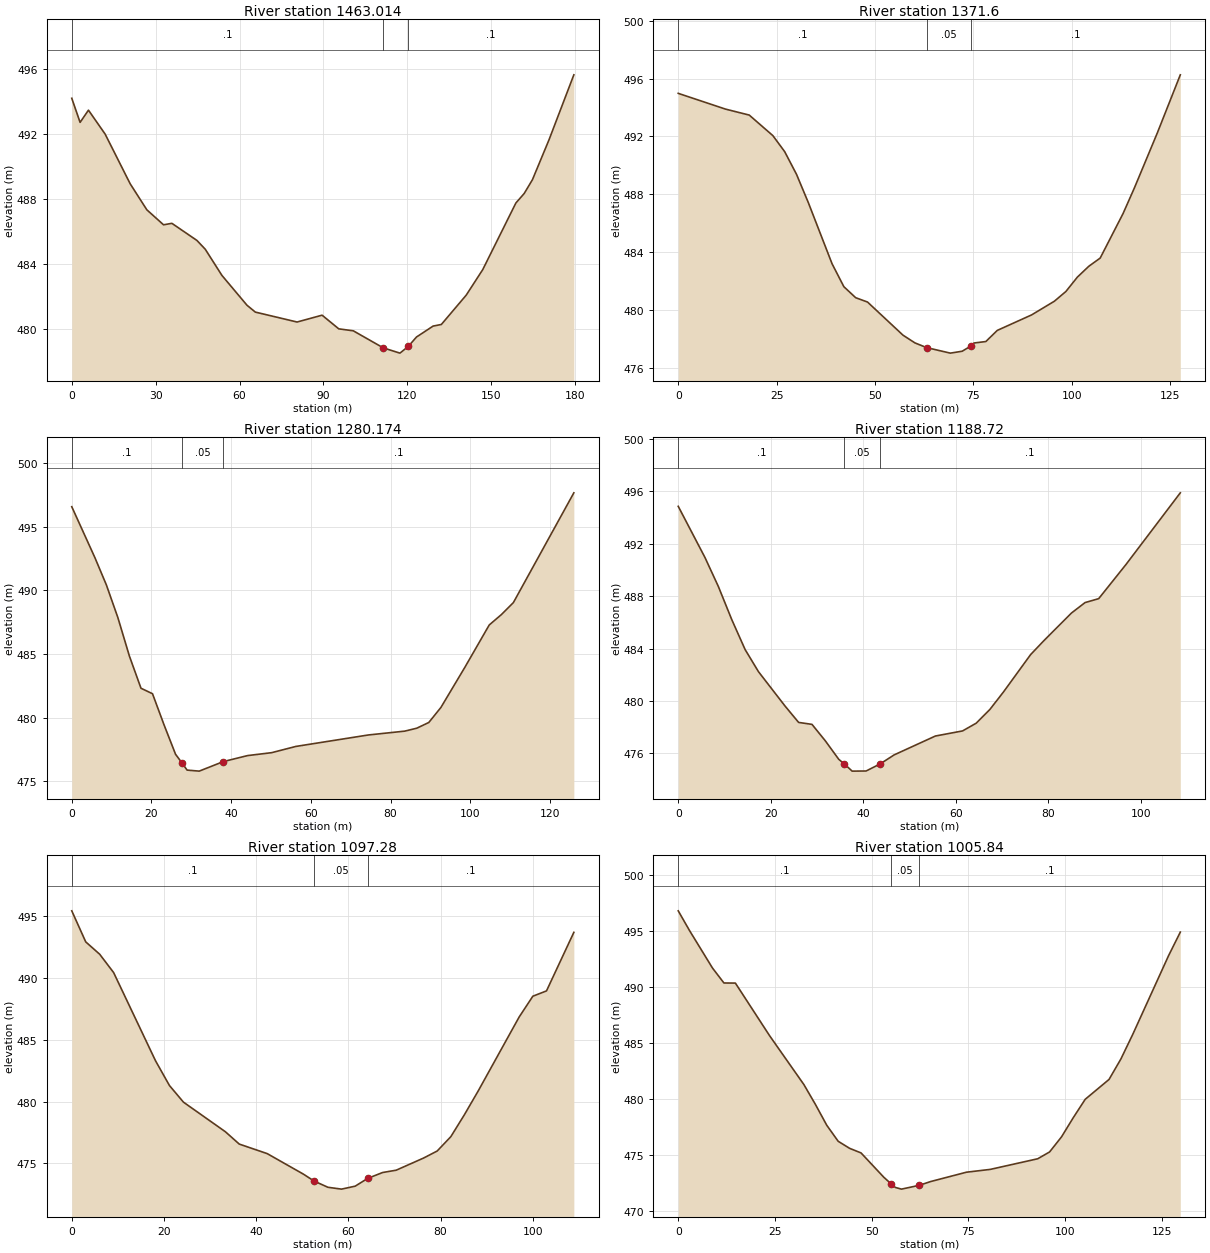
Type RM Length L Ch R = 1 ,1463.014,88.79,91.41,92.84
XS GIS Cut Line= 4
     609348.1434    4343596.2267      609309.252    4343508.9942
     609301.4281    4343498.6211     609271.1055     4343434.321
#Sta/Elev= 30
       0  494.18    2.98   492.7    5.97  493.45   11.94  491.98   20.89  488.93
   26.86  487.33   32.83  486.41   35.82   486.5   44.77  485.45   47.75  484.91
   53.72   483.3   62.68  481.47   65.66  481.05   80.59  480.44   89.54  480.86
   95.51  480.02  100.71   479.9  111.46  478.85  117.39  478.53  120.35  478.94
  123.31  479.52  129.24  480.19   132.2  480.29  141.09  482.09  147.01  483.66
  158.86  487.75  161.82  488.33  164.78  489.18  170.71  491.63  179.59  495.62
#Mann= 3 , 0 , 0
       0      .1       0  111.46     .05       0  120.35      .1       0
Bank Sta=111.46,120.35
XS Rating Curve= 0 ,0
Exp/Cntr=0.3,0.1

Type RM Length L Ch R = 1 ,1371.6  ,91.87,91.43,87.58
XS GIS Cut Line= 3
     609391.3046    4343542.4013     609386.3246    4343464.3815
     609375.3526    4343416.1849
#Sta/Elev= 30
       0  494.98   12.03  493.89   18.04  493.48   24.05  492.06   27.06  490.95
   30.07  489.38   33.08  487.42   39.09  483.21    42.1  481.62    45.1  480.86
   48.11  480.56   57.13  478.27   60.14  477.74   63.14  477.41   69.16  477.03
   72.16  477.16   74.38  477.52   75.17  477.73   78.18  477.83   81.09   478.6
   89.81  479.67   95.62  480.62   98.53  481.29  101.44  482.28  104.35  483.03
  107.25   483.6  113.07  486.68  115.98  488.47  121.79  492.26  127.61  496.26
#Mann= 3 , 0 , 0
       0      .1       0   63.14     .05       0   74.38      .1       0
Bank Sta=63.14,74.38
XS Rating Curve= 0 ,0
Exp/Cntr=0.3,0.1

Type RM Length L Ch R = 1 ,1280.174,93.8,91.45,87.64
XS GIS Cut Line= 3
     609486.6073    4343502.2386     609477.2841    4343474.8381
     609453.0334    4343380.8751
#Sta/Elev= 26
       0  496.57    5.79  492.58    8.68  490.43   11.58  487.85   14.47  484.83
   17.37  482.31   20.26  481.88   23.15  479.44   26.05  477.12   27.67  476.44
   28.94  475.88   31.98   475.8   38.04  476.55   44.11  477.02   50.17  477.25
   56.24  477.74   74.43  478.64   83.53  478.94   86.56  479.17   89.59  479.62
   92.63   480.8   98.69  483.98  104.76  487.28  107.79  488.09  110.82  489.04
  125.99  497.66
#Mann= 3 , 0 , 0
       0      .1       0   27.67     .05       0   38.04      .1       0
Bank Sta=27.67,38.04
XS Rating Curve= 0 ,0
Exp/Cntr=0.3,0.1

Type RM Length L Ch R = 1 ,1188.72 ,88.64,91.44,90.68
XS GIS Cut Line= 4
      609574.691    4343470.1625     609560.6276    4343435.3053
     609554.6307    4343424.7852     609530.0273      4343371.35
#Sta/Elev= 28
       0  494.86    5.78  490.95    8.67  488.74   11.57  486.21   14.46  483.92
   17.35  482.23   23.13  479.59   26.02  478.36   28.91  478.21    31.8  476.95
    34.7  475.54   35.93  475.18   37.59  474.64   40.61  474.65   43.64  475.19
   46.67  475.88   55.58  477.32   61.46  477.71    64.4   478.3   67.34  479.34
   70.29  480.68   76.17  483.54   79.11  484.63   84.99  486.71   87.93  487.51
   90.88  487.81   96.76  490.41  108.52  495.89
#Mann= 3 , 0 , 0
       0      .1       0   35.93     .05       0   43.64      .1       0
Bank Sta=35.93,43.64
XS Rating Curve= 0 ,0
Exp/Cntr=0.3,0.1

Type RM Length L Ch R = 1 ,1097.28 ,95.51,91.44,87.06
XS GIS Cut Line= 4
     609661.1371    4343439.5448     609640.7688    4343398.9514
     609638.3641    4343392.1991      609611.666    4343342.6169
#Sta/Elev= 27
       0  495.41    3.03   492.9    6.06   491.9    9.08  490.42   18.17  483.29
   21.19  481.29   24.22  479.95   33.31  477.56   36.33  476.56   42.39  475.79
    50.2  474.14   52.58  473.57   55.55  473.07   58.51  472.92   61.48  473.16
   64.15  473.78    67.4  474.26   70.37  474.45    76.3  475.43   79.26     476
   82.22  477.16   85.19  478.95   88.15  480.85   97.04  486.83  100.01  488.51
  102.97  488.94   108.9  493.67
#Mann= 3 , 0 , 0
       0      .1       0   52.58     .05       0   64.15      .1       0
Bank Sta=52.58,64.15
XS Rating Curve= 0 ,0
Exp/Cntr=0.3,0.1

Type RM Length L Ch R = 1 ,1005.84 ,99.65,91.43,93
XS GIS Cut Line= 5
     609745.9277    4343403.8938     609719.2028    4343354.5587
     609717.2962    4343352.0166     609712.7512    4343348.1228
     609684.0151    4343290.3874
#Sta/Elev= 30
       0  496.76    2.95  494.98    8.86  491.65   11.81  490.32   14.77  490.31
   23.62  485.61   32.48  481.25   35.44  479.49   38.39  477.62   41.34  476.19
    44.3  475.56   47.25  475.15   53.16  472.97      55   472.4   56.11  472.07
    57.7  471.92   62.28  472.26   65.27   472.6   74.48  473.43   80.63  473.68
   92.91  474.63   95.98  475.24   99.05  476.58  102.12  478.31  105.19  479.94
  111.34  481.71  114.41  483.54  117.48  485.74  126.69  492.73  129.76  494.86
#Mann= 3 , 0 , 0
       0      .1       0      55     .05       0   62.28      .1       0
Bank Sta=55,62.28
XS Rating Curve= 0 ,0
Exp/Cntr=0.3,0.1

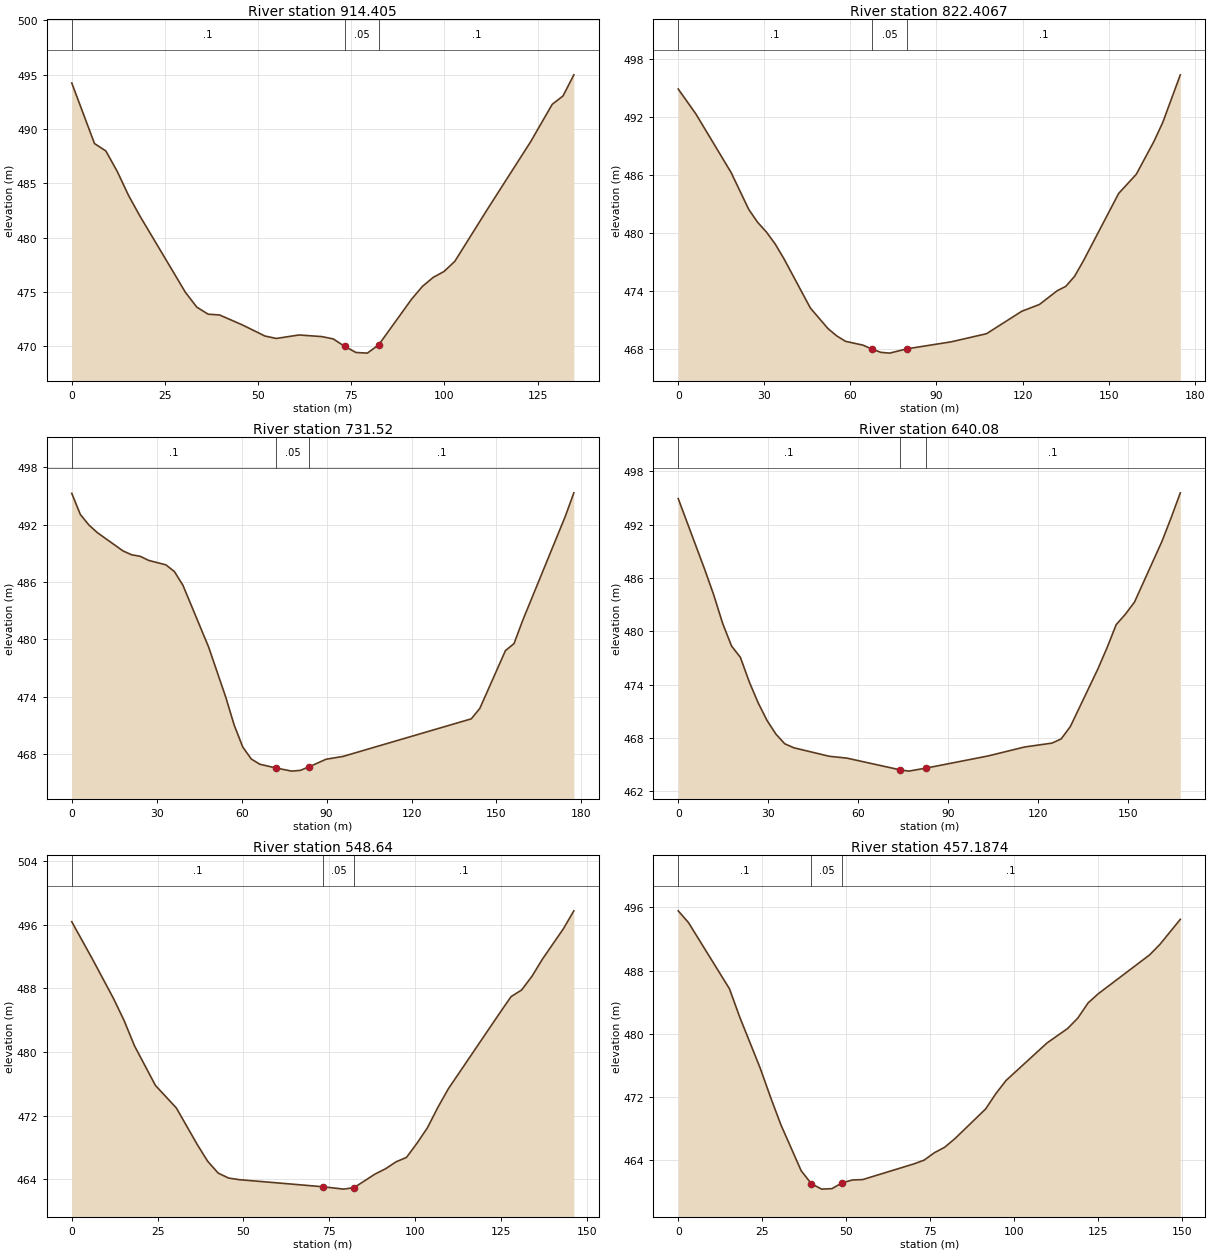
Type RM Length L Ch R = 1 ,914.405 ,99.81,92,91.93
XS GIS Cut Line= 3
     609823.7153    4343391.1938     609797.1053    4343310.0391
     609776.4265    4343265.2592
#Sta/Elev= 30
       0  494.23     6.1  488.66    9.15  487.98    12.2   486.1   15.25  483.88
    18.3  481.99    30.5  474.98   33.55  473.62    36.6  472.97   39.65   472.9
   45.75  471.99   51.85  470.96    54.9  470.74      61  471.06    67.1  470.91
   70.15   470.7   73.21  470.02   76.26  469.45   79.31  469.39   82.36  470.15
   91.21  474.36   94.11  475.53   97.01  476.36   99.91   476.9  102.81  477.84
  111.52  482.61  123.12  488.82  128.93  492.27  131.83  493.04  134.73  494.98
#Mann= 3 , 0 , 0
       0      .1       0   73.21     .05       0   82.36      .1       0
Bank Sta=73.21,82.36
XS Rating Curve= 0 ,0
Exp/Cntr=0.3,0.1

Type RM Length L Ch R = 1 ,822.4067,93.74,90.89,89.06
XS GIS Cut Line= 2
     609921.3468    4343369.7625     609841.1828    4343214.1992
#Sta/Elev= 30
       0  494.88    6.14  492.31   18.42  486.25   24.56  482.44   27.63  481.11
    30.7   480.1   33.77  478.86   36.84  477.33   46.05  472.23   52.19   470.1
   55.26  469.34   58.33  468.78   64.47  468.38   67.55  467.97   70.62  467.64
   73.69  467.56   79.83  468.01   95.18  468.73  107.46  469.57  119.74  471.89
  125.88  472.59  132.02     474  135.09  474.47  138.16  475.51  141.23  477.11
  153.51  484.08  159.65  486.06  165.79  489.45  168.86  491.41     175  496.35
#Mann= 3 , 0 , 0
       0      .1       0   67.55     .05       0   79.83      .1       0
Bank Sta=67.55,79.83
XS Rating Curve= 0 ,0
Exp/Cntr=0.3,0.1

Type RM Length L Ch R = 1 ,731.52  ,88.66,91.44,92.01
XS GIS Cut Line= 4
     610013.3029    4343320.5102     609972.4967    4343268.0741
     609964.0182    4343260.6604     609918.9803    4343171.8097
#Sta/Elev= 30
       0  495.28    3.02  493.07    6.04  491.97    9.06  491.16   18.12  489.25
   21.14  488.85   24.16  488.69   27.18  488.26   33.22   487.8   36.24   487.1
   39.26  485.66   48.32  479.21   54.36  473.98   57.38  471.02    60.4  468.74
   63.42  467.48   66.44  466.94   72.07  466.55   77.71  466.22   80.72   466.3
   83.74  466.66   89.78  467.46   95.82  467.76   141.1  471.69  144.11  472.78
  153.17  478.83  156.19  479.56  159.21  481.95   174.3  492.87  177.32  495.33
#Mann= 3 , 0 , 0
       0      .1       0   72.07     .05       0   83.74      .1       0
Bank Sta=72.07,83.74
XS Rating Curve= 0 ,0
Exp/Cntr=0.3,0.1

Type RM Length L Ch R = 1 ,640.08  ,90.74,91.44,91.58
XS GIS Cut Line= 4
     610089.7897    4343277.9453     610047.0508    4343221.0947
     610032.5149    4343199.4282     610002.5058    4343135.8052
#Sta/Elev= 30
       0  494.91    8.89   486.9   11.85  484.08   14.82  480.89   17.78  478.35
   20.74  477.07   23.71  474.31   26.67  471.96   29.63  469.98    32.6  468.44
   35.56  467.35   38.53  466.91   50.38  465.95   56.31  465.74   73.96  464.43
   76.92  464.28   82.72  464.62  103.33  465.98  115.57  466.99  124.74  467.43
   127.8   467.9  130.86  469.29  140.03  475.75  143.09  478.13  146.15  480.74
  149.21  481.91  152.27  483.28  161.44  490.11   164.5  492.76  167.56  495.56
#Mann= 3 , 0 , 0
       0      .1       0   73.96     .05       0   82.72      .1       0
Bank Sta=73.96,82.72
XS Rating Curve= 0 ,0
Exp/Cntr=0.3,0.1

Type RM Length L Ch R = 1 ,548.64  ,91.95,91.45,90.65
XS GIS Cut Line= 2
     610155.6326    4343217.7026     610069.0435    4343099.8843
#Sta/Elev= 30
       0  496.38    6.09  491.63   12.18  486.71   15.23  483.97   18.28  480.77
   24.37   475.8   30.46  472.97   36.55  468.37    39.6  466.26   42.65  464.78
   45.69  464.16   48.74  463.96   73.11  463.07    79.2  462.77   82.25  462.97
   88.34  464.67   91.38  465.33   94.43   466.2   97.48  466.76  100.52  468.53
  103.57  470.48  106.62  473.05  109.66  475.38  124.89  485.07  127.94  486.97
  130.98  487.79  134.03  489.53  137.08  491.69  143.17   495.5  146.21  497.75
#Mann= 3 , 0 , 0
       0      .1       0   73.11     .05       0   82.25      .1       0
Bank Sta=73.11,82.25
XS Rating Curve= 0 ,0
Exp/Cntr=0.3,0.1

Type RM Length L Ch R = 1 ,457.1874,93.91,91.48,90.92
XS GIS Cut Line= 2
     610207.6883    4343128.3298     610102.5691     4343021.967
#Sta/Elev= 30
       0  495.57    3.05  494.08   15.26  485.68   18.31   482.1   24.42  475.61
   27.47  471.96   30.52  468.49   36.62   462.6   39.67  460.95   42.73  460.27
   45.78  460.33   48.83  461.07   51.88  461.43   54.93  461.48   70.19  463.47
   73.25  463.95    76.3  464.89   79.35  465.58    82.4  466.67   91.56  470.44
   94.61  472.39   97.66  474.06  109.87  478.82  115.97  480.64  119.02  481.97
  122.08  483.89  125.13  485.06  140.39  489.98  143.44   491.3  149.54  494.49
#Mann= 3 , 0 , 0
       0      .1       0   39.67     .05       0   48.83      .1       0
Bank Sta=39.67,48.83
XS Rating Curve= 0 ,0
Exp/Cntr=0.3,0.1

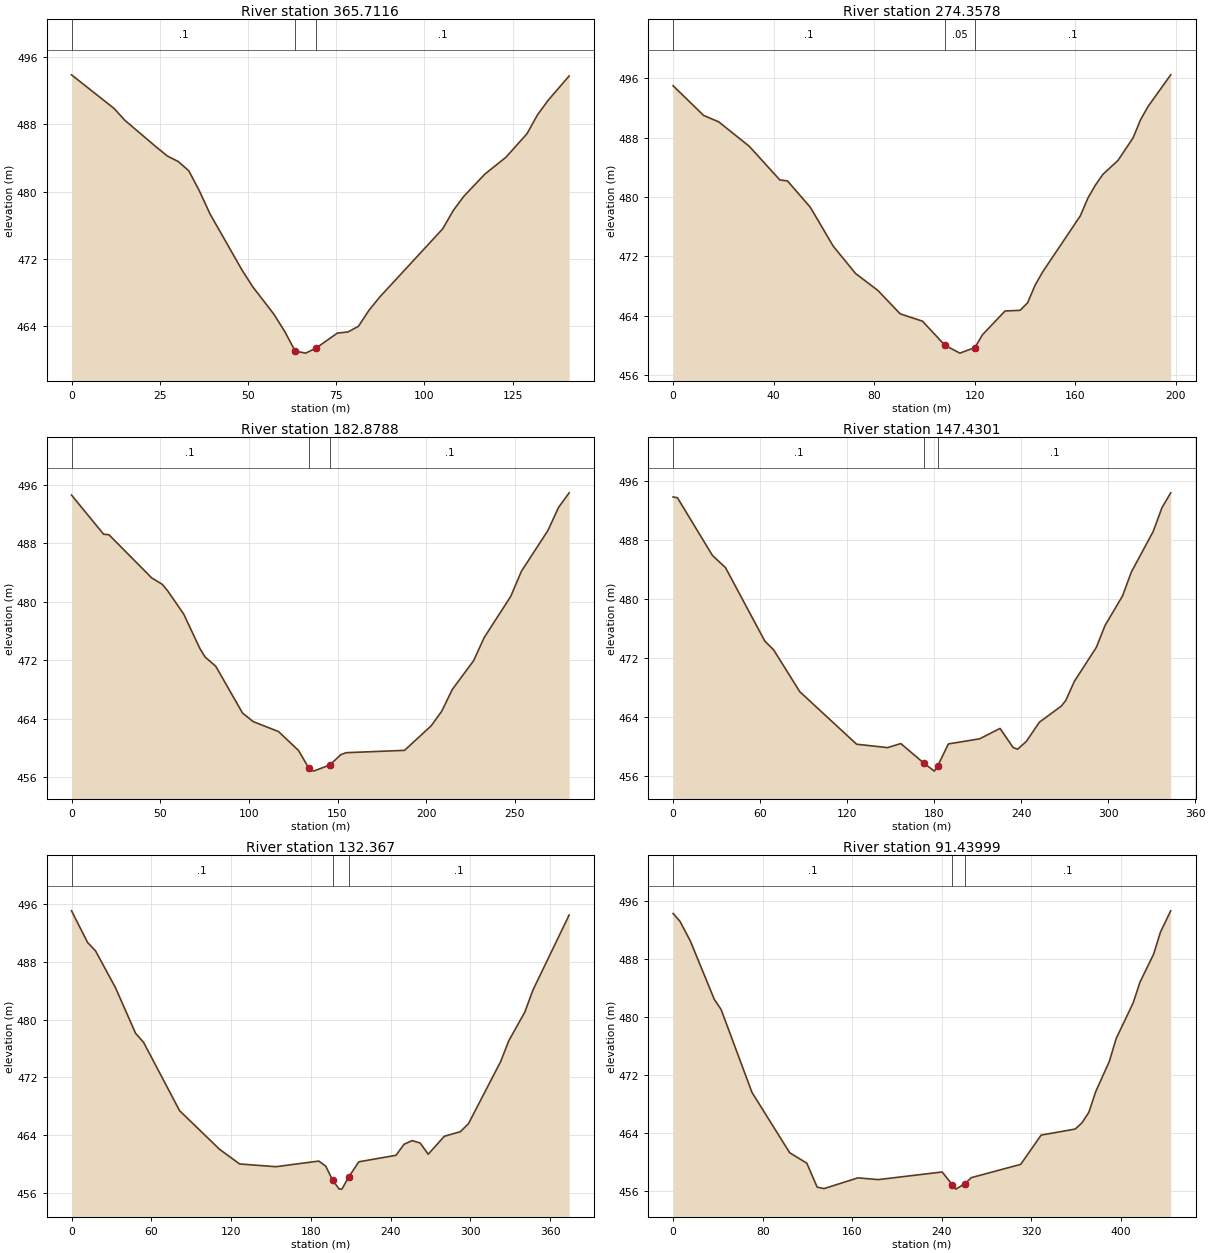
Type RM Length L Ch R = 1 ,365.7116,91.91,91.35,89.96
XS GIS Cut Line= 3
     610276.3479    4343048.4882     610225.3866    4343016.0629
     610161.4037    4342967.0306
#Sta/Elev= 30
       0  493.92   12.08   489.9    15.1   488.5   24.16  485.26   27.18  484.23
    30.2  483.59   33.22  482.48   36.24  480.07   39.26  477.32   48.32  470.63
   51.34  468.65   57.38  465.35    60.4  463.32   63.39  460.96   66.37  460.73
   69.36  461.35   75.33  463.12   78.32  463.25    81.3  463.93   84.29  465.84
   87.27  467.39  105.19  475.56  108.17  477.74  111.16  479.43  117.13  482.08
   123.1  484.09  129.07   486.9  132.06  489.16  135.04  490.87  141.01  493.79
#Mann= 3 , 0 , 0
       0      .1       0   63.39     .05       0   69.36      .1       0
Bank Sta=63.39,69.36
XS Rating Curve= 0 ,0
Exp/Cntr=0.3,0.1

Type RM Length L Ch R = 1 ,274.3578,79.61,91.48,91.57
XS GIS Cut Line= 4
     610333.9124    4343035.8224     610321.8419    4342973.2796
     610286.1451    4342946.9429     610206.9122    4342904.5888
#Sta/Elev= 30
       0  494.98   12.13  490.99    18.2  490.11   30.33  486.82   42.46   482.3
    45.5  482.17    54.6  478.61    63.7  473.38   72.57  469.71   81.44  467.43
   90.31  464.28   99.19  463.29  108.06  460.06  114.05  458.99  120.04  459.74
  123.03  461.46  132.02  464.66  138.01  464.75     141  465.77  143.99  468.15
  146.99  469.93  161.96  477.47  164.96  479.85  167.95   481.6  170.95  483.06
  176.94  484.93  182.93  487.96  185.92  490.41  188.92   492.2   197.9  496.45
#Mann= 3 , 0 , 0
       0      .1       0  108.06     .05       0  120.04      .1       0
Bank Sta=108.06,120.04
XS Rating Curve= 0 ,0
Exp/Cntr=0.3,0.1

Type RM Length L Ch R = 1 ,182.8788,35.18,35.45,35.36
XS GIS Cut Line= 6
     610352.9624    4343036.8808     610368.7911    4342932.5976
     610353.6481    4342905.5364     610349.7699    4342900.4947
     610330.7374    4342866.4887     610233.3705    4342849.5554
#Sta/Elev= 30
       0  494.61   18.08  489.26    21.1  489.19    45.2  483.29   51.23   482.4
   54.25  481.51   63.29  478.33   72.33  473.66   75.34  472.47   81.37   471.2
   96.44  464.81  102.46  463.64  116.75  462.28  128.03  459.69  133.67  457.34
  136.49  456.87  145.71  457.72  151.84  459.12  154.84  459.39  187.81  459.71
  202.78  463.05  208.77  465.05  214.76  468.04  226.74  471.96  232.73  475.13
   247.7  480.76  253.69  484.18  268.67  489.77  274.66  492.92  280.65  494.92
#Mann= 3 , 0 , 0
       0      .1       0  133.67     .05       0  145.71      .1       0
Bank Sta=133.67,145.71
XS Rating Curve= 0 ,0
Exp/Cntr=0.3,0.1

Type RM Length L Ch R = 1 ,147.4301,16.36,15.06,11.46
XS GIS Cut Line= 6
     610374.1292    4343046.4058     610411.0049    4342922.1863
     610388.1511    4342897.6026     610374.9219    4342873.0625
     610352.6485    4342847.5706      610234.958    4342846.4862
#Sta/Elev= 30
       0  493.88    3.01  493.77   27.12  485.95   36.16  484.29   63.28  474.32
   69.31  473.15   87.39  467.46  126.56  460.34  147.89  459.88  157.04  460.43
  172.97  457.77  180.19  456.69   182.6  457.43  189.85  460.38  211.37  461.07
  225.47  462.48  234.53  459.89  237.54  459.66  243.58  460.71  252.63  463.33
  267.72  465.51  270.74  466.25  276.78  468.88  291.86  473.47   297.9  476.45
  309.97  480.46  316.01  483.69   331.1   489.2  337.13  492.42  343.17  494.44
#Mann= 3 , 0 , 0
       0      .1       0  172.97     .05       0   182.6      .1       0
Bank Sta=172.97,182.6
XS Rating Curve= 0 ,0
Exp/Cntr=0.3,0.1

Type RM Length L Ch R = 1 ,132.367 ,41.87,40.93,38.27
XS GIS Cut Line= 6
     610392.1209     4343058.914     610432.6516     4342939.193
     610401.8955    4342888.1872     610381.9202    4342866.1304
      610365.172    4342843.7134      610234.958    4342842.1206
#Sta/Elev= 30
       0  495.07   12.04  490.69   18.06  489.51    33.1  484.39   48.15  478.09
   54.17  476.84   81.25  467.36  111.35     462   126.4  459.97  153.73  459.59
  185.96  460.37  191.21  459.66  196.34  457.73  201.36  456.48  203.35  456.49
  208.34  458.11  216.05  460.27  244.03  461.17  250.09   462.7  256.15  463.21
  262.21  462.87  268.26  461.32  280.38  463.81  292.49  464.45  298.55  465.56
  322.77  474.18  328.83  477.04  340.94  481.04     347  484.07  374.26  494.49
#Mann= 3 , 0 , 0
       0      .1       0  196.34     .05       0  208.34      .1       0
Bank Sta=196.34,208.34
XS Rating Curve= 0 ,0
Exp/Cntr=0.3,0.1

Type RM Length L Ch R = 1 ,91.43999,20.04,91.44,16.72
XS GIS Cut Line= 6
     610411.9646    4343075.4505     610468.0585    4342949.5797
     610440.2772    4342872.8504     610430.7522    4342851.0222
     610399.0021    4342832.7659     610234.6935    4342837.9864
#Sta/Elev= 30
       0  494.26    6.12  493.19   15.31  490.51   36.75  482.46   42.87  481.05
   70.43  469.64  104.12  461.33  119.43  459.89  128.62   456.6  134.74  456.39
  165.01  457.87  183.14  457.63  240.25  458.68  249.35  456.93  252.41  456.32
  260.81  457.09  266.28   457.9   310.4  459.73  328.66  463.76   359.1  464.59
  365.19  465.46  371.28   466.9  377.37  469.73  389.55   473.9  395.64  477.04
  410.86  481.96  416.95  484.82  429.12  488.67  435.21   491.7  444.35  494.63
#Mann= 3 , 0 , 0
       0      .1       0  249.35     .05       0  260.81      .1       0
Bank Sta=249.35,260.81
XS Rating Curve= 0 ,0
Exp/Cntr=0.3,0.1

River Reach=Cheat River     ,1
Reach XY= 30
     610469.2423     4342777.681      610806.363    4342822.9049
     610859.7578    4342855.5957     610921.6704    4342936.5583
      610974.058    4343060.3836     610950.2455     4343263.584
     610972.4705    4343473.1344     610999.1372     4343534.758
     611248.6961    4343789.0475     611339.1838    4343920.8103
     611405.8589    4344106.5482     611532.2374    4344662.0545
      611582.652    4344778.4701     611760.9012    4345032.7973
     612001.5942      4345282.94     612333.4567    4345600.7376
     612401.2234    4345594.0386     612556.6101    4345659.8294
      612720.123    4345835.2485     613152.1124    4345897.2517
     613491.8381    4346000.4395     613596.0558    4346001.2742
     613726.3354    4345971.7738     613796.4501    4345998.2322
     613993.5651    4346188.7325     614095.4299    4346463.8998
     614079.5549    4346627.9418     614025.2492    4346762.5455
     613903.3362    4346981.2457     613683.3798    4347278.7747

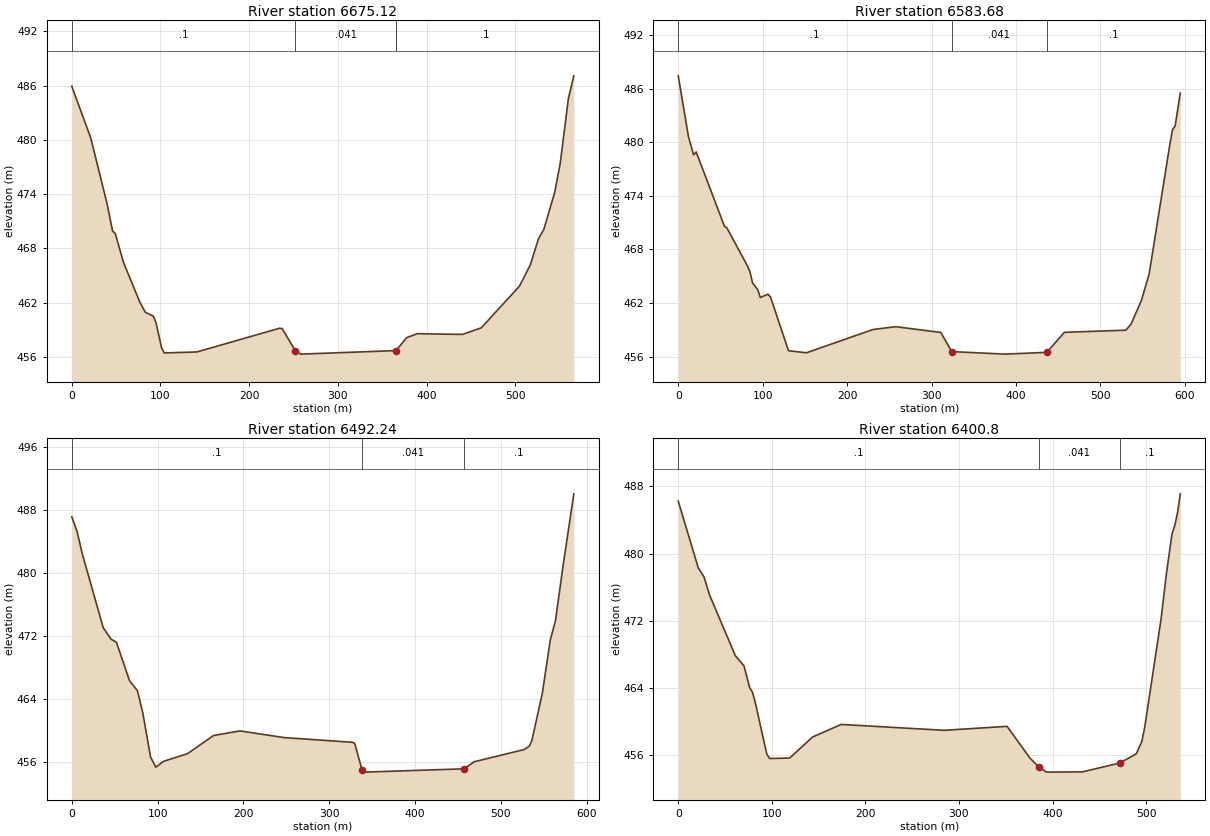
Type RM Length L Ch R = 1 ,6675.12 ,83.49,91.44,89.83
XS GIS Cut Line= 6
     610447.7657    4343079.3595     610510.7086     4342936.147
     610529.7586    4342863.9156     610531.8185    4342810.1998
     610547.2211    4342646.4277     610589.0947    4342537.6286
#Sta/Elev= 30
       0  485.94   21.47   480.2   39.88  472.91   46.01  469.93   49.08  469.64
   58.28  466.47   76.68  462.08   82.82  460.96   92.02  460.51   95.09  459.75
  101.22  457.03  104.29  456.45   141.1  456.56  234.12  459.18  237.11  459.15
  252.04   456.7  258.01  456.32  365.52  456.71  377.51  458.14   389.5  458.58
  440.45   458.5  461.71  459.23  504.66  463.83  516.93  466.18  526.14  469.07
  532.27  470.12  544.54  474.25  550.68  477.41  559.88  484.59  566.02  487.09
#Mann= 3 , 0 , 0
       0      .1       0  252.04    .041       0  365.52      .1       0
Bank Sta=252.04,365.52
XS Rating Curve= 0 ,0
Exp/Cntr=0.3,0.1

Type RM Length L Ch R = 1 ,6583.68 ,85.19,91.44,88.9
XS GIS Cut Line= 6
     610475.2489    4343138.9726     610593.7352     4342940.942
     610616.8016     4342867.229     610628.9129    4342771.0111
     610637.3915    4342664.7165     610661.4691     4342585.402
#Sta/Elev= 30
       0  487.44   12.15  480.61   18.22  478.59   21.26  478.92   54.66  470.61
   57.69   470.4   81.98  466.15   85.02  465.48   88.06  464.24   94.13  463.51
   97.17  462.62  106.28  462.99  109.31  462.67  130.57  456.66  151.82  456.43
  230.77  459.04  257.51  459.35  310.93  458.71  323.96  456.56  387.29  456.28
   436.5  456.48  457.34  458.72  530.16  458.96   536.3  459.64  548.58  462.29
  557.79  465.28  582.35  479.83  585.42  481.41  588.49  481.82  594.63  485.51
#Mann= 3 , 0 , 0
       0      .1       0  323.96    .041       0   436.5      .1       0
Bank Sta=323.96,436.5
XS Rating Curve= 0 ,0
Exp/Cntr=0.3,0.1

Type RM Length L Ch R = 1 ,6492.24 ,78.77,91.44,132.09
XS GIS Cut Line= 6
     610525.6872    4343146.4572      610678.402    4342955.1634
     610711.0838     4342855.431     610721.2768    4342763.5474
     610718.6188    4342733.9713     610722.9212    4342621.0519
#Sta/Elev= 30
       0  487.14    6.12  485.31   12.24  482.44   36.72  473.04    45.9   471.6
   52.01  471.22   67.31  466.33   76.49  465.07   82.61  462.32   91.79  456.65
   97.91  455.36  107.09  456.11  134.63  457.06  165.22  459.38  195.82  459.96
  247.83  459.11  326.71  458.52  329.59  458.38  338.22  454.98   341.1  454.73
  457.03  455.15  468.91  456.05  526.85  457.59  532.96  458.03  536.01  458.74
  548.23  464.77  557.39  471.49   563.5  473.96  572.66  481.19  584.88  490.06
#Mann= 3 , 0 , 0
       0      .1       0  338.22    .041       0  457.03      .1       0
Bank Sta=338.22,457.03
XS Rating Curve= 0 ,0
Exp/Cntr=0.3,0.1

Type RM Length L Ch R = 1 ,6400.8  ,23.21,91.44,108.51
XS GIS Cut Line= 6
     610550.0227    4343160.4666     610759.4548    4342959.6496
      610790.321    4342869.8351     610791.5558    4342847.7181
     610826.8166    4342790.1256     610865.1449    4342741.7702
#Sta/Elev= 30
       0  486.25   21.38  478.31   27.49  477.24    33.6  475.04   61.09  467.83
   70.25  466.64   76.36  464.03   79.41  463.48   82.46   462.2   94.68  456.11
   97.74   455.6  119.12  455.66  143.55  458.16  174.09  459.66  284.05  458.96
  351.43  459.43  375.93  455.64  385.12  454.63  393.43  453.98  431.83  454.01
  471.74  455.06   489.5  456.16  495.37  457.63  498.31  459.21  515.94  472.19
  521.82  477.75  527.69  482.38  530.63  483.33  533.57  484.89  536.51  487.12
#Mann= 3 , 0 , 0
       0      .1       0  385.12    .041       0  471.74      .1       0
Bank Sta=385.12,471.74
XS Rating Curve= 0 ,0
Exp/Cntr=0.3,0.1