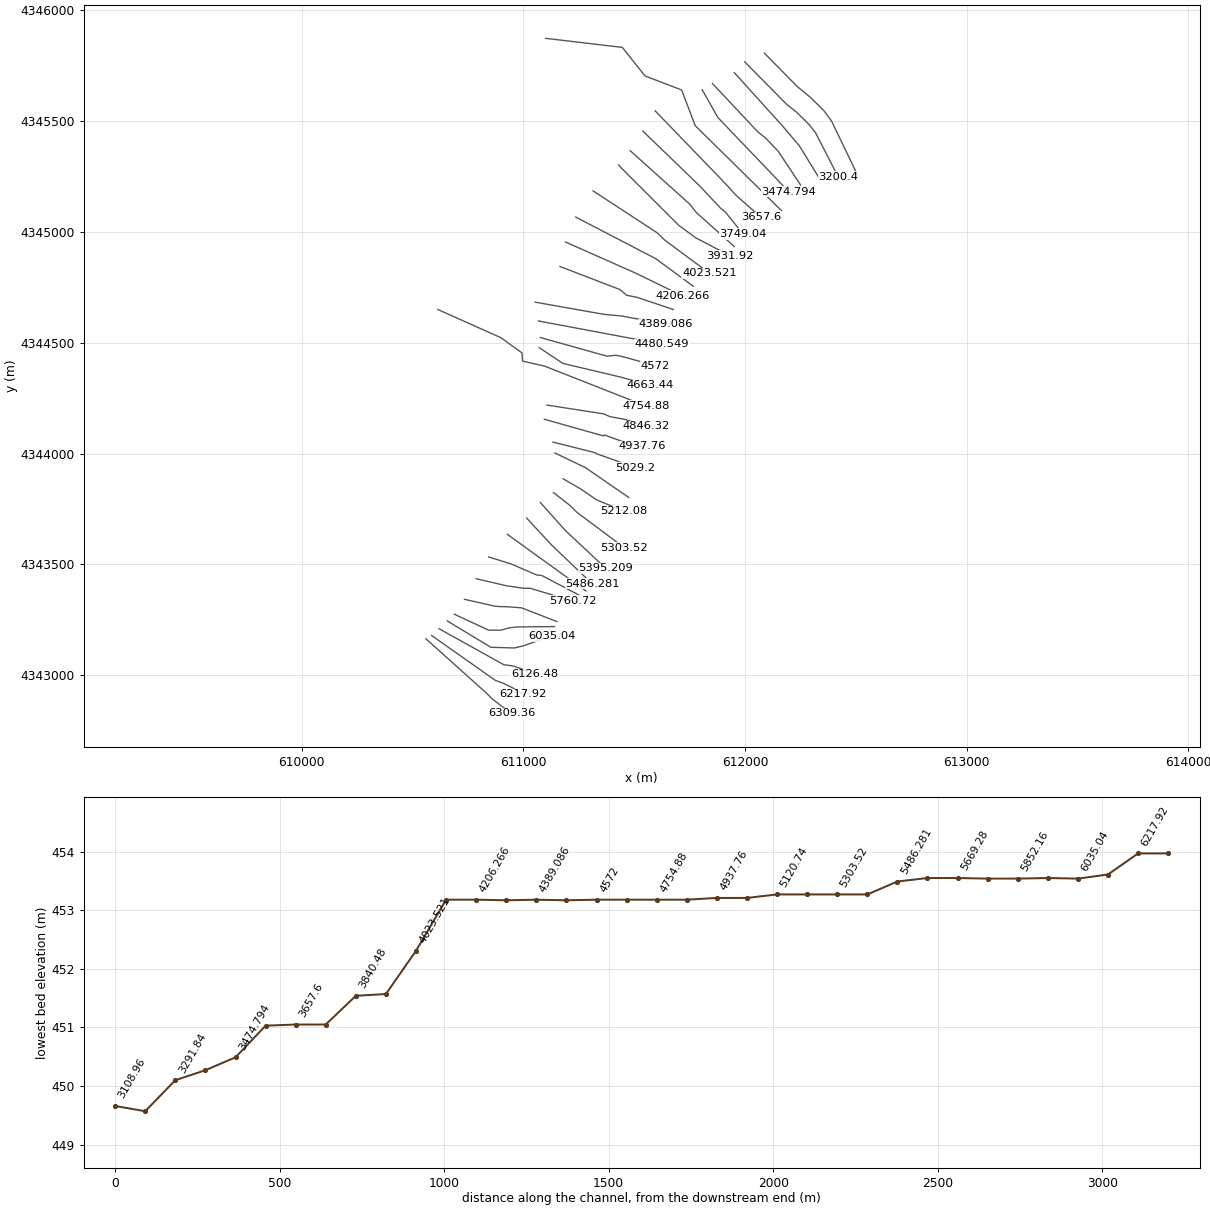
HEC-RAS study CheatRiver.prj: CheatRiver

--- CheatRiver.g01 (geometry) --- (continued)

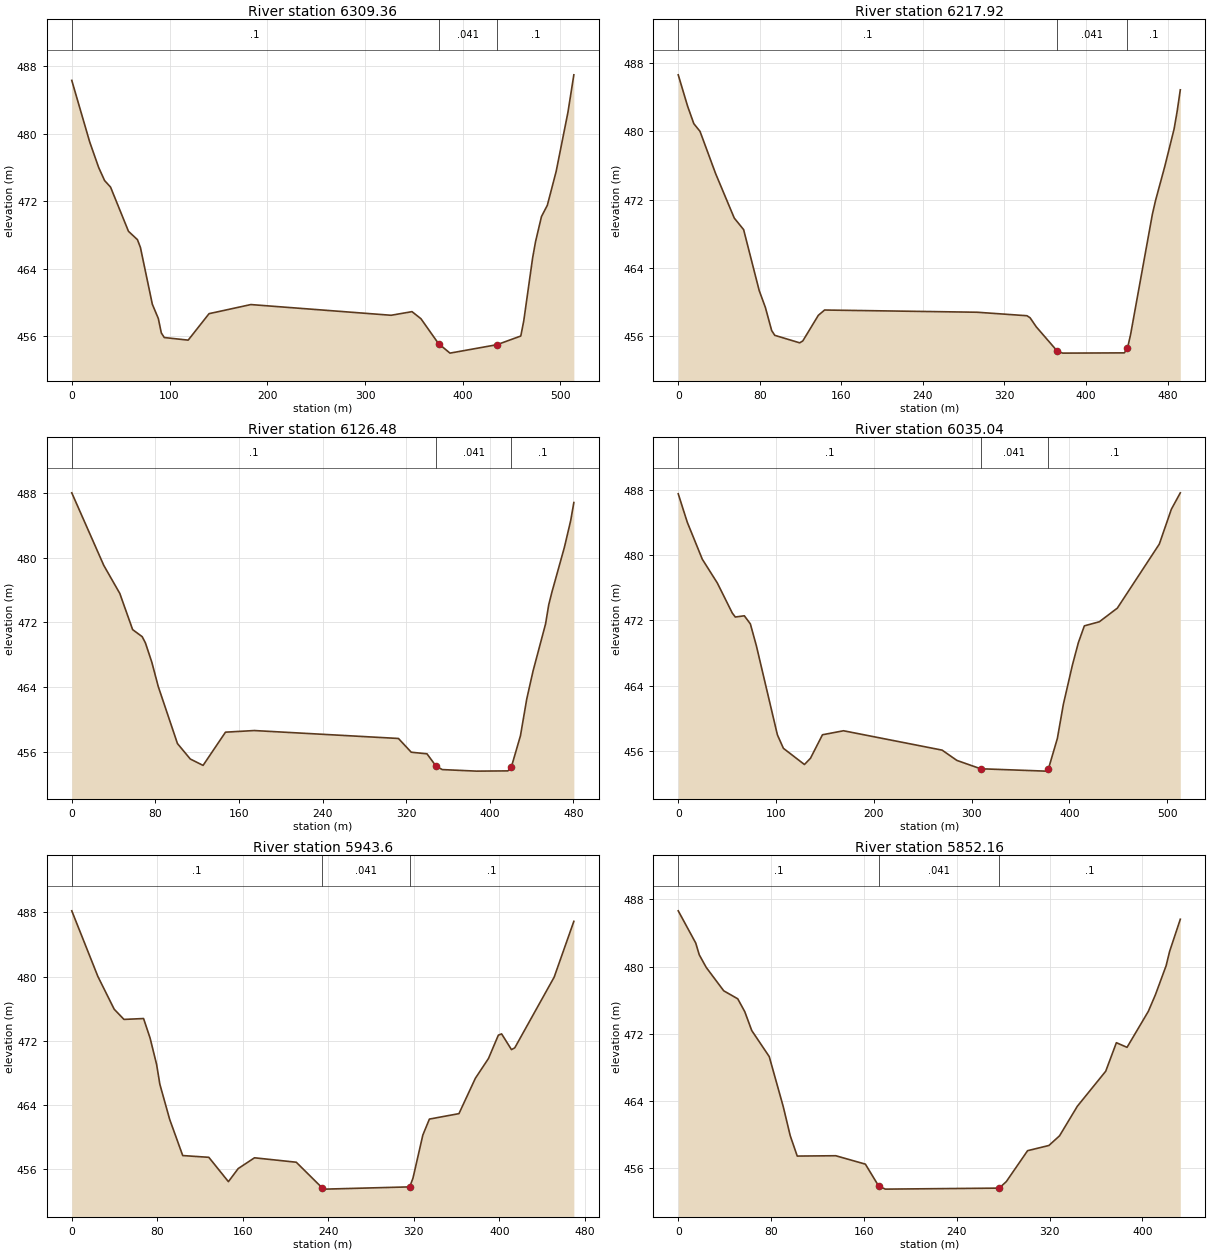
Type RM Length L Ch R = 1 ,6309.36 ,61.95,91.44,96.79
XS GIS Cut Line= 5
     610559.9031    4343164.1806     610832.6544    4342919.4887
     610859.5411     4342892.471      610905.551    4342857.2869
     610947.2259    4342827.5186
#Sta/Elev= 30
       0  486.32   18.32  479.03   27.48     476   33.59  474.44    39.7  473.66
   58.02  468.42   67.18  467.43   70.23  466.51   82.45  459.76   88.55  458.08
   91.61  456.37   94.66  455.82  119.09  455.51  140.46  458.65  183.21  459.73
  326.73  458.46   348.1  458.89  357.26  458.05  375.22   455.1  386.95  453.97
  435.03  454.97  459.41     456  462.46  457.81   471.5  465.26  474.51   467.2
  480.54  470.16  486.56  471.51   495.6  475.53  507.65  482.54  513.68  486.98
#Mann= 3 , 0 , 0
       0      .1       0  375.22    .041       0  435.03      .1       0
Bank Sta=375.22,435.03
XS Rating Curve= 0 ,0
Exp/Cntr=0.3,0.1

Type RM Length L Ch R = 1 ,6217.92 ,73.66,91.44,97.95
XS GIS Cut Line= 5
     610585.8182    4343179.0564     610872.8712     4342976.705
     610911.3629    4342962.3887     610949.3026    4342943.8404
     610998.4431    4342913.1423
#Sta/Elev= 30
       0  486.64    9.16  482.97   15.27  480.91   21.38     480   36.65  475.05
   54.97  469.82   64.13  468.47    79.4  461.32   85.51  459.32   91.62  456.63
   94.67  456.06   119.1  455.18  122.16   455.4  137.43  458.41  143.54  459.03
  293.18  458.77  342.04  458.36   345.1  458.12  351.21  457.05  371.74  454.21
  377.11  453.97  437.55     454   440.6  454.53  443.65  456.13     465  470.24
  468.05  471.84   477.2  475.88  486.35  480.28   489.4  482.39  492.45  484.88
#Mann= 3 , 0 , 0
       0      .1       0  371.74    .041       0   440.6      .1       0
Bank Sta=371.74,440.6
XS Rating Curve= 0 ,0
Exp/Cntr=0.3,0.1

Type RM Length L Ch R = 1 ,6126.48 ,54.1,91.44,130.85
XS GIS Cut Line= 5
     610619.4713    4343209.5125     610911.4508    4343047.1504
     610952.2339    4343041.7056     610986.5239    4343030.2756
     611050.1039    4343003.1631
#Sta/Elev= 30
       0  488.04   30.65  479.06   45.98  475.59   58.24  471.12   67.43  470.24
    70.5  469.47   76.63  467.08   82.76  464.08  101.15  457.02  113.41  455.11
  125.67  454.32  147.12  458.43  174.71  458.63  312.63  457.65  324.89  455.95
  339.96  455.75  348.78   454.2  354.66   453.8  387.28  453.61  417.39  453.64
  420.61  454.08  429.41  457.99  435.42  462.53  441.43  465.98  453.45  471.83
  456.45  474.18  459.46  475.73  471.48  481.31  477.49  484.61   480.5  486.84
#Mann= 3 , 0 , 0
       0      .1       0  348.78    .041       0  420.61      .1       0
Bank Sta=348.78,420.61
XS Rating Curve= 0 ,0
Exp/Cntr=0.3,0.1

Type RM Length L Ch R = 1 ,6035.04 ,78.09,91.44,84.87
XS GIS Cut Line= 5
     610656.1813    4343244.8511     610853.4077    4343125.7318
     610959.3285    4343122.7185     611000.2332    4343132.4248
     611127.5427    4343176.9955
#Sta/Elev= 30
       0  487.48    9.22  484.01   24.58  479.48   39.94  476.57    55.3  472.88
   58.37   472.4   67.59  472.55   73.73  471.56   79.87  468.89  101.38  457.98
  107.52  456.33  129.03  454.35  135.17  455.11  147.46  457.99  168.97  458.48
  269.77  456.11   284.9  454.85  309.12  453.83  375.41  453.54  378.41  453.79
  387.61  457.54  393.74  461.72  402.94   466.5  409.07  469.26   415.2  471.32
  430.53  471.82  448.92  473.49  491.84  481.33   504.1  485.58   513.3   487.6
#Mann= 3 , 0 , 0
       0      .1       0  309.12    .041       0  378.41      .1       0
Bank Sta=309.12,378.41
XS Rating Curve= 0 ,0
Exp/Cntr=0.3,0.1

Type RM Length L Ch R = 1 ,5943.6  ,107.51,91.44,81.12
XS GIS Cut Line= 6
     610688.4584    4343274.8096     610843.6315    4343202.9729
     610897.7255    4343202.9903     610935.8329    4343213.5102
     610971.8299    4343217.6241     611140.7719     4343219.329
#Sta/Elev= 30
       0   488.2   24.43  480.03    39.7  475.95   48.86  474.68   67.18  474.79
   73.28  472.36   79.39  469.07   82.44   466.6    91.6  462.24  103.82  457.73
  128.25  457.51  146.57  454.48  155.73  456.11  170.99  457.45  210.06   456.9
  234.21  453.72  237.25  453.55  316.21  453.83  319.28  454.92   328.5  460.28
  334.64  462.27  362.29  462.95  377.65  467.35  389.94  469.82  399.15  472.72
  402.22  472.88  411.44  470.92  414.51  471.14  451.37  479.94   469.8  486.89
#Mann= 3 , 0 , 0
       0      .1       0  234.21    .041       0  316.21      .1       0
Bank Sta=234.21,316.21
XS Rating Curve= 0 ,0
Exp/Cntr=0.3,0.1

Type RM Length L Ch R = 1 ,5852.16 ,100.19,91.44,97.79
XS GIS Cut Line= 6
     610734.0822    4343342.2555     610872.3671    4343311.1504
     610894.5946     4343309.353     610929.1942    4343308.6822
     610991.5871    4343303.8205     611151.3553    4343241.8186
#Sta/Elev= 30
       0  486.63   15.08   482.8   18.09  481.41   24.13   479.9    39.2  477.12
   51.27  476.17    57.3  474.65   63.33   472.4   78.41   469.3   90.47  463.36
    96.5  459.89  102.54  457.47  135.71  457.51  161.25  456.51  172.69  453.91
  178.46  453.54  276.53  453.66  282.65  454.43  301.01  458.11  319.37  458.73
  328.55  459.88  343.86  463.39  368.34  467.56  377.52  470.95   386.7   470.4
  405.06  474.68  411.18  476.66  420.36   480.1  423.42  481.82   432.6  485.63
#Mann= 3 , 0 , 0
       0      .1       0  172.69    .041       0  276.53      .1       0
Bank Sta=172.69,276.53
XS Rating Curve= 0 ,0
Exp/Cntr=0.3,0.1

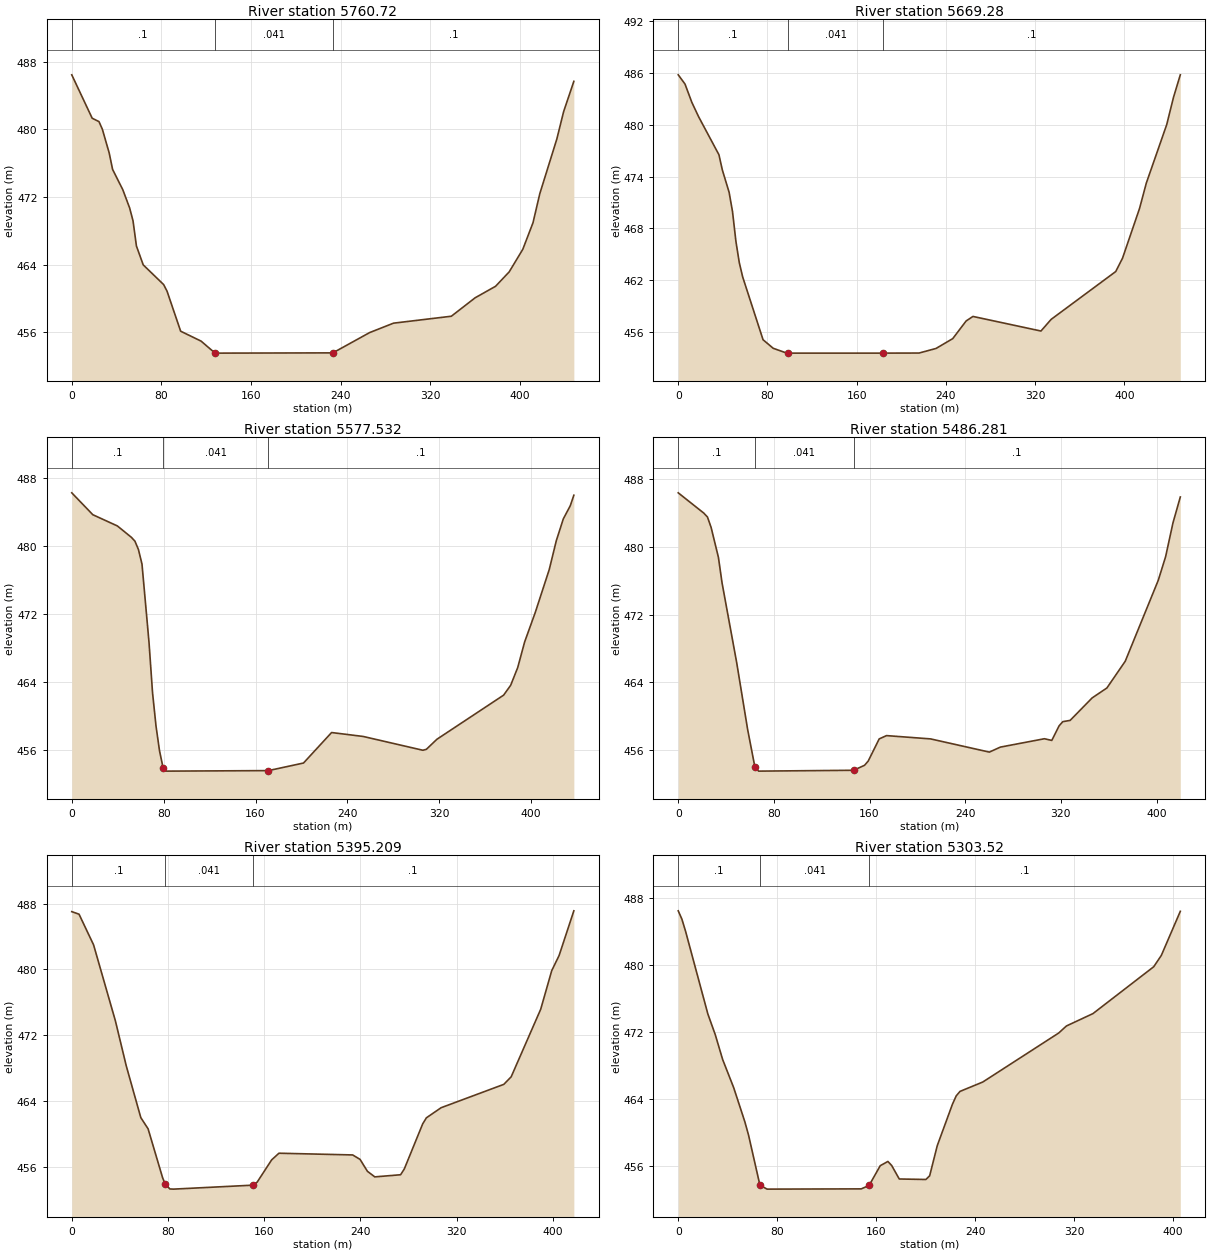
Type RM Length L Ch R = 1 ,5760.72 ,102.27,91.44,70.17
XS GIS Cut Line= 5
     610787.6244    4343435.0844     610923.6865    4343403.3565
     611001.5584    4343392.0297     611030.8222    4343392.1016
     611222.7929    4343334.4229
#Sta/Elev= 30
       0  486.43   18.22   481.3    24.3   480.9   27.33  479.99   33.41  477.19
   36.45  475.25   45.56  472.85   51.63   470.7   54.67  469.18   57.71   466.2
   63.78  463.97   82.01  461.64   85.04  460.86   97.19  456.13  115.41  454.96
  127.56  453.58   130.6  453.54  233.04  453.57  265.89  455.97  287.15  457.08
  338.78   457.9  360.04  460.08  378.26  461.44  390.41  463.14  402.56  465.81
  411.67  468.95  417.75  472.39  432.93  478.84     439  482.08  448.12  485.66
#Mann= 3 , 0 , 0
       0      .1       0  127.56    .041       0  233.04      .1       0
Bank Sta=127.56,233.04
XS Rating Curve= 0 ,0
Exp/Cntr=0.3,0.1

Type RM Length L Ch R = 1 ,5669.28 ,105.4,91.75,69.97
XS GIS Cut Line= 5
     610843.1828    4343533.5893     610944.7957    4343501.8542
     611059.2045    4343452.3455     611083.0445    4343449.7809
     611255.6013     4343358.897
#Sta/Elev= 30
       0  485.79    6.08  484.72   12.17  482.61   18.25  480.94    36.5  476.53
   39.54  474.77   45.62  472.18   48.66  469.95   51.71   466.5   54.75  464.02
   57.79  462.37   76.04   455.1   85.16  454.11   97.33  453.55   98.58  453.55
  183.59  453.55  215.91  453.56  231.11  454.09   246.1  455.23  258.14  457.28
  264.23   457.8  325.18  456.11  334.32  457.46  392.22     463  398.32  464.55
  413.55   470.3  419.65  473.25  437.93  480.02  444.03  483.19  450.12  485.79
#Mann= 3 , 0 , 0
       0      .1       0   98.58    .041       0  183.59      .1       0
Bank Sta=98.58,183.59
XS Rating Curve= 0 ,0
Exp/Cntr=0.3,0.1

Type RM Length L Ch R = 1 ,5577.532,100.31,91.25,75.06
XS GIS Cut Line= 2
     610927.4808    4343635.6904     611282.0597    4343380.0637
#Sta/Elev= 30
       0  486.22   18.34  483.65   39.74  482.33   51.96  480.99   55.02  480.54
   58.08  479.55   61.14  477.85   67.25  468.67   70.31  462.78   73.36  458.82
   76.42  455.92   79.48  453.96   82.53  453.55  171.18  453.61  201.75   454.5
   226.2  458.08  253.71  457.62  305.68     456  308.73  456.11   317.9  457.29
  375.98  462.47   382.1  463.62  388.21  465.69  394.32  468.73  403.49  472.16
  415.72  477.22  421.83  480.59  427.95  483.16  434.06  484.72  437.12  485.94
#Mann= 3 , 0 , 0
       0      .1       0   79.48    .041       0  171.18      .1       0
Bank Sta=79.48,171.18
XS Rating Curve= 0 ,0
Exp/Cntr=0.3,0.1

Type RM Length L Ch R = 1 ,5486.281,92.03,91.07,90.3
XS GIS Cut Line= 3
     611014.6624     4343708.869     611126.7856    4343587.8236
     611311.1639    4343411.8137
#Sta/Elev= 30
       0   486.4   21.39     484   24.44  483.54    27.5  482.31   33.61  478.77
   36.67  475.73   48.89  466.32   58.05  458.41   64.17  453.94   67.22  453.49
  146.66  453.59  155.83  454.18  158.88  454.68  168.07   457.3  174.21  457.69
  211.06   457.3   260.2  455.74  269.41  456.33  306.27  457.32  312.41  457.12
  318.55  458.85  321.62  459.34  327.76  459.49  346.19  462.15  358.48  463.32
  373.83  466.48  401.47  476.06  407.61  478.85  413.75  482.84   419.9  485.91
#Mann= 3 , 0 , 0
       0      .1       0   64.17    .041       0  146.66      .1       0
Bank Sta=64.17,146.66
XS Rating Curve= 0 ,0
Exp/Cntr=0.3,0.1

Type RM Length L Ch R = 1 ,5395.209,85.59,91.69,99.49
XS GIS Cut Line= 3
     611076.8087    4343779.0448     611189.3023     4343652.675
     611370.6953    4343483.2514
#Sta/Elev= 30
       0  487.04    6.04  486.73   18.13     483   36.25  473.76   45.32  468.26
    57.4  461.97   63.45  460.61   75.53  454.65   77.64  453.89   81.57  453.29
   84.59  453.27  150.25  453.75  154.08  454.11  166.17  456.83  172.25  457.64
  233.54  457.43  239.67  456.89  245.79  455.44  251.92  454.76  273.37  455.02
  276.44  455.72  291.76  461.22  294.82  461.95  307.08  463.18  359.17  466.02
   365.3  466.94  389.82  475.15  399.01  479.86  405.14   481.7   417.4  487.14
#Mann= 3 , 0 , 0
       0      .1       0   77.64    .041       0  150.25      .1       0
Bank Sta=77.64,150.25
XS Rating Curve= 0 ,0
Exp/Cntr=0.3,0.1

Type RM Length L Ch R = 1 ,5303.52 ,84.68,91.44,108.42
XS GIS Cut Line= 4
     611135.6284    4343823.8926     611209.0166    4343767.0553
     611241.7452    4343734.7177     611455.8582    4343574.8635
#Sta/Elev= 30
       0  486.47    2.99  485.47    5.99     484   23.95  474.17   29.94   471.7
   35.93  468.73   44.91  465.35    53.9  461.29   56.89   459.7   66.06  453.74
   71.86  453.27  148.05   453.3   154.4  453.72   163.4  456.07  169.55  456.57
  172.62  456.09  178.76  454.48  200.26  454.42  203.33  454.86  209.47  458.45
  221.76   463.4  224.83   464.4   227.9  464.93  246.33  466.05  307.76   471.9
   313.9  472.73   335.4  474.21  384.54   479.8  390.68  481.15  406.04  486.41
#Mann= 3 , 0 , 0
       0      .1       0   66.06    .041       0   154.4      .1       0
Bank Sta=66.06,154.4
XS Rating Curve= 0 ,0
Exp/Cntr=0.3,0.1

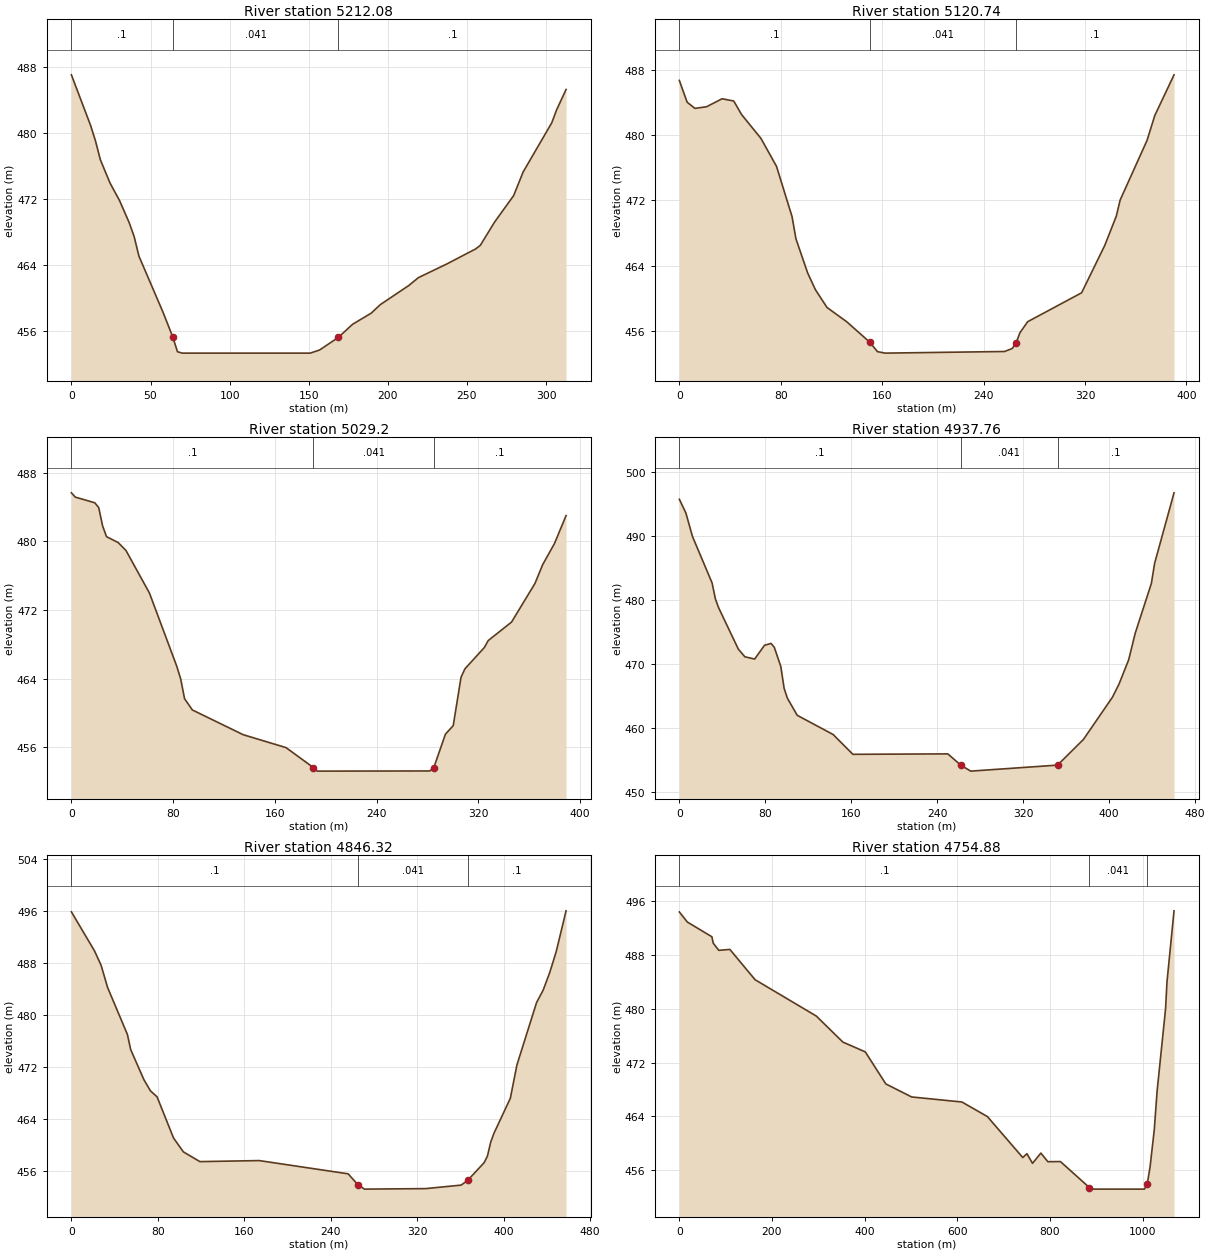
Type RM Length L Ch R = 1 ,5212.08 ,93.52,91.34,90.59
XS GIS Cut Line= 5
     611179.2153    4343886.3392     611258.3423    4343840.5398
     611329.4809    4343791.6855     611351.0666    4343782.3853
     611454.2543    4343740.3165
#Sta/Elev= 30
       0  487.05   12.19  480.88   15.24  479.02   18.29  476.75   24.38  473.93
   30.48  471.77   36.57  469.09   39.62  467.45   42.67  465.05    57.9  458.24
      64  455.27   67.05  453.44   70.09  453.27  150.94  453.27  156.89  453.65
   168.8  455.19  177.72  456.77  189.48  458.12  195.35  459.17  213.28  461.48
   219.3  462.43  237.37   464.1  255.44  465.91  258.45  466.35  267.49  469.18
  279.53  472.39  285.56  475.27  303.63  481.23  306.64  482.78  312.66  485.27
#Mann= 3 , 0 , 0
       0      .1       0      64    .041       0   168.8      .1       0
Bank Sta=64,168.8
XS Rating Curve= 0 ,0
Exp/Cntr=0.3,0.1

Type RM Length L Ch R = 1 ,5120.74 ,76.05,91.54,108.87
XS GIS Cut Line= 3
     611142.2039    4344002.7841     611280.3382    4343936.3603
     611475.4374    4343801.8765
#Sta/Elev= 30
       0  486.67    6.13  484.01   12.26  483.25   21.46  483.45   33.72  484.43
   42.92  484.15   49.05   482.5   64.38  479.57   76.64  476.15    88.9  469.99
   91.96  467.28  101.16  463.11  107.29  461.05  116.49  458.86  131.82  457.14
  150.21  454.61  156.31  453.45  162.39  453.27  256.56  453.47  262.64  453.84
  265.68  454.55  268.72  455.78  274.79  457.12  317.32  460.66  335.55  466.45
  344.67  470.04   347.7  472.01  368.97  479.34  375.04  482.37  390.23  487.36
#Mann= 3 , 0 , 0
       0      .1       0  150.21    .041       0  265.68      .1       0
Bank Sta=150.21,265.68
XS Rating Curve= 0 ,0
Exp/Cntr=0.3,0.1

Type RM Length L Ch R = 1 ,5029.2  ,83.75,91.44,91.86
XS GIS Cut Line= 4
     611133.1854    4344051.7943     611317.7189    4344005.6092
     611337.1359    4343996.9235     611504.1473    4343936.9707
#Sta/Elev= 30
       0  485.65    3.07  485.15   18.41  484.49   21.48  483.93   24.55  481.79
   27.61  480.54   36.82  479.85   42.95  478.92   61.36  473.97   82.84  465.44
   85.91  463.97   88.98  461.65   95.11  460.34     135  457.46  168.75  455.95
  190.23  453.63  193.26  453.21  281.86  453.23  284.92  453.61   294.1  457.52
  300.22  458.51  306.34  464.14   309.4  465.13  324.69  467.62  327.75  468.43
  346.11  470.59  364.47  475.08  370.59  477.29  379.76  479.72  388.94  482.99
#Mann= 3 , 0 , 0
       0      .1       0  190.23    .041       0  284.92      .1       0
Bank Sta=190.23,284.92
XS Rating Curve= 0 ,0
Exp/Cntr=0.3,0.1

Type RM Length L Ch R = 1 ,4937.76 ,93.81,91.44,97.78
XS GIS Cut Line= 6
     611094.4326    4344154.9997      611361.306    4344079.7776
     611365.0579    4344083.6353     611373.6892     4344080.955
     611444.6165    4344055.4939     611534.9688    4344032.0644
#Sta/Elev= 30
       0  495.76    6.09  493.61   12.19  489.95   30.47  482.66   33.52  480.17
   36.56  478.78   54.84  472.32   60.94  471.11   70.08  470.75   79.22   472.9
   85.31   473.2   88.36  472.59   94.46  469.57    97.5  466.17  100.55  464.62
  109.69  461.95  143.21  458.93  161.49  455.84  249.85  455.91  262.04  454.13
  271.18  453.21  351.98  454.15  376.08  458.17  403.18  464.81   409.2  466.83
  418.24  470.67  424.26  474.79  439.31  482.59  442.32  485.73  460.39  496.77
#Mann= 3 , 0 , 0
       0      .1       0  262.04    .041       0  351.98      .1       0
Bank Sta=262.04,351.98
XS Rating Curve= 0 ,0
Exp/Cntr=0.3,0.1

Type RM Length L Ch R = 1 ,4846.32 ,98.47,91.44,86.39
XS GIS Cut Line= 5
     611106.5292    4344218.9218     611362.5848    4344179.1068
     611390.3114    4344166.9073     611457.3756    4344154.3926
     611552.5372    4344123.3812
#Sta/Elev= 30
       0  495.92   21.34  489.92   27.44  487.71   33.53  484.25   51.83  477.02
   54.88  474.68   67.07  470.06   73.17  468.33   79.26  467.41   94.51  461.06
  103.65  458.92   118.9  457.42  173.77  457.58  256.08  455.54  265.19  453.85
  271.25  453.18  327.98  453.26  360.68   453.8  366.75  454.54  381.91  457.26
  384.94  458.26  387.98  460.41  391.01  461.79  406.17  467.19  412.24  472.31
  430.44  481.94   436.5  483.84  442.57  486.54  448.63   489.8  457.73  496.08
#Mann= 3 , 0 , 0
       0      .1       0  265.19    .041       0  366.75      .1       0
Bank Sta=265.19,366.75
XS Rating Curve= 0 ,0
Exp/Cntr=0.3,0.1

Type RM Length L Ch R = 1 ,4754.88 ,89,91.44,93.88
XS GIS Cut Line= 6
      610614.217    4344650.1147       610898.38    4344523.1145
     610993.6302    4344454.3227     610996.2761    4344417.2809
      611095.495    4344394.7913     611553.0558    4344214.5357
#Sta/Elev= 30
       0  494.41   17.26  492.91   70.24  490.72   73.22  489.76   85.16   488.7
  109.04  488.84  163.55  484.33  295.58  478.93  353.16  475.05  401.37   473.6
  445.78  468.83  501.54  466.89  610.12  466.14  665.16  463.97  741.39  457.88
  750.43  458.45  762.48  457.02  780.56  458.54  795.62  457.26  822.74  457.28
  885.24  453.42  894.38  453.18 1004.06  453.18 1010.15  453.92 1016.24  456.44
 1025.38     462 1031.48  467.75 1049.76  479.99  1052.8  483.98 1068.04  494.58
#Mann= 3 , 0 , 0
       0      .1       0  885.24    .041       0 1010.15      .1       0
Bank Sta=885.24,1010.15
XS Rating Curve= 0 ,0
Exp/Cntr=0.3,0.1

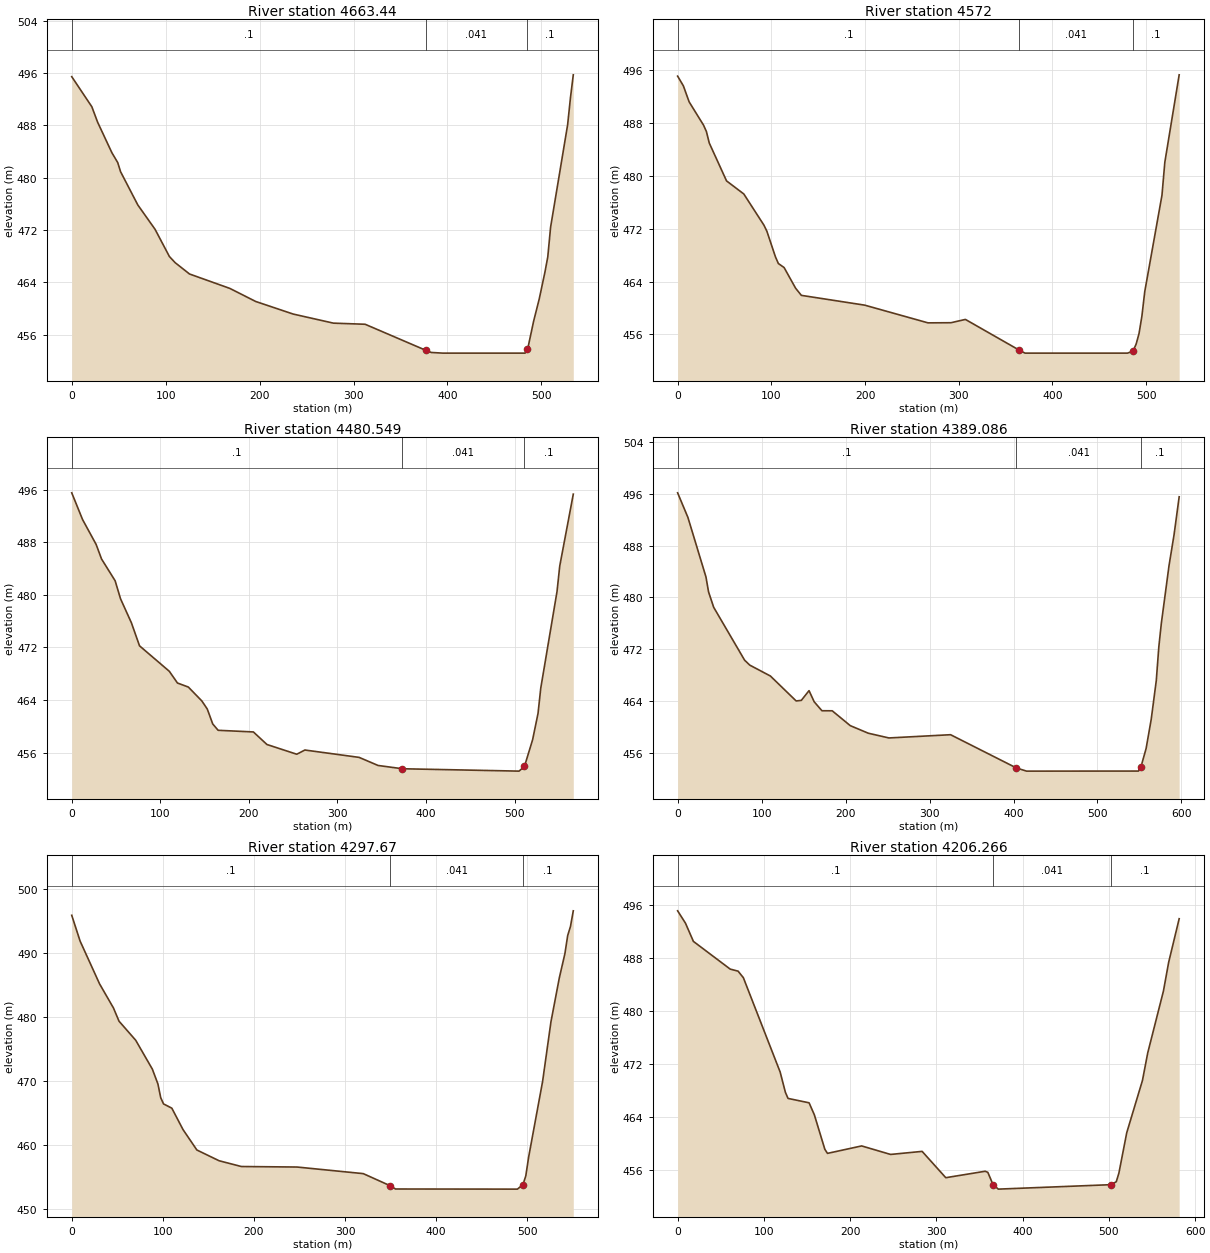
Type RM Length L Ch R = 1 ,4663.44 ,86.25,91.44,91.59
XS GIS Cut Line= 4
     611071.1407    4344478.3448     611177.9548    4344406.9884
     611440.4551    4344344.9101     611571.2231    4344308.2554
#Sta/Elev= 30
       0  495.42   21.41  490.82   27.53  488.47   42.82  483.78   48.94   482.3
   51.99   480.9   70.35  475.82    88.7   472.1  103.99  467.94  110.11     467
   125.4  465.27   168.3  463.07  195.89  461.07  235.74  459.15  278.65  457.76
  312.37  457.59  376.84  453.62  382.87  453.28  395.13  453.18   482.7  453.18
  484.81  453.74  485.72  453.99  491.75  458.04  497.79  461.48  503.83  465.56
  506.84  467.87  509.86  472.43  527.97  488.05  530.99  492.19  534.01   495.7
#Mann= 3 , 0 , 0
       0      .1       0  376.84    .041       0  484.81      .1       0
Bank Sta=376.84,484.81
XS Rating Curve= 0 ,0
Exp/Cntr=0.3,0.1

Type RM Length L Ch R = 1 ,4572    ,94.82,91.45,97.72
XS GIS Cut Line= 5
     611076.2224     4344523.912     611377.8756    4344439.4463
     611417.3767    4344443.8891     611457.8575    4344434.9964
     611593.4394    4344396.9924
#Sta/Elev= 30
       0  495.09    6.14  493.62   12.28   491.2   27.64  487.68   30.71  486.71
   33.78  484.97   52.21  479.24   70.64  477.26   92.13  472.54   95.21  471.64
  104.42  467.74  107.49  466.74  113.63  466.13  125.92     463  132.06  461.92
  199.62  460.44  267.19  457.76  291.76  457.78  307.11  458.28  364.85  453.61
  370.77  453.18  480.16  453.18  486.03  453.49  489.34  454.55   492.4  456.13
  495.47  458.76  498.53  462.49  516.89  477.06  519.95  482.06  535.26  495.29
#Mann= 3 , 0 , 0
       0      .1       0  364.85    .041       0  486.03      .1       0
Bank Sta=364.85,486.03
XS Rating Curve= 0 ,0
Exp/Cntr=0.3,0.1

Type RM Length L Ch R = 1 ,4480.549,89.45,91.46,93.44
XS GIS Cut Line= 2
     611067.8301    4344598.5938     611624.2791    4344494.0102
#Sta/Elev= 30
       0   495.5   12.24  491.43   27.54  487.65   33.67  485.43   48.97  482.13
   55.09  479.38   67.33  475.74   76.51  472.23  110.18  468.35  119.36  466.57
   131.6  465.96   146.9  463.84  153.02  462.61  159.15  460.35  165.27  459.38
  205.05  459.13  220.36  457.22  254.02  455.74   263.2  456.38  324.41  455.26
  345.84  454.03  373.38  453.53  504.98  453.17   511.1   453.9  520.28  457.95
   526.4  461.96  529.47  465.79  547.83  480.49  550.89  484.36  566.19   495.3
#Mann= 3 , 0 , 0
       0      .1       0  373.38    .041       0   511.1      .1       0
Bank Sta=373.38,511.1
XS Rating Curve= 0 ,0
Exp/Cntr=0.3,0.1

Type RM Length L Ch R = 1 ,4389.086,111.75,91.42,79.42
XS GIS Cut Line= 4
     611053.1012    4344683.4335      611361.295     4344628.756
     611442.2843    4344621.0644     611641.8298     4344584.101
#Sta/Elev= 30
       0  496.13   12.27  492.33   33.76  483.14   36.82  480.85   42.96  478.46
   79.79   470.3   85.92  469.54  110.47  467.86  141.16  464.01   147.3   464.1
   156.5   465.6  162.64  463.88  171.85   462.5  184.12  462.49   205.6   460.2
  227.08  459.03  251.63   458.3  325.06   458.8  403.45  453.67  415.56  453.18
  548.84  453.19  551.87  453.88  557.92  456.67  563.98  461.15  570.04  467.15
  573.07  472.36   576.1  476.03  585.18  484.87  591.24  489.69   597.3  495.52
#Mann= 3 , 0 , 0
       0      .1       0  403.45    .041       0  551.87      .1       0
Bank Sta=403.45,551.87
XS Rating Curve= 0 ,0
Exp/Cntr=0.3,0.1

Type RM Length L Ch R = 1 ,4297.67 ,103.13,91.4,80.34
XS GIS Cut Line= 5
     611165.1077    4344844.3593     611435.6893    4344740.2781
     611465.3227    4344714.8781     611514.1528    4344704.7322
     611676.8872     4344650.247
#Sta/Elev= 30
       0  495.93    9.16  491.91   30.52  485.23   45.78  481.46   51.88   479.4
   70.19  476.42    88.5   471.9    94.6  469.58   97.65  467.45  100.71  466.48
  109.86  465.81  122.07  462.48  137.33  459.28  161.74   457.6  186.15   456.7
  247.19  456.62  319.93  455.59  349.47   453.7  355.34  453.19  489.13  453.17
  495.26  453.89  498.33  455.25  501.39  458.14  516.72  469.96  525.91  479.29
   535.1  486.16  541.23  489.94   544.3  492.78  547.36   494.2  550.43  496.63
#Mann= 3 , 0 , 0
       0      .1       0  349.47    .041       0  495.26      .1       0
Bank Sta=349.47,495.26
XS Rating Curve= 0 ,0
Exp/Cntr=0.3,0.1

Type RM Length L Ch R = 1 ,4206.266,102.14,91.49,77.51
XS GIS Cut Line= 3
     611189.8075    4344954.9779     611507.4588    4344814.0388
     611717.8315    4344711.4982
#Sta/Elev= 30
       0  495.06    9.15  493.19   18.29  490.46   60.97  486.29   70.11  485.98
   76.21     485  118.89   470.8  124.98  467.74  128.03  466.83  152.42  466.17
  158.52  464.37  170.71  459.17  173.76  458.56  213.39  459.68  246.92   458.4
   283.5  458.86  310.93   454.9  356.63  455.87  359.67  455.71  365.75  453.85
  371.83  453.18  502.52  453.85   508.6  454.29  511.64  455.58  520.76  461.67
  538.99  469.54  545.07  473.67  563.31  482.99  569.39  487.33  581.55  493.87
#Mann= 3 , 0 , 0
       0      .1       0  365.75    .041       0  502.52      .1       0
Bank Sta=365.75,502.52
XS Rating Curve= 0 ,0
Exp/Cntr=0.3,0.1

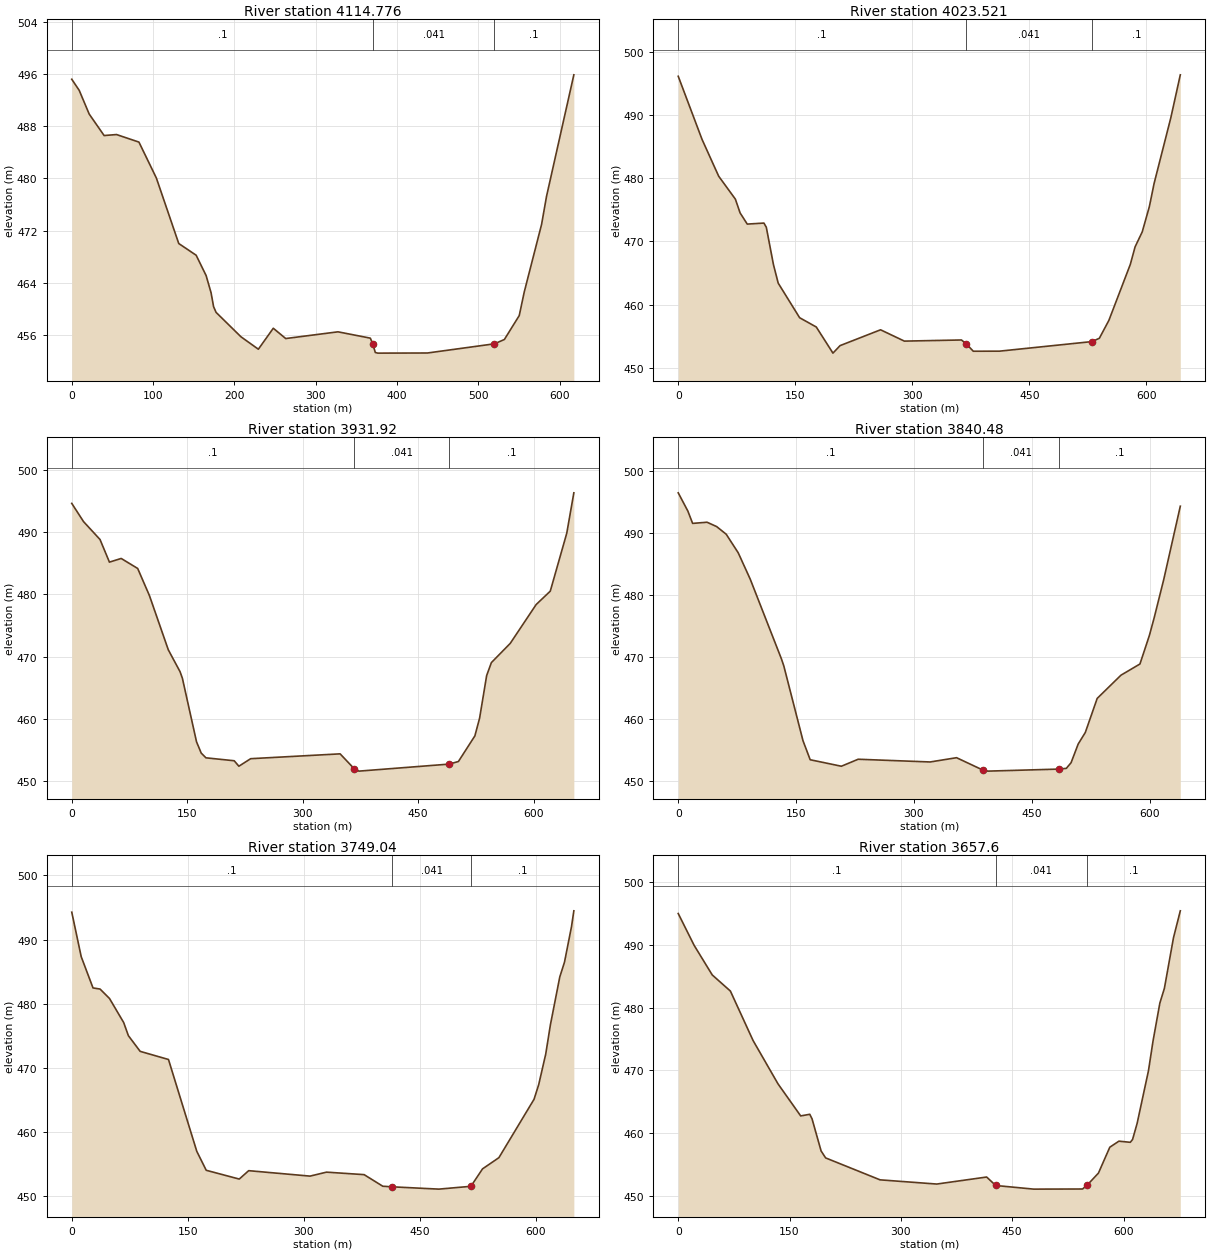
Type RM Length L Ch R = 1 ,4114.776,109.94,91.25,91.77
XS GIS Cut Line= 3
     611236.1226    4345067.3916      611597.154    4344879.7832
     611766.7795    4344755.1545
#Sta/Elev= 30
       0  495.23    9.18  493.52   21.41  489.89   39.77  486.59   55.06  486.74
    82.6  485.58  104.01  480.07  131.54  470.01  152.96  468.21  165.19  465.09
  171.31  462.44  174.37  460.32  177.43  459.44  208.02  455.69  229.44  453.78
  247.79     457  263.09  455.42  327.33  456.45   367.1  455.48  370.16  454.59
  373.22  453.28  376.28  453.18  437.37   453.2  519.74  454.61  531.94  455.27
  550.24  458.95  556.34  462.55   577.7  472.95   583.8  477.27  617.36  495.91
#Mann= 3 , 0 , 0
       0      .1       0  370.16    .041       0  519.74      .1       0
Bank Sta=370.16,519.74
XS Rating Curve= 0 ,0
Exp/Cntr=0.3,0.1

Type RM Length L Ch R = 1 ,4023.521,100.95,91.6,97.84
XS GIS Cut Line= 4
     611314.6364    4345185.4618     611603.2821    4344996.8451
     611638.2651    4344963.0571     611839.3747    4344814.2449
#Sta/Elev= 30
       0   496.1   30.51  486.12   51.87  480.29   73.23  476.67   79.34  474.48
   88.49  472.72  109.85  472.88   112.9  472.22  122.06  466.31  128.16  463.38
  155.62  457.91  176.98  456.44  198.34  452.31   207.5   453.5  259.37     456
  289.88  454.21  363.05  454.39  369.13  453.79  378.24  452.61  411.75  452.62
  530.74  454.14  539.89  454.67  552.09   457.5  579.55  466.35  585.66  469.12
  594.81  471.49  603.96  475.49  610.06  479.17  631.42  489.52  643.62  496.33
#Mann= 3 , 0 , 0
       0      .1       0  369.13    .041       0  530.74      .1       0
Bank Sta=369.13,530.74
XS Rating Curve= 0 ,0
Exp/Cntr=0.3,0.1

Type RM Length L Ch R = 1 ,3931.92 ,100.41,91.44,81.04
XS GIS Cut Line= 5
     611428.6083    4345302.4021     611701.3876    4345030.1388
     611781.1809    4344971.4404     611800.0685    4344962.3166
     611929.9947    4344893.6201
#Sta/Elev= 30
       0  494.65   15.29  491.72   36.71  488.84   48.94   485.2   64.23  485.79
   85.65  484.18  100.94  479.81  125.41   471.1   140.7  467.57  143.76  466.51
  162.11  456.29  168.23  454.47  174.35  453.71  211.05  453.24  217.17  452.36
  232.47  453.57   348.7  454.35  367.05  451.95  373.17  451.57  490.45   452.7
  502.44  453.12  523.81  457.24  529.93  460.08  539.12  466.95  545.24  469.03
  569.74  472.12  603.42  478.37  621.79  480.53  643.22  489.86  652.41  496.35
#Mann= 3 , 0 , 0
       0      .1       0  367.05    .041       0  490.45      .1       0
Bank Sta=367.05,490.45
XS Rating Curve= 0 ,0
Exp/Cntr=0.3,0.1

Type RM Length L Ch R = 1 ,3840.48 ,91.84,91.44,89.18
XS GIS Cut Line= 5
     611482.2306    4345366.8724     611750.4171    4345126.0943
     611780.7513    4345087.4614      611832.621    4345041.3055
      611951.867    4344934.2778
#Sta/Elev= 30
       0  496.51   12.22  493.57   18.33  491.57   36.65  491.76   48.87  491.06
   61.09  489.82   76.36  486.82   91.63  482.57  131.34  469.69  134.39  468.55
  158.83  456.46  167.99  453.38   207.7  452.33  229.08  453.46  320.71  453.02
  354.31  453.71  388.04   451.7  394.15  451.54  485.01  451.87  494.08  451.99
  500.13   452.9   509.2  455.92  518.27  457.79  533.38  463.29  563.62  467.04
   587.8  468.85   599.9  473.49  605.94  476.33  618.03  482.46   639.2  494.35
#Mann= 3 , 0 , 0
       0      .1       0  388.04    .041       0  485.01      .1       0
Bank Sta=388.04,485.01
XS Rating Curve= 0 ,0
Exp/Cntr=0.3,0.1

Type RM Length L Ch R = 1 ,3749.04 ,91.9,91.44,92.23
XS GIS Cut Line= 5
     611539.1162     4345455.508     611798.0844    4345205.4489
     611890.9036    4345106.2345     611909.5423    4345092.3047
     611991.5546    4344991.1633
#Sta/Elev= 30
       0  494.27    12.2  487.33   27.46  482.45   36.61  482.27   48.81   480.8
   67.12  477.05   73.22     475   88.47  472.55  125.08  471.28  161.69  456.95
  173.89  453.99  216.61  452.62  228.81  453.93  308.13  453.08  329.48   453.7
  378.11  453.31  402.26   451.5  414.34  451.41  474.72  451.05  516.22  451.49
  531.24  454.21  552.43  455.96  597.86  465.07  603.91  467.36     613  472.14
  619.05  476.71  631.17  484.17  637.22  486.46  646.31  492.01  649.34  494.48
#Mann= 3 , 0 , 0
       0      .1       0  414.34    .041       0  516.22      .1       0
Bank Sta=414.34,516.22
XS Rating Curve= 0 ,0
Exp/Cntr=0.3,0.1

Type RM Length L Ch R = 1 ,3657.6  ,86.12,91.44,97.79
XS GIS Cut Line= 4
     611594.6788    4345546.7894     611908.8169     4345221.478
      611958.759    4345166.6972      612071.165    4345067.1781
#Sta/Elev= 30
       0  495.02   21.39  489.95   45.83  485.22   70.28  482.65  100.83  474.76
  134.45  467.84     165  462.73  177.22  462.99  180.28  462.27   192.5  457.14
  198.61  456.03  271.95  452.53  348.34  451.86  415.56  452.98  427.78  451.63
  478.91  451.05  544.74  451.07  550.87  451.67  566.19  453.61  581.51  457.74
  593.76   458.7  609.08  458.52  612.15  458.97  618.27  461.52  633.59  469.94
  639.72  474.67  648.91  480.72  655.04  483.08   667.3  491.16  676.49  495.45
#Mann= 3 , 0 , 0
       0      .1       0  427.78    .041       0  550.87      .1       0
Bank Sta=427.78,550.87
XS Rating Curve= 0 ,0
Exp/Cntr=0.3,0.1

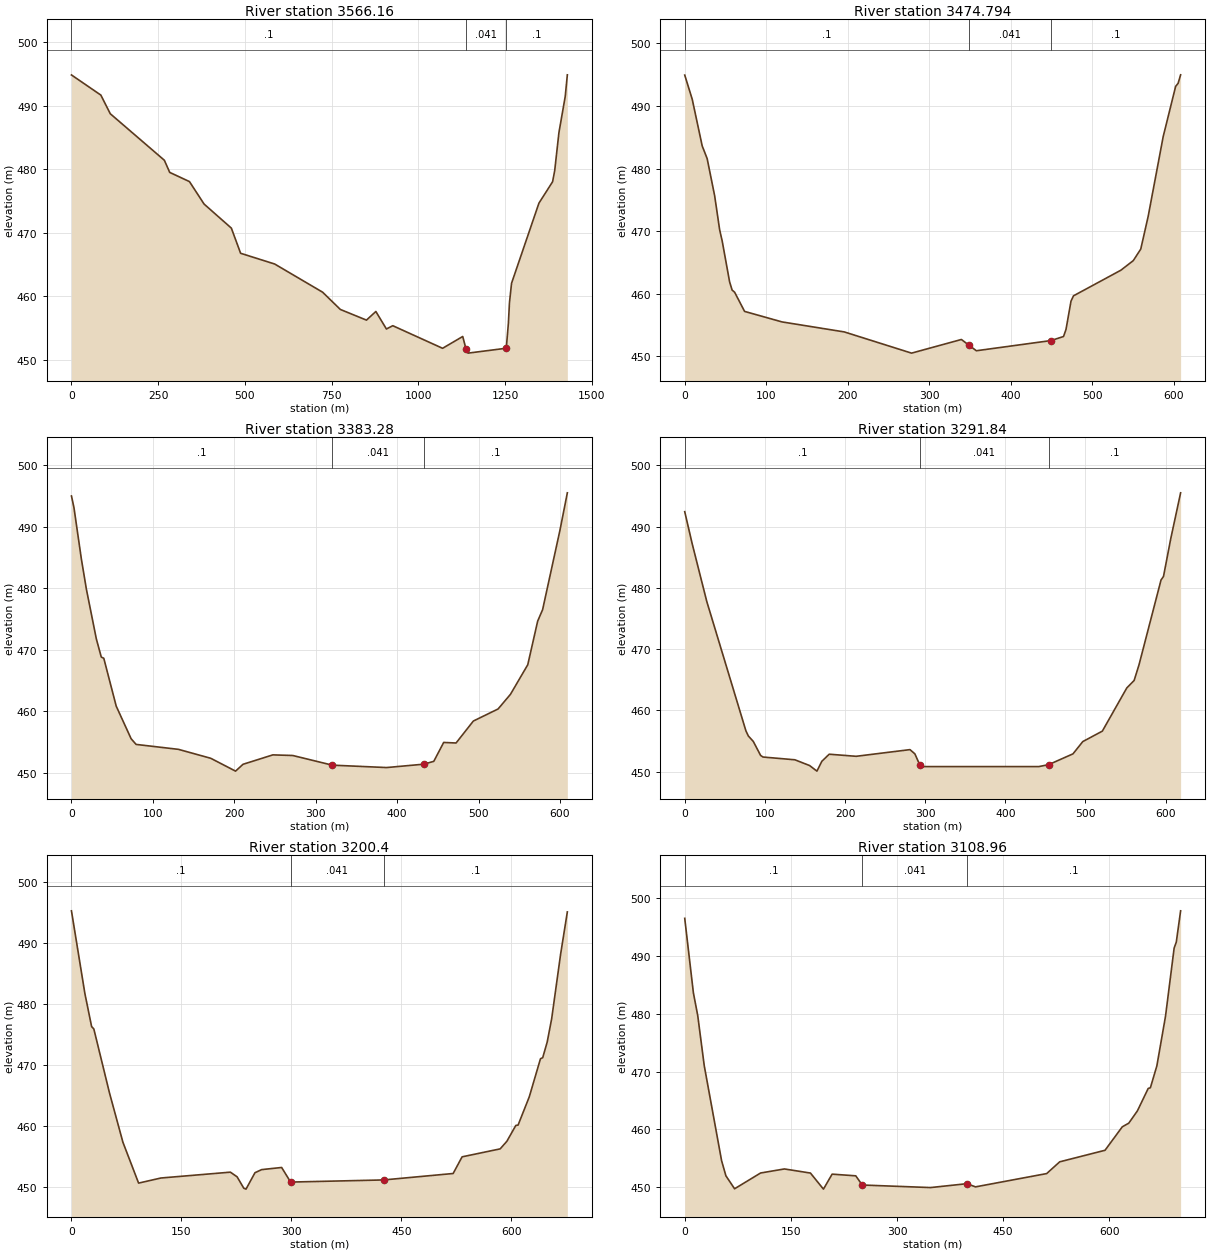
Type RM Length L Ch R = 1 ,3566.16 ,96.01,91.37,83.6
XS GIS Cut Line= 6
     611100.0833    4345874.0797     611446.4994    4345833.2152
     611548.8176    4345704.4814     611714.1825    4345640.9813
     611775.4783    4345480.0231      612163.975    4345097.2614
#Sta/Elev= 30
       0  494.85   84.65  491.68  111.86  488.74  267.74  481.41  283.11   479.5
  340.06  478.05  382.21  474.51  460.78  470.72  487.42  466.76  585.49  465.07
  723.68  460.63  774.83  457.91  850.06  456.23  877.14  457.59  907.59  454.83
  925.91  455.35 1069.43  451.79 1127.45  453.65 1136.95  451.68 1142.72  451.03
 1252.97   451.8 1259.04  455.72 1262.07  458.92 1268.14  462.03 1347.03  474.65
 1386.47  478.03 1392.53  479.78 1404.67  485.76 1422.87  491.47 1428.94  494.87
#Mann= 3 , 0 , 0
       0      .1       0 1136.95    .041       0 1252.97      .1       0
Bank Sta=1136.95,1252.97
XS Rating Curve= 0 ,0
Exp/Cntr=0.3,0.1

Type RM Length L Ch R = 1 ,3474.794,86.06,91.51,84.73
XS GIS Cut Line= 3
     611806.7868    4345642.3042      611877.408    4345517.1108
     612198.2387    4345181.3991
#Sta/Elev= 30
       0  494.94    9.17  491.09   21.41  483.62   27.52  481.58    36.7  475.64
   42.82   470.2   45.87  468.46   55.05  461.87   58.11  460.57   61.17  460.23
    73.4  457.16  119.27  455.48  195.67  453.88  278.16  450.49  339.26  452.67
  348.43  451.77  357.59  450.87  449.24   452.5  464.52  453.15  467.57  454.29
  473.68   458.8  476.74  459.65  534.78  463.74  550.06  465.28  559.22  467.12
  568.39   472.4  586.72   485.1  601.99  493.13  605.05  493.63   608.1  494.98
#Mann= 3 , 0 , 0
       0      .1       0  348.43    .041       0  449.24      .1       0
Bank Sta=348.43,449.24
XS Rating Curve= 0 ,0
Exp/Cntr=0.3,0.1

Type RM Length L Ch R = 1 ,3383.28 ,101.37,91.44,92.96
XS GIS Cut Line= 5
      611853.255     4345670.112     612058.1083    4345451.9558
     612093.2877    4345423.6706     612150.1976    4345364.1274
     612250.9686    4345212.2789
#Sta/Elev= 30
       0  494.98    3.05   493.1   12.21   484.7   18.32  479.84   30.54  471.76
   36.64   468.8    39.7  468.61   54.97  460.83   73.29  455.53    79.4  454.61
  131.31  453.81  171.01  452.36  201.54  450.27   210.7  451.38  247.35  452.91
  271.78  452.81  320.33  451.24  387.11  450.85  432.84   451.4  444.99  451.86
  457.14  454.93  472.33  454.84  493.59  458.41  523.96  460.37  539.15  462.75
  560.41  467.56  572.56  474.64  578.64  476.51   599.9  489.39  609.01  495.49
#Mann= 3 , 0 , 0
       0      .1       0  320.33    .041       0  432.84      .1       0
Bank Sta=320.33,432.84
XS Rating Curve= 0 ,0
Exp/Cntr=0.3,0.1

Type RM Length L Ch R = 1 ,3291.84 ,77.68,91.44,91.11
XS GIS Cut Line= 4
     611951.8514    4345719.2913     612169.0539    4345479.0956
     612245.3545    4345389.1742     612338.0577     4345238.348
#Sta/Elev= 30
       0  492.45    9.17  487.29    27.5   477.8   76.38  456.66   79.43  455.83
   85.54  454.95   94.71  452.66   97.76   452.4  137.48  451.95  155.81  451.01
  164.97   450.1  171.08   451.7  180.25  452.86  213.86  452.52  281.07  453.61
  287.18  452.92  293.29  451.13  296.34  450.84  441.77  450.84  453.98  451.15
   484.5  452.92  496.71  454.92  521.13  456.63  551.65  463.68  560.81   464.9
  566.92  467.47  594.39  481.31  597.44  481.88   606.6  488.11  618.81  495.53
#Mann= 3 , 0 , 0
       0      .1       0  293.29    .041       0  453.98      .1       0
Bank Sta=293.29,453.98
XS Rating Curve= 0 ,0
Exp/Cntr=0.3,0.1

Type RM Length L Ch R = 1 ,3200.4  ,90.74,91.44,87.31
XS GIS Cut Line= 6
     611998.7424    4345768.1248     612187.4524    4345576.9011
     612234.5478     4345539.326     612290.8374    4345483.4261
     612318.6859    4345447.7842     612420.5505    4345249.4254
#Sta/Elev= 30
       0  495.34   18.32  481.74   27.48  476.31   30.53  475.91    51.9  465.38
   70.22  457.27   91.59  450.56  122.12   451.4  216.76  452.36  225.92   451.6
  235.08  449.72  238.13  449.57  250.34  452.27   259.5  452.78  286.73  453.13
  298.99  450.73  425.86  451.08  520.67  452.14  532.89  454.88  584.82  456.19
  593.98  457.44   606.2  460.05  609.25   460.1  624.53  464.75   639.8  471.01
  642.86  471.19  648.96  473.75  655.07  477.59  667.29  488.22  676.46  495.16
#Mann= 3 , 0 , 0
       0      .1       0  298.99    .041       0  425.86      .1       0
Bank Sta=298.99,425.86
XS Rating Curve= 0 ,0
Exp/Cntr=0.3,0.1

Type RM Length L Ch R = 1 ,3108.96 ,116.68,91.44,40.13
XS GIS Cut Line= 6
     612087.8823    4345807.0064     612236.1755    4345656.3821
     612297.0561    4345606.1192     612356.7843    4345546.8046
      612390.957    4345500.2776     612507.5251    4345258.2307
#Sta/Elev= 30
       0   496.5   12.25   483.6   18.38  479.68   27.57  471.02   52.08  454.59
    58.2  451.96   70.46  449.72  107.22  452.45  140.92  453.15  177.68  452.44
  196.06  449.66  208.31  452.25  241.74  451.96  250.85  450.37  347.44  449.93
   398.8   450.6  410.96  450.05   511.6  452.35  529.92  454.38  594.03  456.38
  618.45  460.44  627.61  461.07  639.82   463.2  655.09  467.08  658.14  467.19
   667.3  470.98  679.51  479.55  691.72  491.36  694.77  492.39  700.88   497.8
#Mann= 3 , 0 , 0
       0      .1       0  250.85    .041       0   398.8      .1       0
Bank Sta=250.85,398.8
XS Rating Curve= 0 ,0
Exp/Cntr=0.3,0.1