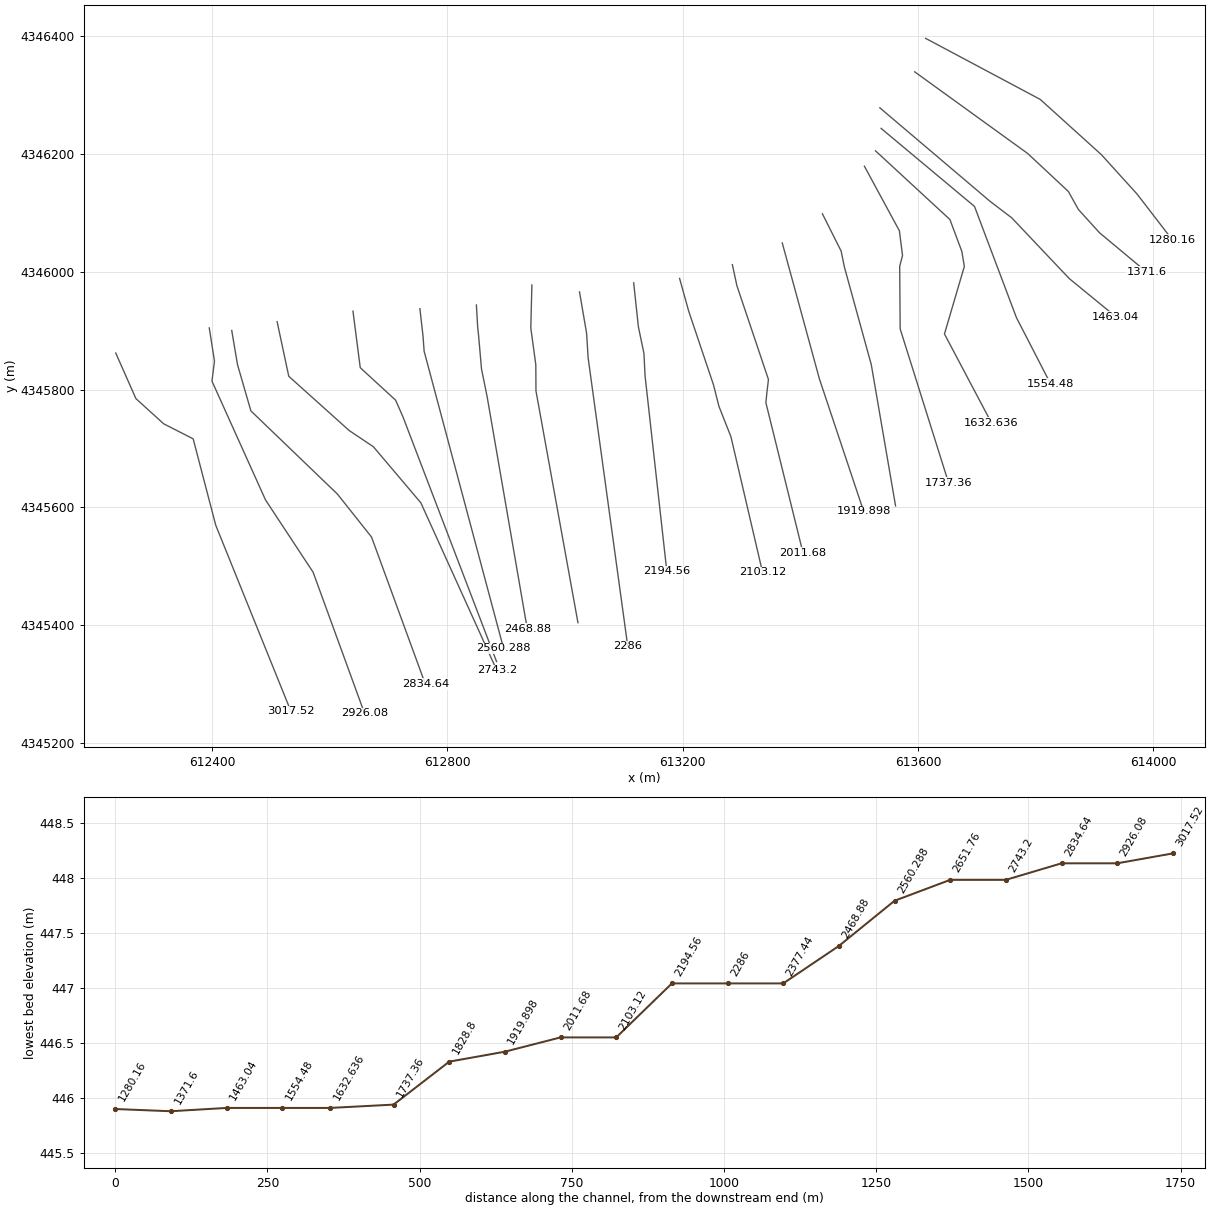
HEC-RAS study CheatRiver.prj: CheatRiver

--- CheatRiver.g01 (geometry) --- (continued)

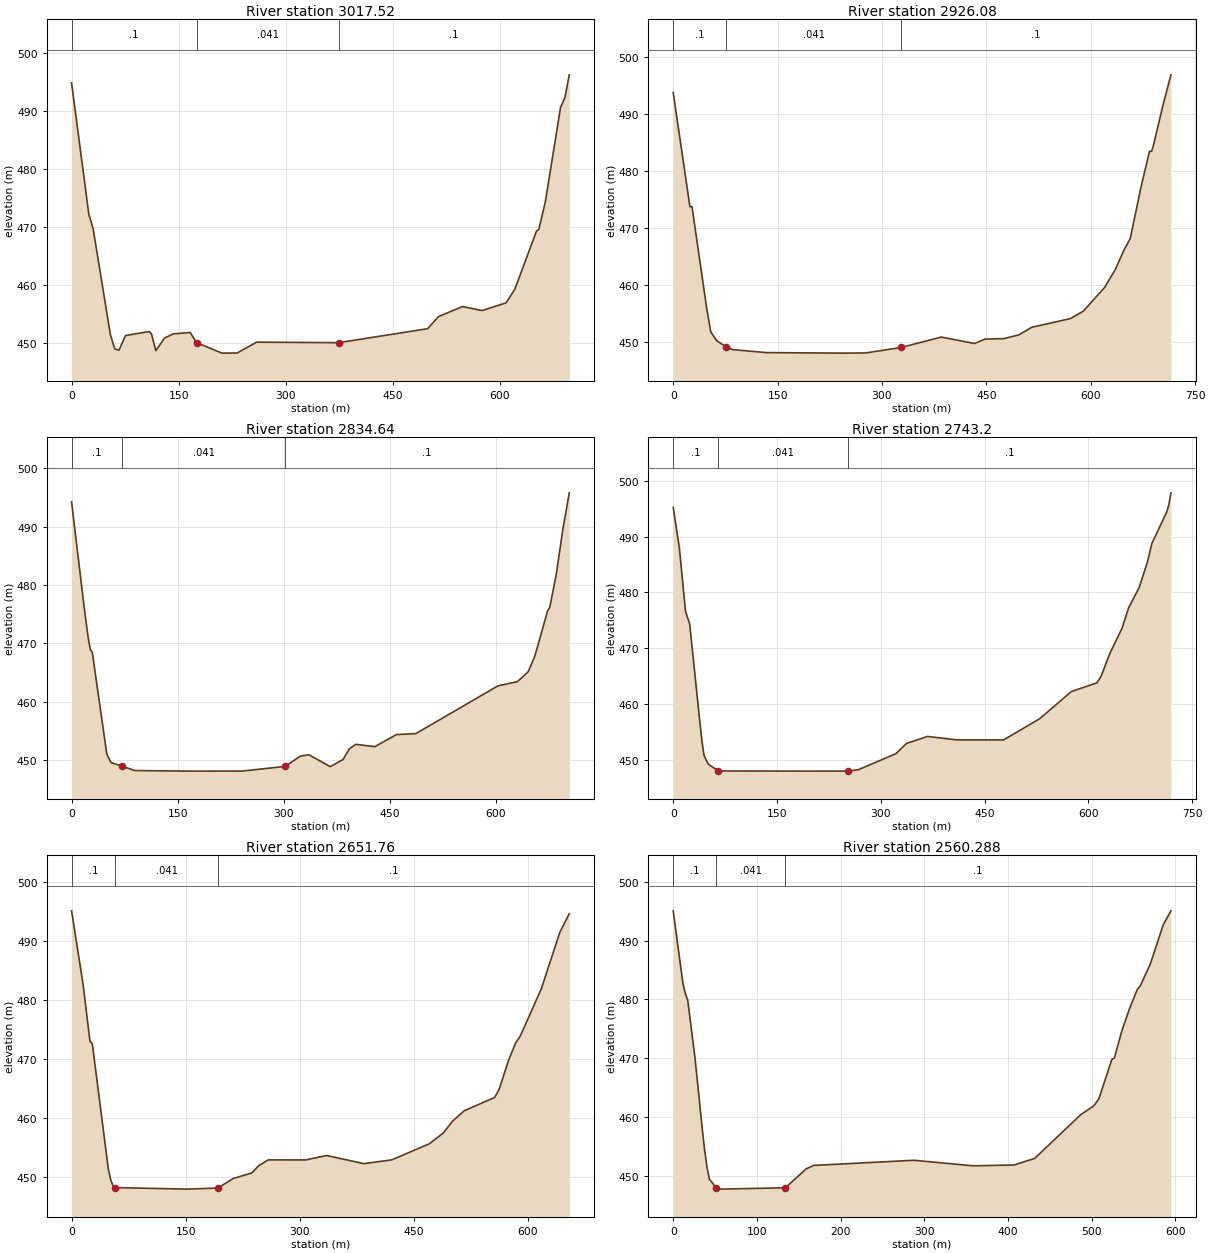
Type RM Length L Ch R = 1 ,3017.52 ,141.97,91.44,111.7
XS GIS Cut Line= 6
     612236.1446    4345861.9354     612270.4138    4345784.5409
     612317.6012    4345741.7765     612367.7412    4345716.2038
     612406.1296    4345569.4475     612533.7751    4345253.8003
#Sta/Elev= 30
       0  494.81   24.18  472.16   30.23  469.65   54.41   451.4   60.46  448.96
    66.5  448.73   75.57  451.25   108.9  451.94  111.93  451.53     118  448.65
  130.13   450.8  142.26  451.54   166.1  451.78  174.99  450.03  210.68  448.22
  231.91  448.24  259.22  450.11  374.04  450.02  498.66  452.43  513.91  454.52
  547.47  456.25  574.93  455.55  608.49  456.89  620.69   459.2   651.2  469.29
  654.26  469.51  663.41  474.24  684.76  490.56  690.87  492.27  696.97  496.18
#Mann= 3 , 0 , 0
       0      .1       0  174.99    .041       0  374.04      .1       0
Bank Sta=174.99,374.04
XS Rating Curve= 0 ,0
Exp/Cntr=0.3,0.1

Type RM Length L Ch R = 1 ,2926.08 ,39.09,91.44,110.45
XS GIS Cut Line= 6
     612395.1155    4345904.5707     612403.9361    4345848.2725
     612399.7027    4345814.2074     612490.7419    4345612.4382
     612571.6292    4345489.6888     612659.0379    4345249.9903
#Sta/Elev= 30
       0  493.72   23.99  473.76   26.99  473.76   47.99  456.08   53.99  451.84
   62.66  450.27   76.48  449.21   85.62  448.74  133.62  448.22  246.17  448.13
  276.59  448.16  327.59  449.12  385.18  450.94  433.13  449.81  448.11  450.58
  475.47  450.67  496.98  451.34  515.43  452.66  570.76  454.17   589.2  455.46
  619.94  459.62  635.31  462.75  647.61  466.12  656.83  468.18   672.2  477.16
   684.5  483.45  687.57  483.45  690.64  484.72  702.94  491.07  715.24  496.83
#Mann= 3 , 0 , 0
       0      .1       0   76.48    .041       0  327.59      .1       0
Bank Sta=76.48,327.59
XS Rating Curve= 0 ,0
Exp/Cntr=0.3,0.1

Type RM Length L Ch R = 1 ,2834.64 ,81.71,91.44,99.34
XS GIS Cut Line= 6
      612433.303    4345900.2603     612443.0574    4345842.4014
     612465.8869    4345763.6226     612613.0365    4345622.3335
     612670.9805    4345549.3524     612762.3315    4345299.7673
#Sta/Elev= 30
       0  494.27    17.6  476.44   23.47  471.03    26.4  468.99   29.34  468.46
   49.87  451.03   55.74  449.61   71.21  448.98   89.35  448.23  165.12  448.13
  241.24  448.14  302.13  448.94  323.45   450.7  335.63  450.93   365.8   448.9
  383.84  450.11  392.86  451.95  401.88  452.72  428.93  452.33  459.33  454.39
  486.83  454.56  602.91  462.74  630.41  463.45  645.68  465.16  654.85  467.75
  673.18  475.59  676.23  476.21   685.4  481.87  694.56  489.47  703.73  495.81
#Mann= 3 , 0 , 0
       0      .1       0   71.21    .041       0  302.13      .1       0
Bank Sta=71.21,302.13
XS Rating Curve= 0 ,0
Exp/Cntr=0.3,0.1

Type RM Length L Ch R = 1 ,2743.2  ,125.47,91.44,52.28
XS GIS Cut Line= 6
     612510.4186    4345915.2254     612530.2444    4345822.4441
     612632.9468    4345730.3178     612674.0673    4345702.8111
     612754.7654    4345607.5609     612883.7754    4345323.3153
#Sta/Elev= 30
       0  495.23     8.9  487.95   17.81  476.57   23.74   474.4   38.58   456.7
   41.55  453.34   44.52  450.78   50.45  449.25   65.27  448.01     193  447.98
  253.23  447.99  267.78  448.24  321.91  451.11  337.13  452.94  367.58  454.19
  410.23  453.58  477.55  453.58  529.58  457.36  575.48  462.24  612.21  463.79
  618.33  464.95  630.57  468.93  648.93  473.65  658.11  477.22  673.41  480.86
  685.66  485.55  691.78  488.78   713.2  494.37  716.26  495.68  719.32  497.84
#Mann= 3 , 0 , 0
       0      .1       0   65.27    .041       0  253.23      .1       0
Bank Sta=65.27,253.23
XS Rating Curve= 0 ,0
Exp/Cntr=0.3,0.1

Type RM Length L Ch R = 1 ,2651.76 ,112.9,91.47,57.31
XS GIS Cut Line= 5
     612639.3436    4345933.1129     612651.7601    4345837.0475
      612711.863    4345781.8712     612724.3823    4345753.4348
     612883.4116    4345338.0217
#Sta/Elev= 30
       0  495.09   15.14  482.67   24.22  473.01   27.24  472.61   48.43  451.31
   51.46  449.57   54.49  448.55   57.51  448.24  151.26  447.98  192.58  448.17
  212.59  449.78  237.13  450.72  246.34  451.98  258.61  452.93  307.69  452.92
   335.3  453.67  384.38  452.29  421.19  452.94  470.28  455.65  488.68  457.47
  500.95  459.49  516.29  461.25  556.17  463.49  562.31  464.93  574.58  469.79
  583.78  472.69  589.92  473.89  617.52  481.86  642.07  491.48  654.34   494.6
#Mann= 3 , 0 , 0
       0      .1       0   57.51    .041       0  192.58      .1       0
Bank Sta=57.51,192.58
XS Rating Curve= 0 ,0
Exp/Cntr=0.3,0.1

Type RM Length L Ch R = 1 ,2560.288,94.66,91.41,78.31
XS GIS Cut Line= 4
     612753.1465    4345937.2387     612758.3691    4345891.4007
       612760.34    4345864.9627     612895.3179    4345360.5114
#Sta/Elev= 30
       0  495.04   11.53  482.81   14.42  481.01    17.3  479.92   25.95  470.19
    34.6  458.18   37.48  454.51   40.37   451.5   43.25  449.48   51.22  448.04
   54.97  447.79  134.05  448.02  158.65   451.2  167.87  451.82  287.67  452.69
  358.32  451.75  407.47  451.89  432.04  453.01  487.33  460.47  502.69  461.93
  508.83  463.16  524.19  469.81  527.26  470.06  536.48  474.79  545.69  478.56
  554.91  481.77  557.98  482.25  570.27  486.05  585.63  492.68  594.84  495.06
#Mann= 3 , 0 , 0
       0      .1       0   51.22    .041       0  134.05      .1       0
Bank Sta=51.22,134.05
XS Rating Curve= 0 ,0
Exp/Cntr=0.3,0.1

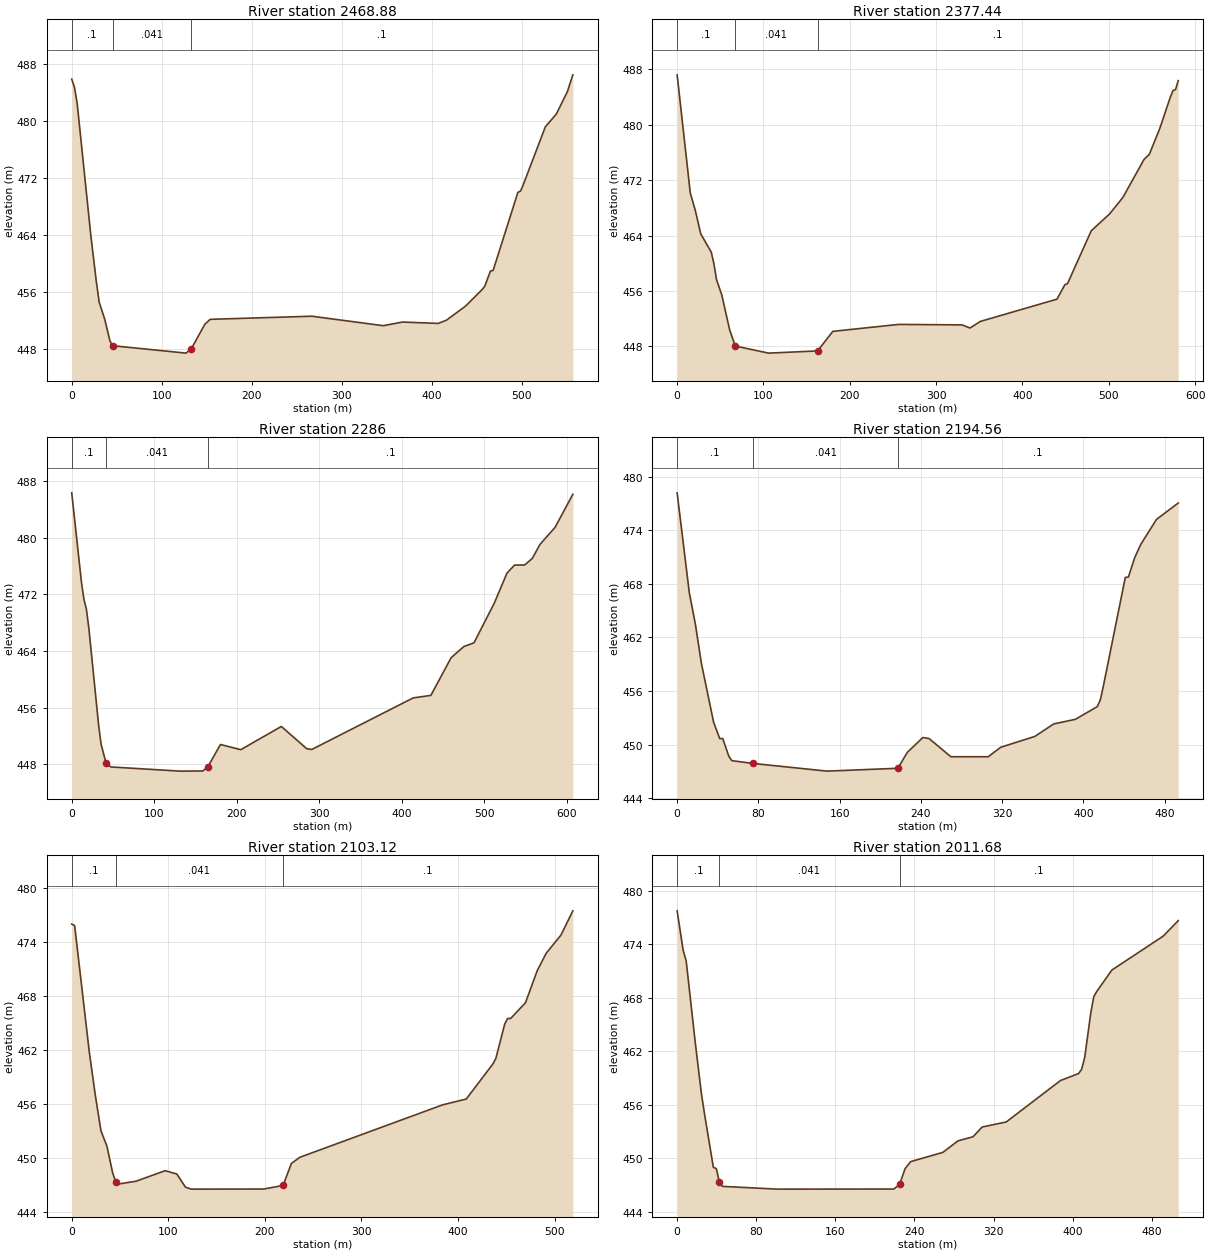
Type RM Length L Ch R = 1 ,2468.88 ,91.06,91.44,84.09
XS GIS Cut Line= 6
     612849.1737    4345943.5809     612851.2767    4345907.0645
     612852.8343     4345892.263     612857.8773    4345834.7574
     612867.3733    4345788.0953     612935.5512    4345394.0474
#Sta/Elev= 30
       0  485.82    3.05  484.68     6.1  482.38   21.34  463.75   27.43  457.33
   30.48  454.54   36.58  452.17   42.53  449.08   45.51  448.42  127.04  447.38
     133  448.02  147.88  451.43  153.83  452.12   266.7  452.56  346.07  451.23
  367.44  451.74  407.13  451.55  416.28     452  437.65  453.99  455.97   456.3
  459.02  456.81  465.13  458.89  468.18  458.99  495.65  469.93  498.71  470.13
  501.76  471.05  526.18  479.14  538.39  480.93   550.6  484.06  556.71  486.43
#Mann= 3 , 0 , 0
       0      .1       0   45.51    .041       0     133      .1       0
Bank Sta=45.51,133
XS Rating Curve= 0 ,0
Exp/Cntr=0.3,0.1

Type RM Length L Ch R = 1 ,2377.44 ,89.75,91.44,93.62
XS GIS Cut Line= 5
     612943.4887    4345977.4548     612941.6659    4345904.4826
     612950.1696    4345842.0568     612950.4306    4345797.6423
     613021.8055    4345403.9693
#Sta/Elev= 30
       0  487.17   15.21  470.15   21.29  467.49   27.37  464.23   39.54   461.6
   42.58  459.94   45.62  457.65    51.7  455.44   60.83  450.41   67.34  448.06
     106  447.04  162.65  447.36  180.41  450.18  256.77  451.18  330.06  451.11
  339.23  450.66  351.44  451.62  440.01  454.82  449.18  456.91  452.23  457.07
  479.72  464.68   501.1  467.13  516.37  469.49   540.8  474.96  546.91  475.69
  559.12  479.44  571.34  483.96  574.39  484.89  577.45  485.07   580.5  486.33
#Mann= 3 , 0 , 0
       0      .1       0   67.34    .041       0  162.65      .1       0
Bank Sta=67.34,162.65
XS Rating Curve= 0 ,0
Exp/Cntr=0.3,0.1

Type RM Length L Ch R = 1 ,2286    ,91.36,91.44,90.44
XS GIS Cut Line= 4
     613024.4596    4345965.6796      613036.524    4345895.4057
     613039.0762    4345853.9944     613106.4724    4345363.7525
#Sta/Elev= 30
       0  486.35   11.88  473.65   14.85  471.29   17.83   469.9    20.8   467.2
   32.68  453.47   35.65  450.83   41.59  448.18   47.53  447.63  131.23  447.04
   158.9  447.06  165.04  447.65  180.41   450.8     205  450.07  254.18  453.35
  284.91  450.21  291.06   450.1  414.01  457.38  435.52  457.74  460.11  463.07
  475.48  464.64  487.77  465.16  512.36  470.76  527.73     475  536.95  476.14
  549.25  476.16  558.47  477.08  567.69  479.05  586.13  481.48  607.64  486.14
#Mann= 3 , 0 , 0
       0      .1       0   41.59    .041       0  165.04      .1       0
Bank Sta=41.59,165.04
XS Rating Curve= 0 ,0
Exp/Cntr=0.3,0.1

Type RM Length L Ch R = 1 ,2194.56 ,84.73,91.44,146.62
XS GIS Cut Line= 5
     613116.5266    4345981.1149     613124.5065    4345906.6556
      613133.985    4345861.1375      613135.851     4345823.426
     613172.8927    4345491.1087
#Sta/Elev= 30
       0  478.19   11.98  467.01   17.97  463.49   23.96  459.06   35.95   452.5
   41.94  450.69   44.93  450.68   50.92   448.7   53.92  448.21   74.89   447.9
  147.52  447.04  217.42  447.36  226.63  449.13  241.96   450.8   248.1  450.69
  269.57  448.65  306.39  448.65  318.66  449.71   352.4  450.93  370.81  452.32
  392.28  452.84  413.75  454.26  416.82  455.03  419.89  456.63  441.36  468.72
  444.43  468.76  450.57  470.92   456.7  472.44  472.04  475.21  493.51  477.05
#Mann= 3 , 0 , 0
       0      .1       0   74.89    .041       0  217.42      .1       0
Bank Sta=74.89,217.42
XS Rating Curve= 0 ,0
Exp/Cntr=0.3,0.1

Type RM Length L Ch R = 1 ,2103.12 ,90.65,91.44,81.17
XS GIS Cut Line= 6
     613194.5588    4345988.6661      613209.999    4345933.1971
     613252.3315    4345807.4826     613261.4549    4345771.3808
     613281.8372    4345719.8597     613335.5138    4345489.9502
#Sta/Elev= 30
       0  476.02    3.03  475.86   18.18  461.82   24.24  457.13    30.3  453.02
   36.37  451.36   42.43  448.35   45.46  447.39   48.49  447.12   66.62  447.43
   96.77   448.6  108.83  448.23  117.87  446.76   123.9  446.55  198.82  446.56
  218.87  446.96  227.47   449.4  236.21  450.09  384.05  455.92  408.58  456.57
  436.18  460.47  439.24  461.09  448.44  464.92  451.51  465.53  454.58  465.53
  469.91  467.28  482.17  470.87  491.37  472.78   506.7  474.81  518.96   477.5
#Mann= 3 , 0 , 0
       0      .1       0   45.46    .041       0  218.87      .1       0
Bank Sta=45.46,218.87
XS Rating Curve= 0 ,0
Exp/Cntr=0.3,0.1

Type RM Length L Ch R = 1 ,2011.68 ,93.44,91.78,102.52
XS GIS Cut Line= 6
     613284.2498    4346012.0664     613291.9745    4345976.2856
     613345.6216    4345816.9702     613342.8614    4345793.9712
     613341.2739     4345777.567     613404.3056    4345522.7586
#Sta/Elev= 30
       0  477.75     6.1  473.32    9.15  472.14    18.3  463.02    24.4  457.38
   27.45  455.16   36.61     449   39.66  448.85   42.72  447.34   45.77  446.86
  100.79  446.55  219.19  446.56  224.98  447.09  230.62  448.86  236.11  449.63
  268.77  450.67  284.03  451.96  299.29  452.42  308.45  453.51  332.87  454.08
  387.81  458.73  406.12  459.51  409.17     460  412.23  461.32  418.33  466.27
  421.38  468.12  424.43  468.71   439.7  471.11  491.58  474.91  506.84  476.65
#Mann= 3 , 0 , 0
       0      .1       0   42.72    .041       0  224.98      .1       0
Bank Sta=42.72,224.98
XS Rating Curve= 0 ,0
Exp/Cntr=0.3,0.1

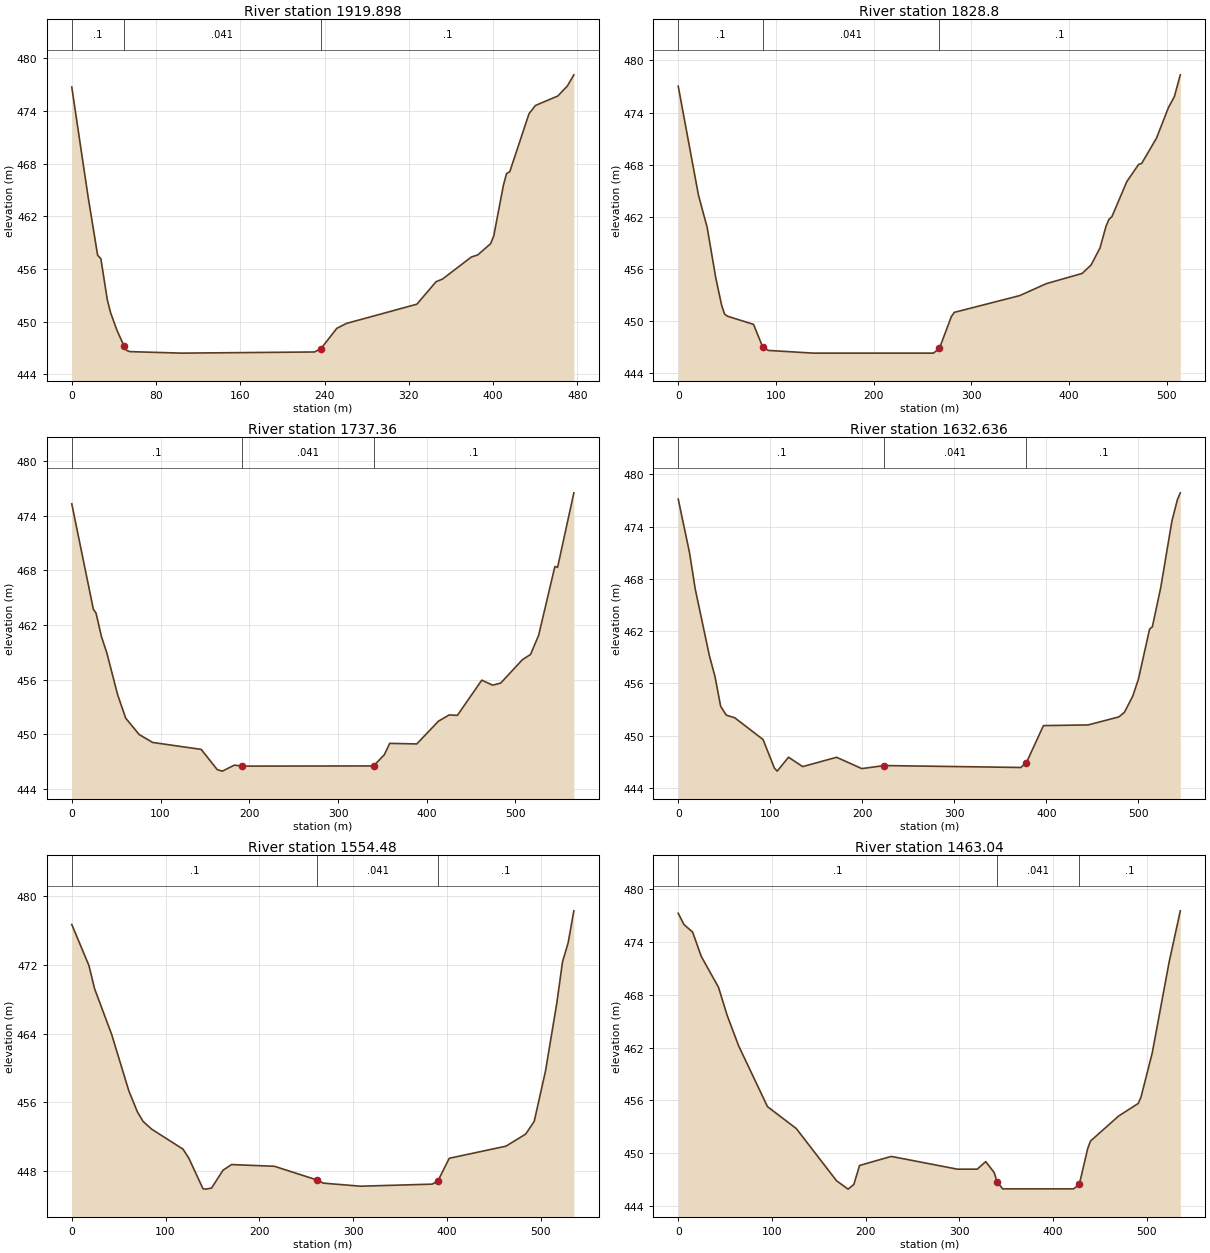
Type RM Length L Ch R = 1 ,1919.898,92.31,91.1,90.5
XS GIS Cut Line= 3
      613369.063    4346048.9101     613432.2382    4345817.9736
     613507.4404    4345593.0321
#Sta/Elev= 30
       0  476.71   15.35  464.33   24.56  457.56   27.63  457.16   33.76  452.48
   36.83  451.03   42.97     449   49.63  447.23   52.18  446.72   55.25  446.59
  104.36  446.42  230.21  446.55  236.35   446.9  251.58  449.24  260.71   449.8
   327.6  451.99  345.85  454.55  351.93  454.85   379.3  457.36  385.38   457.6
  397.54  458.87  400.58  459.76   409.7  465.51  412.74  466.87  415.79  467.07
  434.03  473.67  440.11  474.61   461.4  475.69  470.52  476.84   476.6   478.1
#Mann= 3 , 0 , 0
       0      .1       0   49.63    .041       0  236.35      .1       0
Bank Sta=49.63,236.35
XS Rating Curve= 0 ,0
Exp/Cntr=0.3,0.1

Type RM Length L Ch R = 1 ,1828.8  ,102.55,91.44,67.87
XS GIS Cut Line= 5
     613437.3257    4346098.3872     613469.2199    4346034.9171
      613474.623    4346008.1799     613520.3899     4345842.275
     613561.6801    4345602.2925
#Sta/Elev= 30
       0  477.04   20.72   464.5    29.6   460.8   38.48  454.96    44.4  451.85
   47.36  450.84   50.32  450.58   77.09  449.64   86.42  447.04   92.25  446.64
  138.26  446.33  261.19  446.33  267.34  446.87  279.54  450.53  282.59  451.02
  349.55  452.95  376.95  454.33  413.47   455.5  422.61  456.47  431.74  458.44
  437.83  460.91  440.87  461.73  443.91  462.03  459.13  466.06  471.31  468.05
  474.35  468.15  489.57  471.07  501.75  474.58  507.83  475.84  513.92  478.35
#Mann= 3 , 0 , 0
       0      .1       0   86.42    .041       0  267.34      .1       0
Bank Sta=86.42,267.34
XS Rating Curve= 0 ,0
Exp/Cntr=0.3,0.1

Type RM Length L Ch R = 1 ,1737.36 ,94.31,104.72,74.3
XS GIS Cut Line= 6
     613508.7633    4346179.0853     613568.1904     4346069.524
     613573.5344    4346027.4599     613568.6735    4346009.2028
     613569.5253    4345902.8533     613651.6386    4345641.9801
#Sta/Elev= 30
       0  475.32   24.32  463.74   27.36  463.31   33.44  460.73   39.52  458.93
   51.68  454.34    60.8  451.76      76  449.96    91.2  449.09  145.84  448.33
  164.01   446.1  169.74  445.94  183.24   446.6  192.01  446.49  340.04  446.51
  352.18  447.74  358.28  448.99   388.8  448.93  413.21  451.43  425.41  452.12
  434.57  452.07  462.03  455.94  474.24  455.39  483.39  455.62   507.8  458.19
  516.96  458.76  526.11  460.87  544.42  468.43  547.47  468.34  565.78  476.53
#Mann= 3 , 0 , 0
       0      .1       0  192.01    .041       0  340.04      .1       0
Bank Sta=192.01,340.04
XS Rating Curve= 0 ,0
Exp/Cntr=0.3,0.1

Type RM Length L Ch R = 1 ,1632.636,47.08,78.16,126.01
XS GIS Cut Line= 6
     613527.5488     4346205.332     613654.0401     4346088.693
     613674.3611    4346034.4175     613678.5944    4346009.0175
     613644.7887    4345894.3191     613724.3992    4345743.8978
#Sta/Elev= 30
       0  477.17   12.29     471   18.43  466.86    33.8   459.2   39.94  456.78
   46.09  453.36   52.23  452.34   61.45  452.04   92.18  449.54  104.47  446.26
  107.54  445.91  119.83  447.51  135.19  446.43  172.06   447.5  199.51   446.2
  223.91  446.55  372.28  446.33  378.41   446.9   396.8  451.14  445.39  451.22
  478.77  452.14  484.84  452.67  493.95  454.55  500.02  456.48  512.16  462.23
  515.19   462.5   524.3  467.02  536.44  474.66  542.51  477.15  545.54  477.89
#Mann= 3 , 0 , 0
       0      .1       0  223.91    .041       0  378.41      .1       0
Bank Sta=223.91,378.41
XS Rating Curve= 0 ,0
Exp/Cntr=0.3,0.1

Type RM Length L Ch R = 1 ,1554.48 ,45.58,91.44,117.43
XS GIS Cut Line= 4
     613537.0738    4346243.4321     613695.8871    4346110.8865
     613767.0849    4345922.2126     613825.1691    4345809.5828
#Sta/Elev= 30
       0  476.72   18.25  471.96   24.34  469.24   42.59   463.9   60.84  457.35
   69.97   454.9   76.05  453.79   85.18  452.89  118.64  450.56  124.72  449.53
  139.93  445.95  142.97  445.91  149.06  446.04  161.23  448.11  170.35  448.77
  216.02  448.57  261.86  446.96  267.97  446.61  307.69  446.25  384.07  446.49
  390.19  446.83  402.41   449.5  462.83  450.91  483.95  452.32     493   453.8
  505.07  459.68  517.14  467.61  523.17  472.37  529.21  474.61  535.24  478.31
#Mann= 3 , 0 , 0
       0      .1       0  261.86    .041       0  390.19      .1       0
Bank Sta=261.86,390.19
XS Rating Curve= 0 ,0
Exp/Cntr=0.3,0.1

Type RM Length L Ch R = 1 ,1463.04 ,100.83,91.44,96.16
XS GIS Cut Line= 5
     613534.9571    4346278.3572     613722.5106    4346119.4105
     613759.1826    4346091.4884     613857.0682    4345988.2635
     613935.8681    4345923.8081
#Sta/Elev= 30
       0  477.27    6.15  475.99   15.37  475.13   24.58  472.37   43.02  468.85
   52.24  465.66   64.53  462.19   95.27  455.29     126   452.8  169.02  446.86
  181.31  445.91  187.46  446.44   193.6   448.6  227.41  449.63  297.99  448.18
  319.18  448.18  328.26  449.04  337.34  447.79  340.37  446.74  346.42  445.94
  422.09  445.94  428.14  446.44  437.19  450.54  440.18  451.38  470.13  454.22
  491.08  455.65  494.08  456.39  506.06  461.41  524.02   471.7     536  477.55
#Mann= 3 , 0 , 0
       0      .1       0  340.37    .041       0  428.14      .1       0
Bank Sta=340.37,428.14
XS Rating Curve= 0 ,0
Exp/Cntr=0.3,0.1

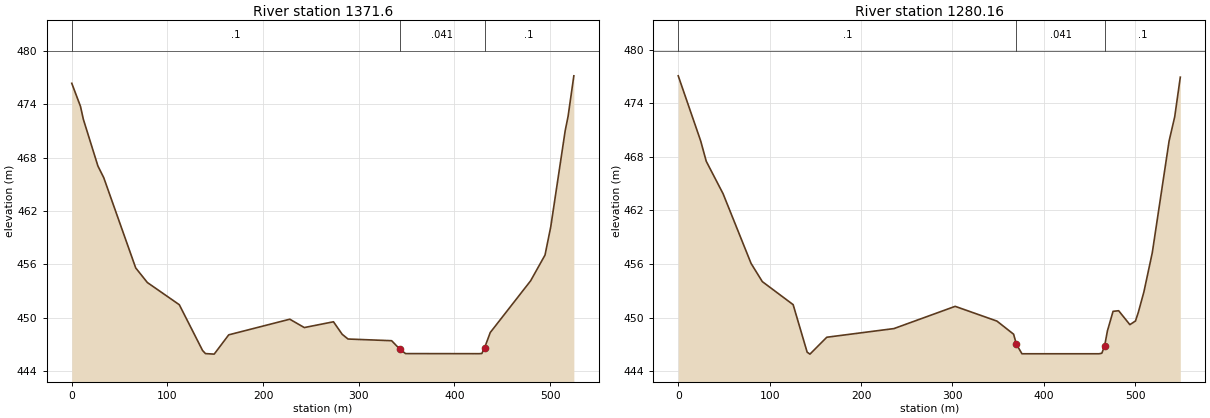
Type RM Length L Ch R = 1 ,1371.6  ,82.88,91.44,86.38
XS GIS Cut Line= 6
     613594.2239    4346339.4761     613786.3507    4346200.7399
     613855.4111    4346136.3262     613872.4735    4346105.7514
     613908.3642    4346066.1661     613988.4539    4345999.4858
#Sta/Elev= 30
       0  476.36    9.11  473.76   12.15  472.29   27.34  467.05   33.42  465.74
   66.84  455.58   78.99  453.94  112.41  451.44  136.72  446.29  139.76  445.94
  148.87  445.88  164.06  448.05  227.87  449.81  243.07  448.87  273.54  449.52
  282.68  448.11  288.77  447.58  334.34  447.39  343.09  446.42  348.93  445.94
  425.72  445.93  428.64  445.95  431.57  446.61  437.42  448.31  479.61  454.13
  494.67  457.03   500.7  460.23  515.76  471.03  518.78  472.64   524.8   477.2
#Mann= 3 , 0 , 0
       0      .1       0  343.09    .041       0  431.57      .1       0
Bank Sta=343.09,431.57
XS Rating Curve= 0 ,0
Exp/Cntr=0.3,0.1

Type RM Length L Ch R = 1 ,1280.16 ,65.43,91.44,114.83
XS GIS Cut Line= 6
     613612.7448    4346396.3616     613807.6272    4346292.6247
     613911.5999    4346198.7318     613940.1805     4346167.209
     613972.2791    4346131.8062     614032.1715    4346054.0763
#Sta/Elev= 30
       0  477.06   24.53  469.78   30.66  467.49   49.06  463.86   79.72  456.05
   91.99  454.02  125.72  451.44  141.05  446.12  144.12   445.9  162.51  447.79
     236  448.76     303  451.25  348.68   449.6  366.94  448.13  369.98  447.01
  376.06  445.94   460.4  445.94  463.47     446  466.54  446.84   469.6  448.51
  475.74  450.69  481.87  450.76  494.14   449.2  500.27  449.61  503.33  450.56
  509.47  452.86  518.67  457.26  537.07  469.77   543.2  472.47  549.33  476.91
#Mann= 3 , 0 , 0
       0      .1       0  369.98    .041       0  466.54      .1       0
Bank Sta=369.98,466.54
XS Rating Curve= 0 ,0
Exp/Cntr=0.3,0.1