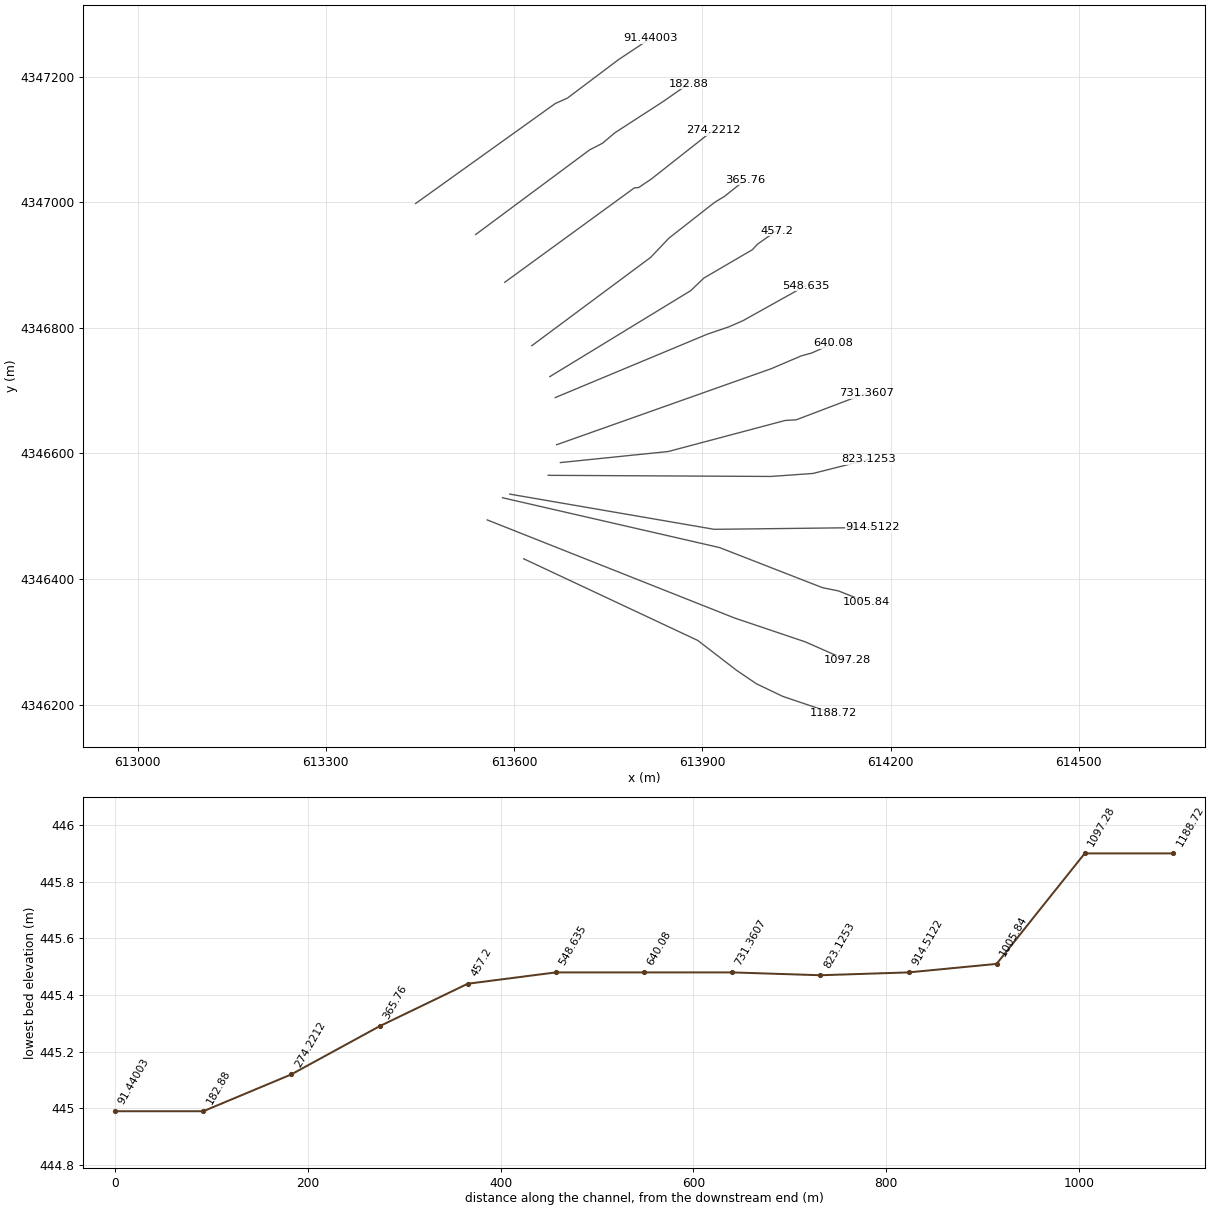
HEC-RAS study CheatRiver.prj: CheatRiver

--- CheatRiver.g01 (geometry) --- (continued)

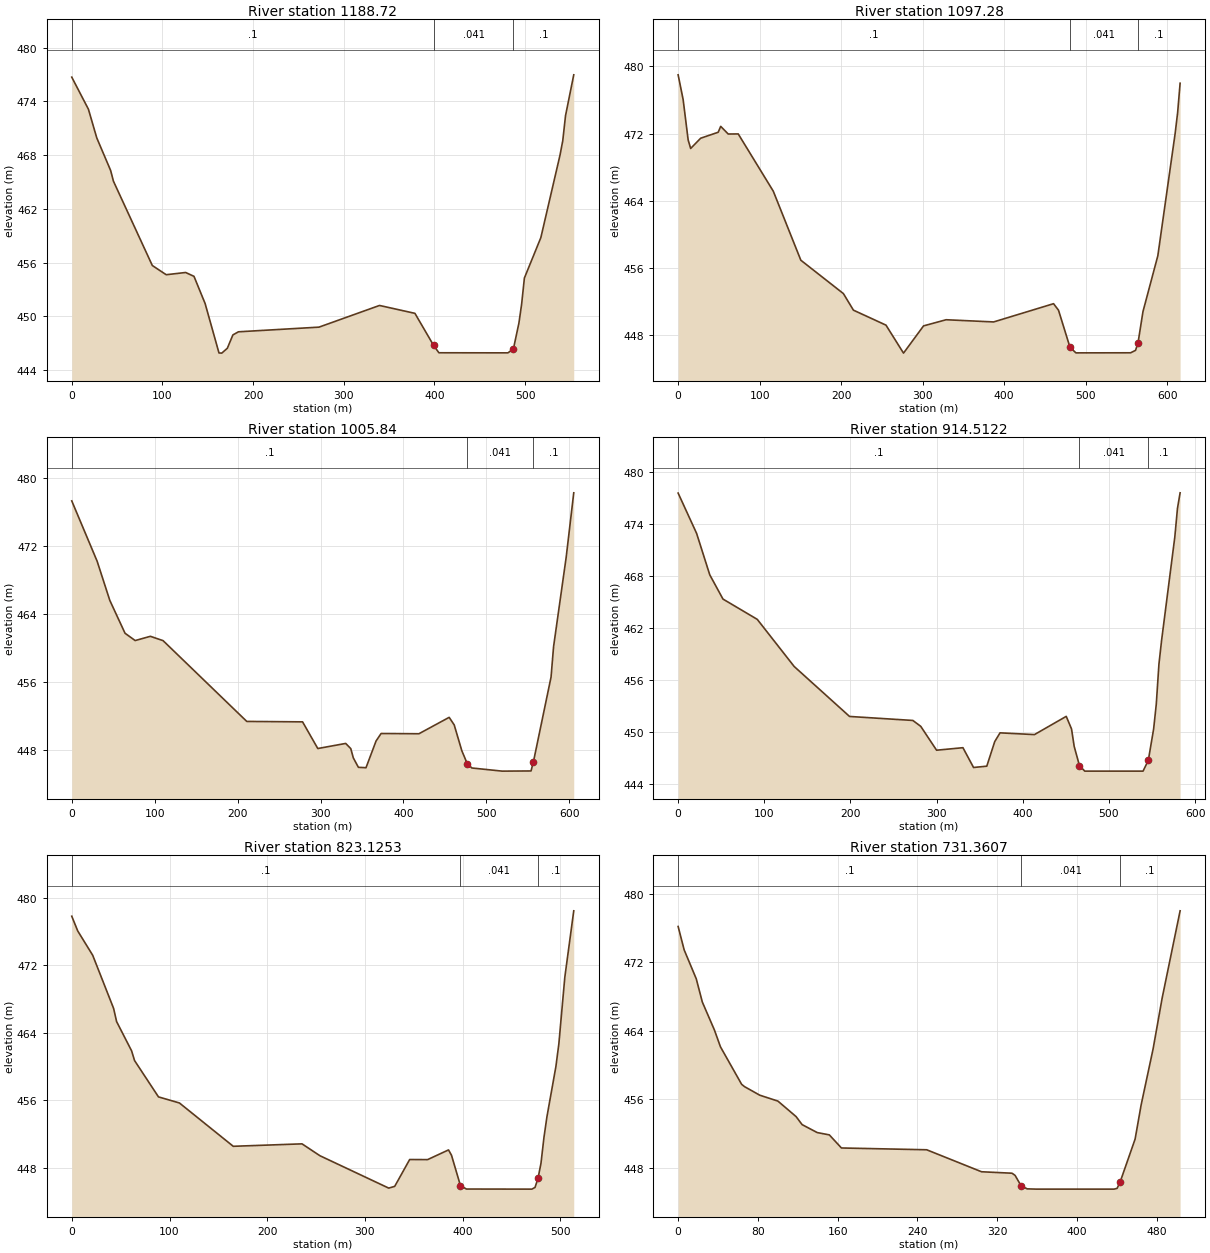
Type RM Length L Ch R = 1 ,1188.72 ,59.78,91.44,94.02
XS GIS Cut Line= 6
     613615.3906    4346432.0804     613892.8232    4346302.0505
     613954.7359    4346254.4254     613986.1656     4346233.118
     614028.1269    4346213.0496     614108.3654    4346185.9373
#Sta/Elev= 30
       0   476.7   18.38  473.12   27.58  469.92    42.9  466.28   45.96  465.09
   88.85  455.68  104.17  454.65  125.62   454.9  134.81  454.47  147.07  451.44
  162.39  445.92  165.45   445.9  171.58  446.44  177.71  447.93  183.84  448.28
  272.69   448.8  339.44  451.22   378.5  450.34  399.11  446.76  404.95  445.94
  481.09  445.93  487.14  446.37  493.19  449.25  496.21  451.38  499.24  454.28
  517.39  458.79  538.56  468.01  541.58  469.62  544.61   472.4  553.68  476.96
#Mann= 3 , 0 , 0
       0      .1       0  399.11    .041       0  487.14      .1       0
Bank Sta=399.11,487.14
XS Rating Curve= 0 ,0
Exp/Cntr=0.3,0.1

Type RM Length L Ch R = 1 ,1097.28 ,95.91,91.44,95.83
XS GIS Cut Line= 4
     613557.1822     4346493.993     613951.3537    4346337.8164
      614064.093    4346299.8214     614130.8248    4346270.4525
#Sta/Elev= 30
       0     479    6.14  476.06   12.29  471.26   15.36  470.24   27.65  471.46
   49.16  472.17   52.23  472.87   61.45  471.96   73.74  471.97  116.75  465.16
  150.54  456.95  202.77  452.98  215.06  451.01     255  449.23  276.51   445.9
  301.09  449.14  328.74  449.87  387.12  449.61  460.59  451.78  466.69     451
  480.75  446.59  488.04  445.93   555.1  445.94  561.18  446.23  564.22  447.12
  570.29  450.84  588.52  457.48  609.79  472.05  612.82  474.51  615.86     478
#Mann= 3 , 0 , 0
       0      .1       0  480.75    .041       0  564.22      .1       0
Bank Sta=480.75,564.22
XS Rating Curve= 0 ,0
Exp/Cntr=0.3,0.1

Type RM Length L Ch R = 1 ,1005.84 ,50.89,91.33,104.52
XS GIS Cut Line= 5
     613581.6043    4346529.2688      613927.448     4346449.948
     614091.7351    4346386.0193     614116.8199    4346380.9759
     614162.0972    4346363.1536
#Sta/Elev= 30
       0  477.32   30.59  470.22   45.88  465.61   64.24  461.74   76.47  460.88
   94.82  461.38  110.12  460.87  211.06  451.36  278.35  451.31  296.71  448.17
  330.35  448.77  336.47  448.16  339.53  447.07  345.65  445.96  354.82  445.91
  366.98  449.06  373.06  449.94  418.65  449.91  455.12  451.84   461.2  450.95
  470.32  447.93  476.88   446.4  482.48  445.88  518.95  445.51  553.85  445.53
   556.7  446.59  577.99  456.58  581.03  460.16  596.23  470.68  605.36  478.27
#Mann= 3 , 0 , 0
       0      .1       0  476.88    .041       0   556.7      .1       0
Bank Sta=476.88,556.7
XS Rating Curve= 0 ,0
Exp/Cntr=0.3,0.1

Type RM Length L Ch R = 1 ,914.5122,83.57,91.39,100.71
XS GIS Cut Line= 3
     613593.2097    4346535.0476      613918.997    4346478.9963
     614171.0376    4346481.9094
#Sta/Elev= 30
       0  477.52   21.43  472.88   36.73   468.1   52.03  465.31   91.83  462.97
  134.68  457.54  198.96  451.78  272.42  451.32   281.6  450.64  299.97  447.89
  330.57  448.18  342.87   445.9  358.24  446.05  367.46  448.88  373.61  449.89
  413.57  449.69  450.46  451.79   456.6  450.34  459.68  448.33  465.82  446.11
  471.97  445.48   539.6  445.48  545.74  446.72  551.89  450.34  554.97  453.19
  558.04   457.8  561.11  460.53  576.48  472.46  579.56  475.76  582.63  477.55
#Mann= 3 , 0 , 0
       0      .1       0  465.82    .041       0  545.74      .1       0
Bank Sta=465.82,545.74
XS Rating Curve= 0 ,0
Exp/Cntr=0.3,0.1

Type RM Length L Ch R = 1 ,823.1253,76.89,91.76,97.35
XS GIS Cut Line= 4
     613654.4238    4346564.9568     614009.3325    4346563.1778
     614076.4091    4346567.9501     614165.0935    4346590.3199
#Sta/Elev= 30
       0  477.84    6.12  476.09   21.42  473.21   42.83   466.9   45.89  465.34
   61.19  461.88   64.25  460.72   88.73  456.41  110.15  455.69  165.22  450.55
  235.59  450.84  253.95  449.43  324.32  445.59  330.44   445.8  345.73  448.98
  364.08  448.97  385.48  450.12  388.54  449.49  397.71  445.88  403.82  445.48
  470.77  445.47  473.99  445.67  477.04  446.74  480.09  448.53  483.13  451.59
  486.18  454.05  495.33  459.99  498.38   462.7  504.48   470.6  513.62  478.48
#Mann= 3 , 0 , 0
       0      .1       0  397.71    .041       0  477.04      .1       0
Bank Sta=397.71,477.04
XS Rating Curve= 0 ,0
Exp/Cntr=0.3,0.1

Type RM Length L Ch R = 1 ,731.3607,81.44,91.28,91.42
XS GIS Cut Line= 5
     613673.8769    4346585.2701     613845.9169    4346602.9107
     614032.0781    4346652.3265     614049.7411    4346653.3729
     614162.2944    4346696.1285
#Sta/Elev= 30
       0  476.18    6.07  473.44    18.2  470.06   24.27  467.35   36.41  464.08
   42.48  462.11   63.72  457.73   66.75  457.45   81.92  456.46  100.12  455.77
  118.33  453.96   124.4  453.02  139.57  452.09   151.7  451.82  163.84  450.29
  249.37  450.08   304.4  447.51  334.98  447.34  338.04  447.09  344.15  445.86
  350.26  445.51  359.44  445.48  437.42  445.48  440.43  445.57  443.44  446.31
  458.49  451.33  464.51  455.31  476.55  461.88  485.58  467.79  503.64  478.01
#Mann= 3 , 0 , 0
       0      .1       0  344.15    .041       0  443.44      .1       0
Bank Sta=344.15,443.44
XS Rating Curve= 0 ,0
Exp/Cntr=0.3,0.1

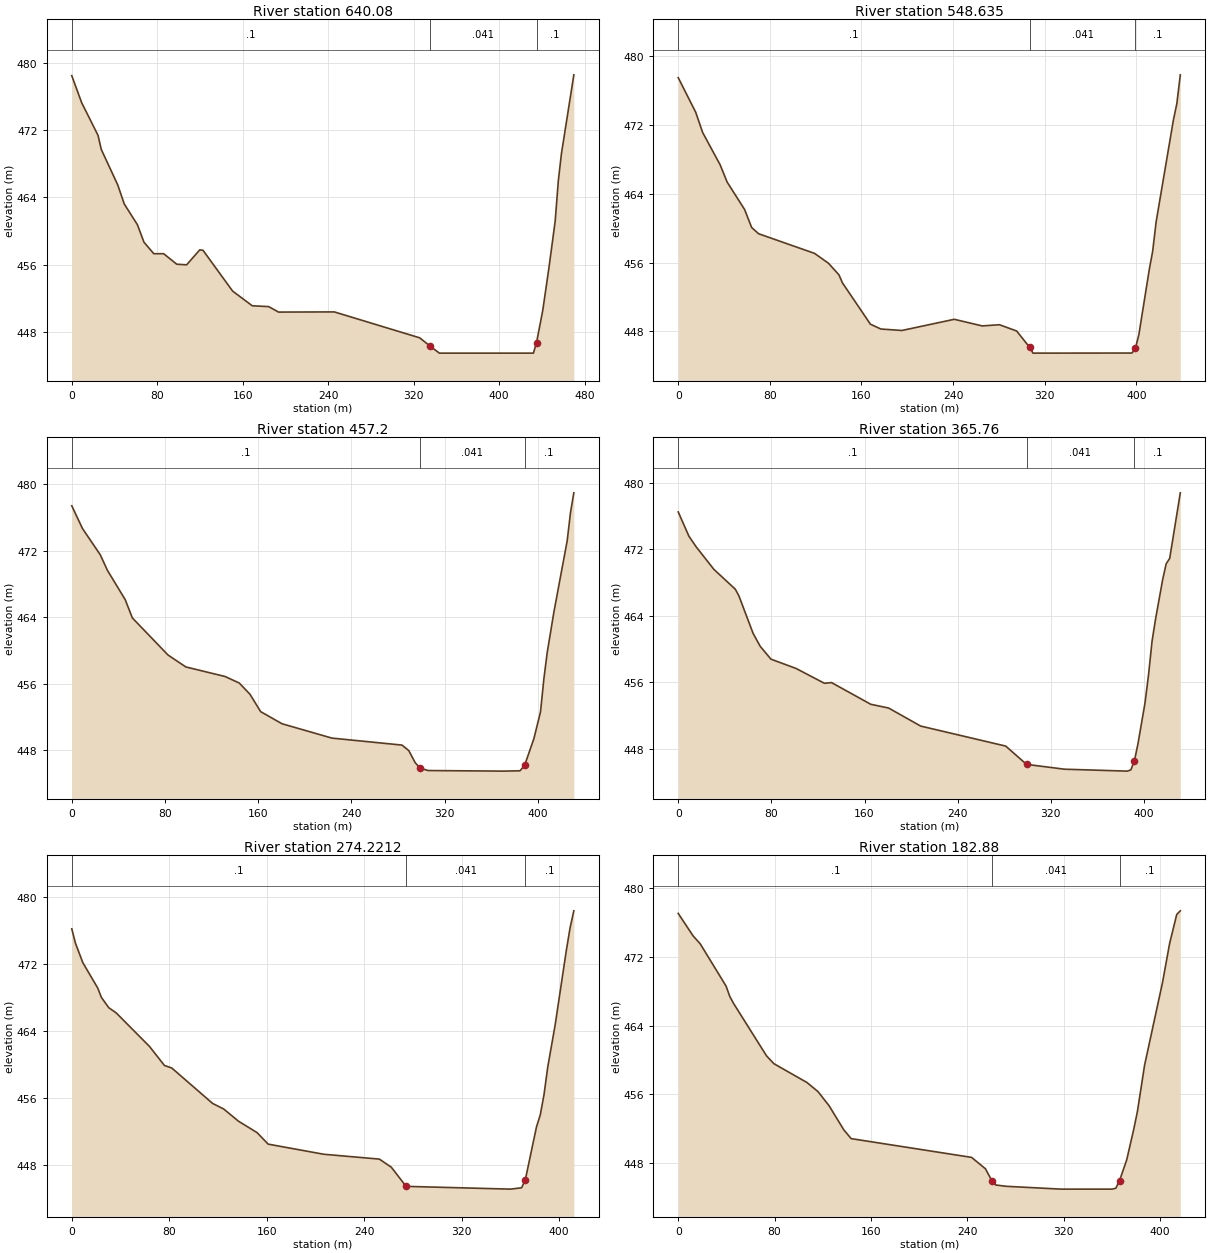
Type RM Length L Ch R = 1 ,640.08  ,85.95,91.45,98.7
XS GIS Cut Line= 5
     613667.8652    4346613.6972     614009.5882    4346734.6591
     614057.6824    4346755.1269     614074.4115    4346759.7475
     614108.9348    4346775.1857
#Sta/Elev= 30
       0  478.47    9.22  475.27   24.58  471.37   27.65  469.69   43.01  465.49
   49.15  463.21   61.44  460.75   67.58  458.67    76.8   457.3   86.02   457.3
   98.31  456.05  107.52  455.98  119.81  457.76  122.88   457.7  150.53  452.86
  168.96  451.11  184.32  451.01  193.54  450.36  245.76  450.38  325.64   447.3
  334.85  446.37  344.07  445.48  432.12  445.48  435.03  446.74  440.85  450.56
  446.67  455.66  452.49  461.19   455.4  465.95  458.31  469.18  469.94  478.57
#Mann= 3 , 0 , 0
       0      .1       0  334.85    .041       0  435.03      .1       0
Bank Sta=334.85,435.03
XS Rating Curve= 0 ,0
Exp/Cntr=0.3,0.1

Type RM Length L Ch R = 1 ,548.635 ,84.32,91.44,96.28
XS GIS Cut Line= 5
     613665.6219    4346688.7664     613907.8428    4346789.6455
     613942.0192    4346801.2595     613965.1943    4346811.4001
     614065.2811    4346867.2159
#Sta/Elev= 30
       0  477.48   15.26  473.46   21.36   471.1   36.61  467.35   42.71  465.35
   57.97  462.16   64.07  460.08   70.17  459.35  118.99  457.07  131.19  455.92
  140.35  454.57   143.4  453.64  167.81  448.84  176.96  448.28  195.27  448.11
  241.03  449.41   265.4  448.64  280.44  448.78  295.48  448.05  306.92  446.14
  309.73  445.48  396.16  445.49  399.17  446.03  402.19  447.62  411.24  455.15
  414.25  457.32  417.27  460.73  432.35  472.56  435.36  474.47  438.38  477.81
#Mann= 3 , 0 , 0
       0      .1       0  306.92    .041       0  399.17      .1       0
Bank Sta=306.92,399.17
XS Rating Curve= 0 ,0
Exp/Cntr=0.3,0.1

Type RM Length L Ch R = 1 ,457.2   ,84.05,91.44,92.8
XS GIS Cut Line= 6
     613656.9734    4346722.1096     613881.5894    4346859.0348
     613902.5922     4346879.128     613979.9066     4346924.289
     613988.0844    4346933.1183     614018.5146    4346954.4463
#Sta/Elev= 30
       0  477.43    9.18  474.69   24.47  471.52   30.59  469.65   45.88  466.11
      52  463.91   82.59  459.44   97.88     458  131.53  456.85  143.77  456.06
  152.94  454.71  162.12  452.61  180.47  451.15   223.3  449.42  283.41  448.58
  289.22  447.92  294.88  446.43  299.04   445.8  305.88  445.51  369.93  445.44
  384.72  445.48  388.66  446.14  396.61  449.35  402.32   452.6  405.18  456.55
  408.04  459.72  413.76  464.59  425.19   473.2  428.05  476.62  430.91  478.99
#Mann= 3 , 0 , 0
       0      .1       0  299.04    .041       0  388.66      .1       0
Bank Sta=299.04,388.66
XS Rating Curve= 0 ,0
Exp/Cntr=0.3,0.1

Type RM Length L Ch R = 1 ,365.76  ,102.95,91.54,94.03
XS GIS Cut Line= 6
     613628.3334     4346771.413     613817.6594    4346911.9626
     613846.9851    4346942.7532     613919.6463    4346999.6045
     613935.1634    4347008.9911     613968.4283    4347035.4181
#Sta/Elev= 30
       0  476.47    9.19  473.55   15.31  472.29   30.62  469.56      49  467.18
   52.06  466.39   64.31  461.86   70.43   460.3   79.62  458.76  101.05  457.65
  125.55  455.86  131.68  455.94  165.36  453.33  180.67  452.88  208.23  450.71
  281.29   448.3  299.15   446.1  331.88  445.52  385.69  445.29  388.71  445.44
  391.74  446.52  394.78  448.54  400.85  453.47  403.88  456.84  406.92  460.92
  409.95   463.6  416.02  468.32  419.05  470.23  422.09  470.89  431.19  478.77
#Mann= 3 , 0 , 0
       0      .1       0  299.15    .041       0  391.74      .1       0
Bank Sta=299.15,391.74
XS Rating Curve= 0 ,0
Exp/Cntr=0.3,0.1

Type RM Length L Ch R = 1 ,274.2212,92.33,91.34,85.51
XS GIS Cut Line= 5
     613585.1804    4346872.3621     613791.7146    4347022.6457
     613798.4928     4347023.195     613818.6449     4347036.682
     613917.2596     4347114.324
#Sta/Elev= 30
       0  476.25    3.04  474.52    9.12  472.19   21.29  469.17   24.33  468.04
   30.41  466.81   36.49  466.19   63.86  462.17   76.02  459.91    82.1   459.6
  115.55  455.37  124.67   454.7  136.83  453.24  152.04  451.88  161.16   450.5
  206.77  449.29  252.38  448.71  262.22  447.74  274.35  445.45  359.94  445.12
  369.13  445.28  372.19  446.25  381.37  452.58  384.43  453.98  387.49   456.4
  390.56   459.7  396.68  464.78  405.86   473.7  408.92  476.38  411.99   478.4
#Mann= 3 , 0 , 0
       0      .1       0  274.35    .041       0  372.19      .1       0
Bank Sta=274.35,372.19
XS Rating Curve= 0 ,0
Exp/Cntr=0.3,0.1

Type RM Length L Ch R = 1 ,182.88  ,93.52,91.44,95
XS GIS Cut Line= 6
     613538.9047     4346948.463     613720.4627    4347083.1802
     613741.1285     4347093.842     613760.7206    4347110.4346
     613837.3709    4347159.9879      613878.749    4347188.8164
#Sta/Elev= 30
       0  477.04   12.22  474.45   18.33  473.49   39.72  468.59   42.77   467.4
   45.83   466.6   73.32  460.48   79.43  459.57  106.93  457.38  116.09  456.32
  125.26  454.68  137.48  451.88  143.59  450.86  243.52  448.68  255.04  447.36
  260.74  445.88   263.6  445.47  272.16  445.32  317.64  444.99   360.3  444.99
  363.36   445.1  366.42  445.99  372.35  448.39  378.28     452  381.25  454.02
  387.18  459.39  402.01  468.96  407.95  473.53  413.88  476.92  416.85  477.34
#Mann= 3 , 0 , 0
       0      .1       0  260.74    .041       0  366.42      .1       0
Bank Sta=260.74,366.42
XS Rating Curve= 0 ,0
Exp/Cntr=0.3,0.1

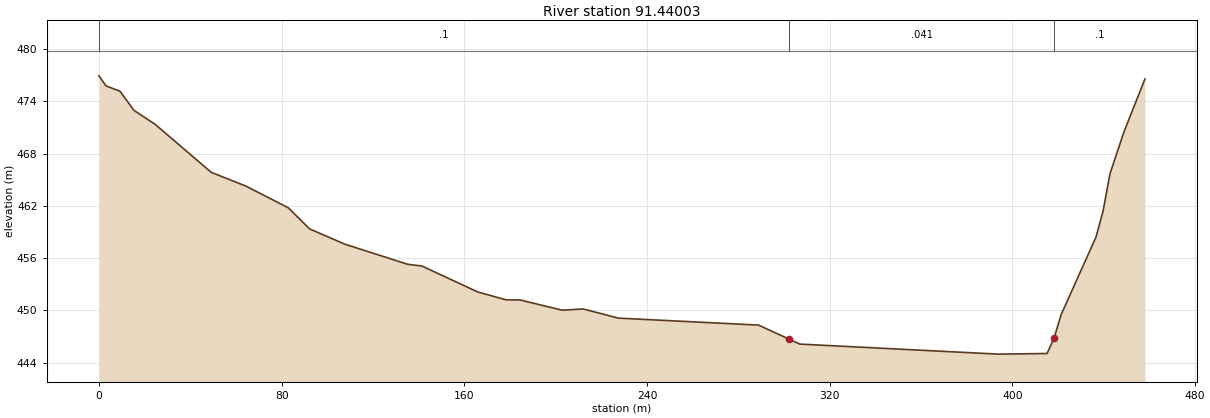
Type RM Length L Ch R = 1 ,91.44003,95.97,91.44,80.43
XS GIS Cut Line= 5
     613443.1254    4346997.8079     613665.6118    4347156.9232
     613685.1595    4347165.6978     613766.5669    4347226.9245
     613817.5827    4347260.7776
#Sta/Elev= 30
       0  476.91    3.07  475.76    9.22  475.14   15.37  472.94   24.59  471.35
   49.17  465.84   64.54  464.24   82.98  461.76    92.2  459.36  107.57  457.61
  135.23  455.29  141.37   455.1  165.96  452.11  178.25  451.22   184.4   451.2
  202.84  450.03  212.06  450.17  227.43  449.12  288.83  448.32  302.19  446.71
  306.94  446.14  393.82  444.99  415.18  445.06  418.25  446.83  421.31   449.5
  436.61  458.42  439.68  461.37  442.74  465.69  448.86  470.49  458.04  476.55
#Mann= 3 , 0 , 0
       0      .1       0  302.19    .041       0  418.25      .1       0
Bank Sta=302.19,418.25
XS Rating Curve= 0 ,0
Exp/Cntr=0.3,0.1
LCMann Table=0

Chan Stop Cuts=-1
Use User Specified Reach Order=0
Composite Channel Slope=5